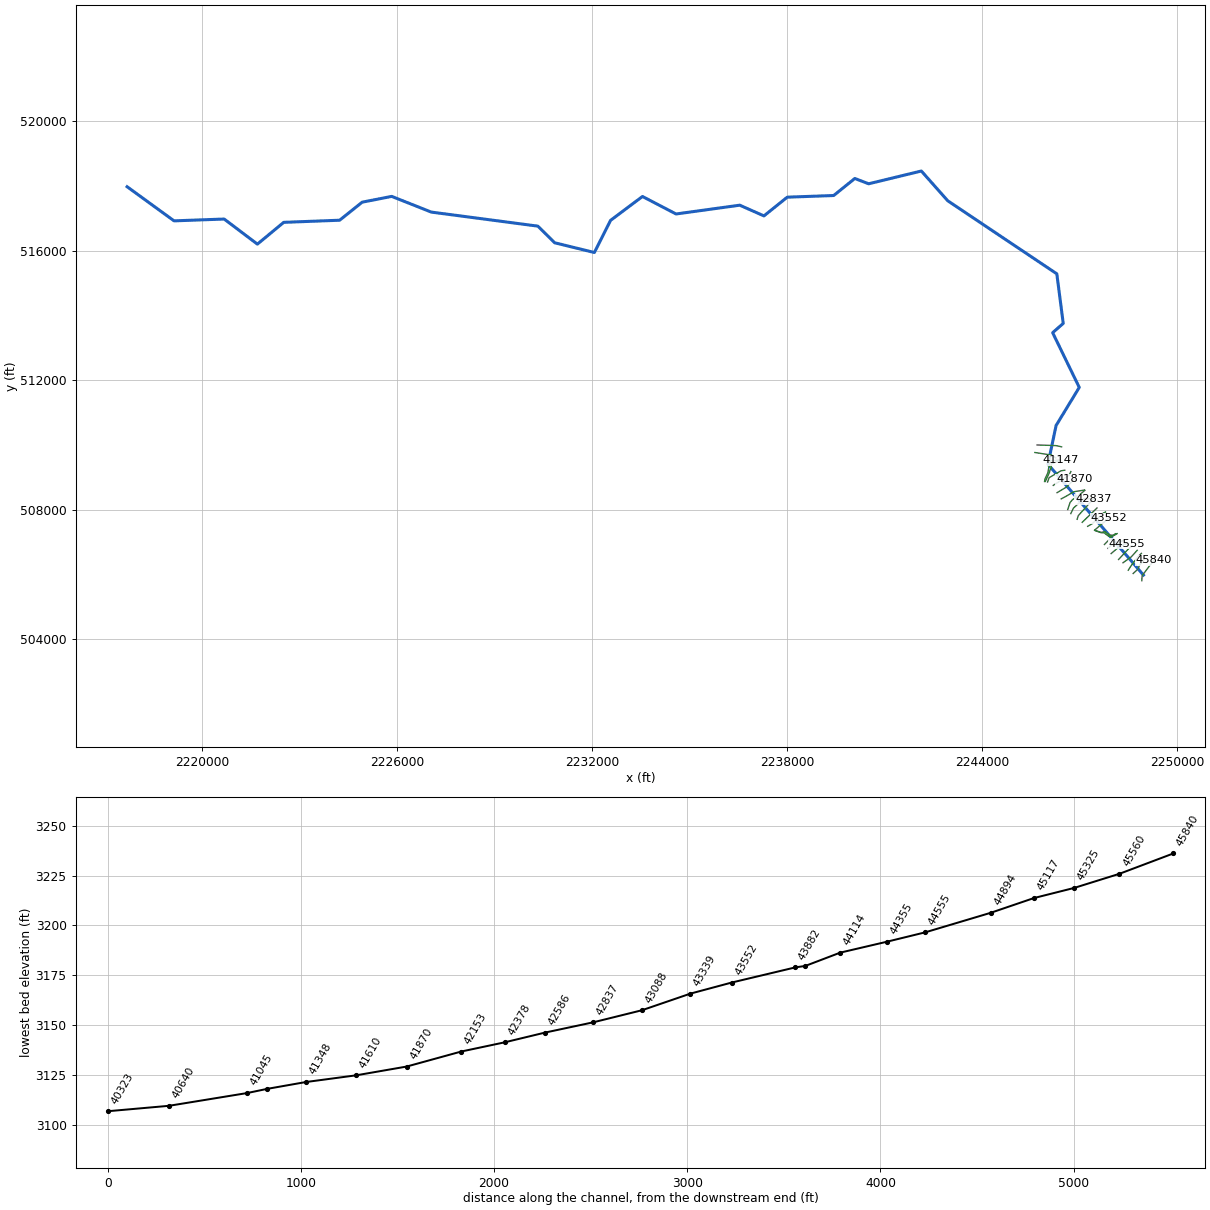
--- BIGSPRFK.prj (project) ---

Proj Title=BIGSPRFK
Current Plan=p01
Default Exp/Contr=0,0
English Units
Geom File=g01
Flow File=f01
Plan File=p01
Background Map Layer=Inundation Boundary (01pct Value_0)
Background Map Layer=Inundation Boundary (01pct Value_0)
Background Map Layer=Inundation Boundary (01pct Value_0)
BEGIN DESCRIPTION:
----------MODEL BY WOOD PLC 2021----------
Stream Name: Big Spring Fork
Flood Zone: Alternating Approximate / Detailed
Pocahontas County, WV
HEC-RAS Version: RAS 6.1.0
Vertical Datum: NAVD88
Projection: NAD 1983 StatePlane West Virginia S FIPS 4702 (US Feet)
Terrain: 1-meter LIDAR (FEMA Region III 3DEP collected 2016-2018)
Land Use: 2019 NLCD
Hydrologic Method:
WV SIR2010-5033 regression equations
Model Notes:
KWSEL tie in / Coincident peak with OLDFLDFK XS 27092
Zone A Approximate: 45840 - 3590; Zone AE Detailed: 3390 - 0
END DESCRIPTION:
DSS File=dss
DSS Export Rating Curves= 0
DSS Export Rating Curve Sorted= 0
DSS Export Volume Flow Curves= 0
DXF OffsetX= 0
DXF OffsetY= 0
DXF ScaleX= 0
DXF ScaleY= 0

--- BIGSPRFK.p01 (plan) ---

Plan Title=Floodplain
Program Version=6.10
Short Identifier=Floodplain
Geom File=g01
Flow File=f01
Subcritical Flow
K Sum by GR= 0
Std Step Tol= 0.01
Critical Tol= 0.01
Num of Std Step Trials= 20
Max Error Tol= 0.3
Flow Tol Ratio= 0.001
Split Flow NTrial= 30
Split Flow Tol= 0.02
Split Flow Ratio= 0.02
Log Output Level= 0
Friction Slope Method= 1
Unsteady Friction Slope Method= 2
Unsteady Bridges Friction Slope Method= 1
Parabolic Critical Depth
Global Vel Dist= 0 , 0 , 0
Global Log Level= 0
CheckData=True
Encroach Param=-1 ,0,0, 2
Encroach River=BIGSPRELK
Encroach Reach=Main
Encroach Node=3590
       1   248.1   351.1
Encroach Node=3390
       1   178.2   257.6
Encroach Node=3046
       1     123     229
Encroach Node=2828
       1   160.5   286.8
Encroach Node=2468
       1     256  366.75
Encroach Node=2016
       1  283.15   347.2
Encroach Node=1879
       1   285.8     372
Encroach Node=1787
       1   300.9   378.4
Encroach Node=1516
       1  962.95  1015.6
Encroach Node=1403
       1     950    1003
Encroach Node=1365
       1   932.6   991.2
Encroach Node=1227
       1   894.2   952.3
Encroach Node=1105
       1  852.18   910.1
Encroach Node=906
       1  847.42   907.4
Encroach Node=740
       1   612.7     709
Encroach Node=672
       1  563.49   669.4
Encroach Node=471
       1   484.5     578
Encroach Node=274
       1     435     558
Encroach Node=227
       1   418.9     554
Encroach Node=144
       1     330     447
Encroach Node=0
       1     330  517.69
Computation Interval=0.1SEC
Output Interval=1SEC
Instantaneous Interval=Max Profile
Mapping Interval=1HOUR
Computation Time Step Use Courant=        0
Computation Time Step Use Time Series=    0
Computation Time Step Count To Double=0
Computation Time Step Max Doubling=0
Computation Time Step Max Halving=0
Computation Time Step Residence Courant=0
Run HTab= 0
Run UNet= 0
Run Sediment= 0
Run PostProcess= 0
Run WQNet= 0
Run RASMapper= 0
UNET Theta= 0
UNET Theta Warmup= 0
UNET ZTol= 0
UNET ZSATol= 0
UNET MxIter= 0
UNET Max Iter WO Improvement= 0
UNET MaxInSteps= 0
UNET DtIC= 0
UNET DtMin= 0
UNET MaxCRTS= 0
UNET WFStab= 0
UNET SFStab= 0
UNET WFX= 1
UNET SFX= 1
UNET Gravity=32.174
UNET 1D Methodology=Finite Difference
UNET DSS MLevel= 1
UNET Pardiso=0
UNET DZMax Abort= 0
UNET Use Existing IB Tables= 0
UNET Froude Reduction=False
UNET Froude Limit= 0
UNET Froude Power= 0
UNET D1 Cores= 0
UNET WindReference=Eulerian
UNET WindDragFormulation=Hsu (1988)
UNET D2 Coriolis=0
UNET D2 Cores= 0
UNET D2 Theta= 1
UNET D2 Theta Warmup= 1
UNET D2 Z Tol= 0.01
UNET D2 Volume Tol= 0.01
UNET D2 Max Iterations= 20
UNET D2 Equation= 0
UNET D2 RampUpFraction=0.1
UNET D2 TimeSlices= 1
UNET D2 Turbulence Formulation=Non-Conservative (original)
UNET D2 Eddy Viscosity=0.3
UNET D2 Transverse Eddy Viscosity=0.1
UNET D2 Smagorinsky Mixing=0
UNET D2 BCVolumeCheck=0
UNET D2 Cores=0
UNET D2 SolverType=PARDISO (Direct)
UNET D2 Minimum Iterations= 2147483647
UNET D2 Maximum Iterations= 2147483647
UNET D2 Restart Number= 10
UNET D2 Relaxation Coeff=1.3
UNET D2 SOR Precondition Iterations= 10
UNET D2 ILUT Maximum Fill= 8
UNET D2 ILUT Tolerance=1E-08
UNET D1D2 MaxIter= 0
UNET D1D2 ZTol=0.01
UNET D1D2 QTol=0.1
UNET D1D2 MinQTol=1
DSS File=dss
Write IC File= 0
Write IC File at Fixed DateTime=0
Write IC File at Sim End=0
Echo Input=False
Echo Parameters=False
Echo Output=False
Write Detailed= 0
HDF Write Warmup=0
HDF Write Time Slices=0
HDF Flush=0
HDF Compression= 1
HDF Chunk Size= 1
HDF Spatial Parts= 1
HDF Use Max Rows=0
HDF Fixed Rows= 1
Calibration Method= 0
Calibration Iterations= 20
Calibration Max Change=0.05
Calibration Tolerance=0.2
Calibration Maximum=1.5
Calibration Minimum=0.5
Calibration Optimization Method= 1
WQ AD Non Conservative
WQ ULTIMATE=-1
WQ Max Comp Step=1HOUR
WQ Output Interval=15MIN
WQ Output Selected Increments= 0
WQ Output face flow=0
WQ Output face velocity=0
WQ Output face area=0
WQ Output face dispersion=0
WQ Output cell volume=0
WQ Output cell surface area=0
WQ Output cell continuity=0
WQ Output cumulative cell continuity=0
WQ Output face conc=0
WQ Output face dconc_dx=0
WQ Output face courant=0
WQ Output face peclet=0
WQ Output face adv mass=0
WQ Output face disp mass=0
WQ Output cell mass=0
WQ Output cell source sink temp=0
WQ Output nsm pathways=0
WQ Output nsm derived pathways=0
WQ Create Restart=0
WQ Fixed Restart=0
WQ System Summary=0
WQ Write To DSS=0
Sorting and Armoring Iterations= 10
XS Update Threshold= 0.02
Bed Roughness Predictor= 0
Hydraulics Update Threshold= 0.02
Energy Slope Method= 1
Volume Change Method= 1
Sediment Retention Method= 0
Sediment TS Multiplier= 1
Warm Up Method= 0
XS Weighting Method= 0
Number of US Weighted Cross Sections= 1
Number of DS Weighted Cross Sections= 1
Upstream XS Weight=0
Main XS Weight=1
Downstream XS Weight=0
Number of DS XS's Weighted with US Boundary= 1
Upstream Boundary Weight= 1
Weight of XSs Associated with US Boundary= 0
Number of US XS's Weighted with DS Boundary= 1
Downstream Boundary Weight= 0.5
Weight of XSs Associated with DS Boundary= 0.5
Percentile Method= 0
Sediment Output Level= 3
Mass or Volume Output= 0
Output Increment Type= 1
Profile and TS Output Increment= 1
Transport Output Increment 1
XS Output Flag= 0
XS Output Increment= 10
Read HDF5 Sediment Hotstart= 0
Sediment Hotstart Type= 0
Write Gradation File= 0
Read Gradation Hotstart= 0
Write HDF5 File= 1
Write Binary Output= 1
Write DSS Sediment File= 0
DSS Sediment Output Type= 1
SV Curve= 0
Specific Gage Flag= 0
Subcell Erosion Methods= 0
Subcell Deposition Methods= 0
Advection Scheme= 1
Matrix Solver= 0
Implicit Weighting Factor= 1
Maximum Outer Loop Convergence Iterations= 5
Convergence Maximum Absolute= 0.001
Convergence RMSE= 0.0001
Grain Fractions Max Abs Error= 0.001
Max Subgrid Regions= 1
Max Subgrid Length Scale= 3.402823E+38
Initial Layer Thickness= 3.402823E+38
Min Layer Thickness= 3.402823E+38
Max Layer Thickness= 3.402823E+38
Number of Layers= 5

--- BIGSPRFK.f01 (steady flow) ---

Flow Title=Flow
Program Version=6.10
Number of Profiles= 7
Profile Names=01pct,FWY,10pct,04pct,02pct,0_2pct,01plus
River Rch & RM=BIGSPRELK,Main            ,45840
     579     579     306     407     491     809     857
River Rch & RM=BIGSPRELK,Main            ,42586
     644     644     342     453     545     897     952
River Rch & RM=BIGSPRELK,Main            ,40640
     875     875     470     620     743    1210    1290
River Rch & RM=BIGSPRELK,Main            ,39495
     974     974     526     692     829    1350    1440
River Rch & RM=BIGSPRELK,Main            ,35697
    1320    1320     721     944    1130    1820    1950
River Rch & RM=BIGSPRELK,Main            ,32440
    1870    1870    1030    1340    1600    2550    2760
River Rch & RM=BIGSPRELK,Main            ,30038
    2260    2260    1260    1630    1930    3070    3340
River Rch & RM=BIGSPRELK,Main            ,24065
    2700    2700    1520    1960    2320    3670    4000
River Rch & RM=BIGSPRELK,Main            ,20751
    3090    3090    1740    2240    2650    4180    4560
River Rch & RM=BIGSPRELK,Main            ,12192
    3440    3440    1950    2500    2960    4640    5090
River Rch & RM=BIGSPRELK,Main            ,0
    4640    4640    2640    3380    3990    6270    6830
Boundary for River Rch & Prof#=BIGSPRELK,Main            , 1
Up Type= 0
Dn Type= 1
Dn Known WS=2668
Boundary for River Rch & Prof#=BIGSPRELK,Main            , 2
Up Type= 0
Dn Type= 1
Dn Known WS=2668.4
Boundary for River Rch & Prof#=BIGSPRELK,Main            , 3
Up Type= 0
Dn Type= 1
Dn Known WS=2665.5
Boundary for River Rch & Prof#=BIGSPRELK,Main            , 4
Up Type= 0
Dn Type= 1
Dn Known WS=2666.5
Boundary for River Rch & Prof#=BIGSPRELK,Main            , 5
Up Type= 0
Dn Type= 1
Dn Known WS=2667.2
Boundary for River Rch & Prof#=BIGSPRELK,Main            , 6
Up Type= 0
Dn Type= 1
Dn Known WS=2669.4
Boundary for River Rch & Prof#=BIGSPRELK,Main            , 7
Up Type= 0
Dn Type= 1
Dn Known WS=2670
DSS Import GetInterval= 0
DSS Import GetPeak= 0
DSS Import FillOption= 0

--- BIGSPRFK.g01 (geometry) ---

Geom Title=Geometry
Program Version=6.10

River Reach=BIGSPRELK       ,Main
Reach XY= 30
2248956.62404455505983.2479380672246018.60793898509406.629870817
2246268.50999822510600.4060265572246981.99019855511776.803280056
2246163.03284697 513466.305150392246488.43902031513752.953855306
2246291.14709206515283.4507943092242935.35590339517538.822267815
2242122.65149206518457.9247603122240501.67409097518063.692937225
2240075.16214871518227.0817180572239425.34487881517701.315053061
2237996.64202756517650.267911062 2237279.4948398517072.116836399
2236534.10098939517402.8300857252234574.50385872517131.402150899
2233541.67095064517671.3498898892232560.43013097516934.915995315
 2232061.0938593515941.8271022292230840.57759956516242.161803395
2230322.60586648516755.8750148122227042.13768989 517189.84724398
2225825.86190721517674.4040176422224917.25512864517495.878127977
2224223.09509964516938.6945310532222502.16711105  516873.0719589
2221692.99090789516200.4663487232220669.08810006516975.197082728
2219127.62694414516919.1010663062217684.10555297517972.357818067

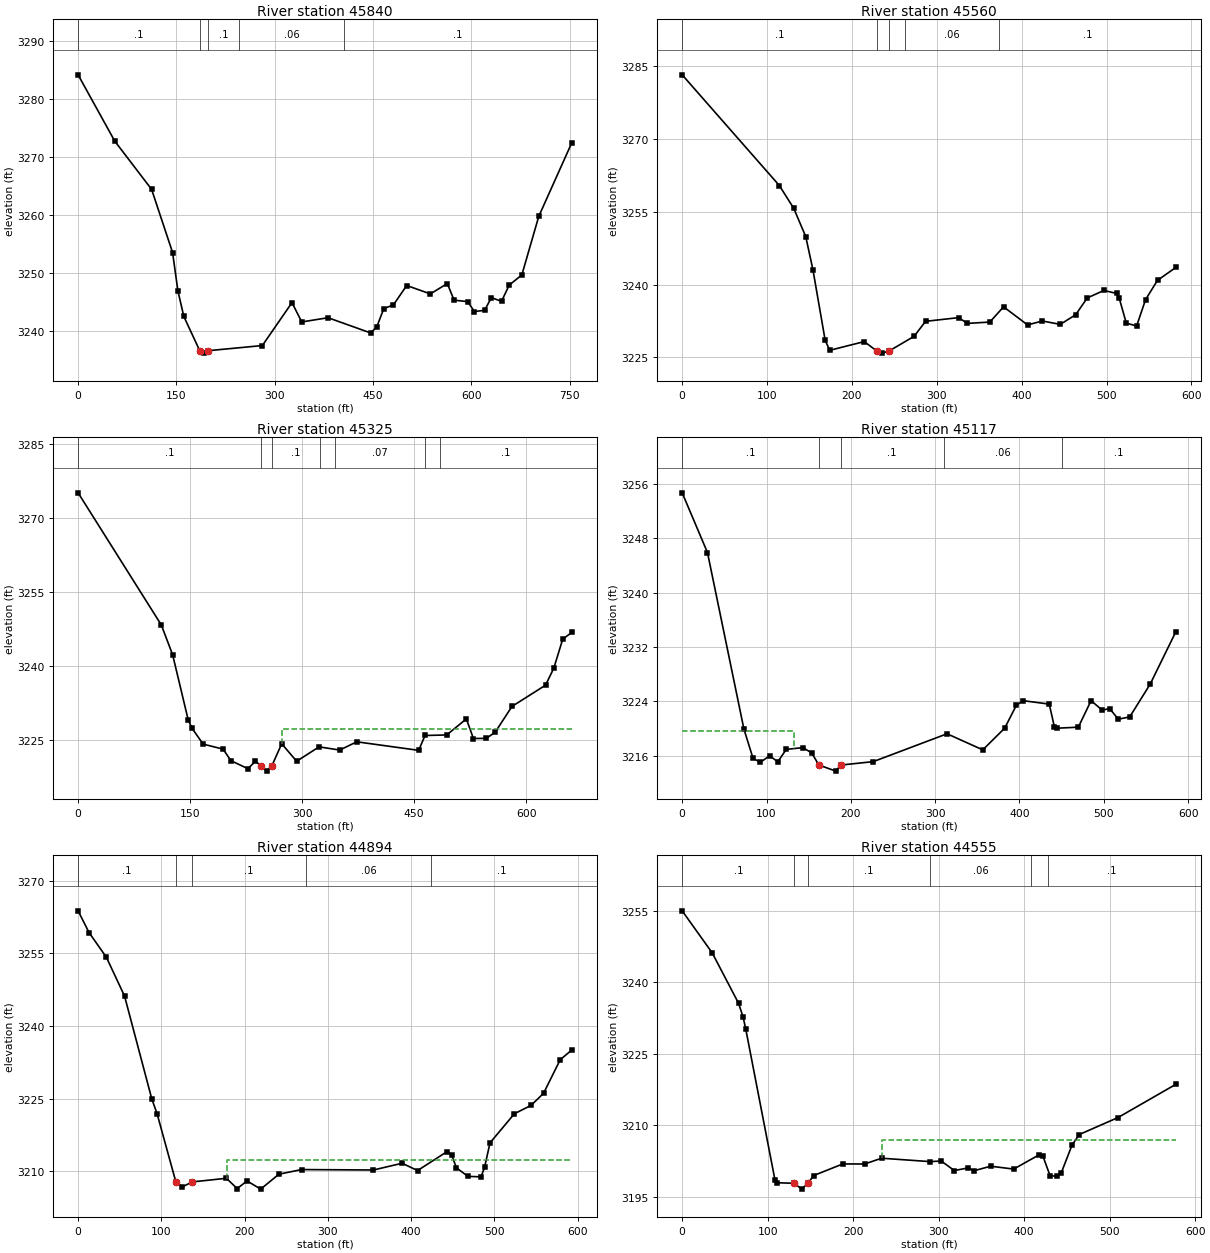
Type RM Length L Ch R = 1 ,45840   ,271,279.3,287.2
XS GIS Cut Line= 4
2248906.14160616505809.4036061612248917.08636922505964.831142551
2249126.33292163506243.8265457652249283.63986839506436.313502344
#Sta/Elev= 30
       0 3284.21    55.9 3272.75   112.1 3264.41   144.1 3253.49   152.2 3246.87
   161.2 3242.45185.37923236.554   192.6  3236.1   198.3 3236.52     281 3237.41
   326.2 3244.83   341.1 3241.49   381.2 3242.22   446.2 3239.59   455.4  3240.6
   466.2 3243.78     481 3244.45   501.2 3247.79   537.3 3246.34   563.1 3248.13
   573.5 3245.25   594.1 3245.01   604.5 3243.29     620  3243.5   630.3 3245.69
   645.8 3245.06   657.5 3247.86   676.8 3249.62   702.6 3259.74   753.1  3272.5
#Mann= 5 ,-1,0
       0      .1       0185.3792    .045       0   198.3      .1       0
  245.81     .06       0  405.81      .1       0
Bank Sta=185.3792,198.3
XS Rating Curve= 0 ,0
Exp/Cntr=0.3,0.1

Type RM Length L Ch R = 1 ,45560   ,241.4,234.9,226.6
XS GIS Cut Line= 4
2248640.04724445506031.5703342042248796.54952026506175.281558621
2248830.40818569506280.6196288742248999.70151289 506476.24747363
#Sta/Elev= 30
       0 3283.12   114.5 3260.35   131.5 3255.65   145.6 3249.85   154.1 3243.01
   168.5 3228.51   173.9 3226.47   214.5 3228.26   229.6  3226.3   235.5 3225.89
   243.9 3226.34   273.3 3229.35   286.8 3232.43   325.8 3233.19   336.1    3232
   362.5 3232.28   378.7 3235.41     407 3231.69   424.4  3232.5   445.5  3231.8
   463.7 3233.79   477.3 3237.24     497 3238.78   511.9 3238.16   514.8 3237.31
   523.3 3232.06   535.5 3231.47     546 3236.89   560.1 3240.86581.8307 3243.53
#Mann= 5 ,-1,0
       0      .1       0   229.6    .045       0   243.9      .1       0
  262.48     .06       0  373.12      .1       0
Bank Sta=229.6,243.9
XS Rating Curve= 0 ,0
Exp/Cntr(USF)=0,0
Exp/Cntr=0.3,0.1

Type RM Length L Ch R = 1 ,45325   ,214.9,208.1,197.6
XS GIS Cut Line= 4
2248489.61661665 506132.436787082248560.29127697506246.760963436
2248791.28261674506553.7461967452248893.51807394506653.072402211
#Sta/Elev= 30
       0 3275.18   111.4 3248.41   126.6 3242.35   147.4 3229.17   152.4  3227.5
   167.4 3224.26   194.1 3223.25   204.6 3220.91   227.4 3219.28   237.5 3220.81
   244.6 3219.87   252.6 3218.79  259.63 3219.93   272.6 3224.34   292.6 3220.79
   322.6 3223.71   350.3 3223.06   373.1 3224.73     456    3223   464.5 3226.01
   493.5 3226.12   519.8 3229.37   529.3  3225.4   546.5 3225.43   558.4 3226.67
   580.9  3231.9   625.8  3236.2   636.9 3239.65   648.9 3245.55   661.1  3246.9
#Mann= 7 ,-1,0
       0      .1       0   244.6    .045       0  259.63      .1       0
  324.41     .06       0  344.41     .07       0  464.41     .08       0
  484.41      .1       0
#XS Ineff= 2 , 0
                           272.9         3227.32
Permanent Ineff=
       F       F
Bank Sta=244.6,259.63
XS Rating Curve= 0 ,0
Exp/Cntr=0.3,0.1

Type RM Length L Ch R = 1 ,45117   ,218.3,223.4,231.9
XS GIS Cut Line= 3
2248327.79510763506363.3852555022248580.60647624506543.964804508
2248764.94809918506747.869211926
#Sta/Elev= 30
       0  3254.7      30  3245.9    73.2 3219.92      84 3215.61    92.6 3215.02
   103.7 3215.97   113.4  3215.1   123.4 3216.92     143 3217.18   153.5 3216.42
   162.1 3214.62   182.2 3213.72   187.9 3214.61   226.6 3215.12   314.1 3219.22
   356.5 3216.85   382.4 3220.04   396.2 3223.39     404  3224.1   435.3 3223.59
   441.5 3220.18   444.3 3220.04   469.8 3220.19   484.9  3224.1   498.1  3222.7
   506.9 3222.93   517.2 3221.37   530.7  3221.7     555 3226.53585.5605 3234.28
#Mann= 5 ,-1,0
       0      .1       0   162.1    .045       0   187.9      .1       0
     310     .06       0  450.68      .1       0
#XS Ineff= 2 , 0
          132.85 3219.61
Permanent Ineff=
       F       F
Bank Sta=162.1,187.9
XS Rating Curve= 0 ,0
Exp/Cntr(USF)=0,0
Exp/Cntr=0.3,0.1

Type RM Length L Ch R = 1 ,44894   ,340.4,338.5,334.4
XS GIS Cut Line= 4
 2248191.2787834506464.170333481 2248261.5696817506540.385646573
2248496.33602003506793.7665139652248611.33743734506880.234527536
#Sta/Elev= 30
       0  3263.8    13.1 3259.32      34  3254.2    55.8 3246.19    88.4 3225.02
    94.8 3221.94   117.4 3207.83   125.2 3206.82   137.2 3207.83   178.1 3208.58
     191 3206.45   202.9 3208.03   219.3 3206.34   241.1 3209.42   268.4 3210.38
   354.7 3210.29   389.1 3211.68   407.7 3210.18   442.9 3214.06   448.6  3213.4
   454.3 3210.76   468.1 3208.97   483.9 3208.88   488.1 3210.81   494.7  3215.9
     524 3221.91     544 3223.63     559 3226.13     579 3233.06     593 3235.08
#Mann= 5 ,-1,0
       0      .1       0   117.4    .045       0   137.2      .1       0
  273.68     .06       0  423.68      .1       0
#XS Ineff= 2 , 0
                          178.48         3212.31
Permanent Ineff=
       F       F
Bank Sta=117.4,137.2
XS Rating Curve= 0 ,0
Exp/Cntr=0.3,0.1

Type RM Length L Ch R = 1 ,44555   ,214.6,199.8,183.9
XS GIS Cut Line= 3
2247962.12152089506646.2932156112248241.26740706506885.561118043
2248438.40008139506957.792937645
#Sta/Elev= 30
       0    3255    35.2 3246.15    65.9  3235.6    71.2 3232.74    74.4 3230.14
   108.5 3198.52   111.3  3197.9   131.2 3197.78   139.7 3196.56  147.08  3197.8
   153.9 3199.42   187.9 3201.85   213.4 3201.84   233.3 3203.05     290 3202.34
     303 3202.46   318.4 3200.46   334.6 3201.02   341.1 3200.41   360.9 3201.37
   387.8 3200.77   417.6 3203.77   421.9 3203.52   430.4 3199.36   438.9 3199.28
   443.2 3199.86     456  3205.8   464.5 3208.02   509.9  3211.6577.6062 3218.58
#Mann= 6 ,-1,0
       0      .1       0   131.2    .045       0  147.08      .1       0
     290     .06       0  407.66     .07       0  427.66      .1       0
#XS Ineff= 2 , 0
                          233.92         3206.88
Permanent Ineff=
       F       F
Bank Sta=131.2,147.08
XS Rating Curve= 0 ,0
Exp/Cntr(USF)=0,0
Exp/Cntr=0.3,0.1

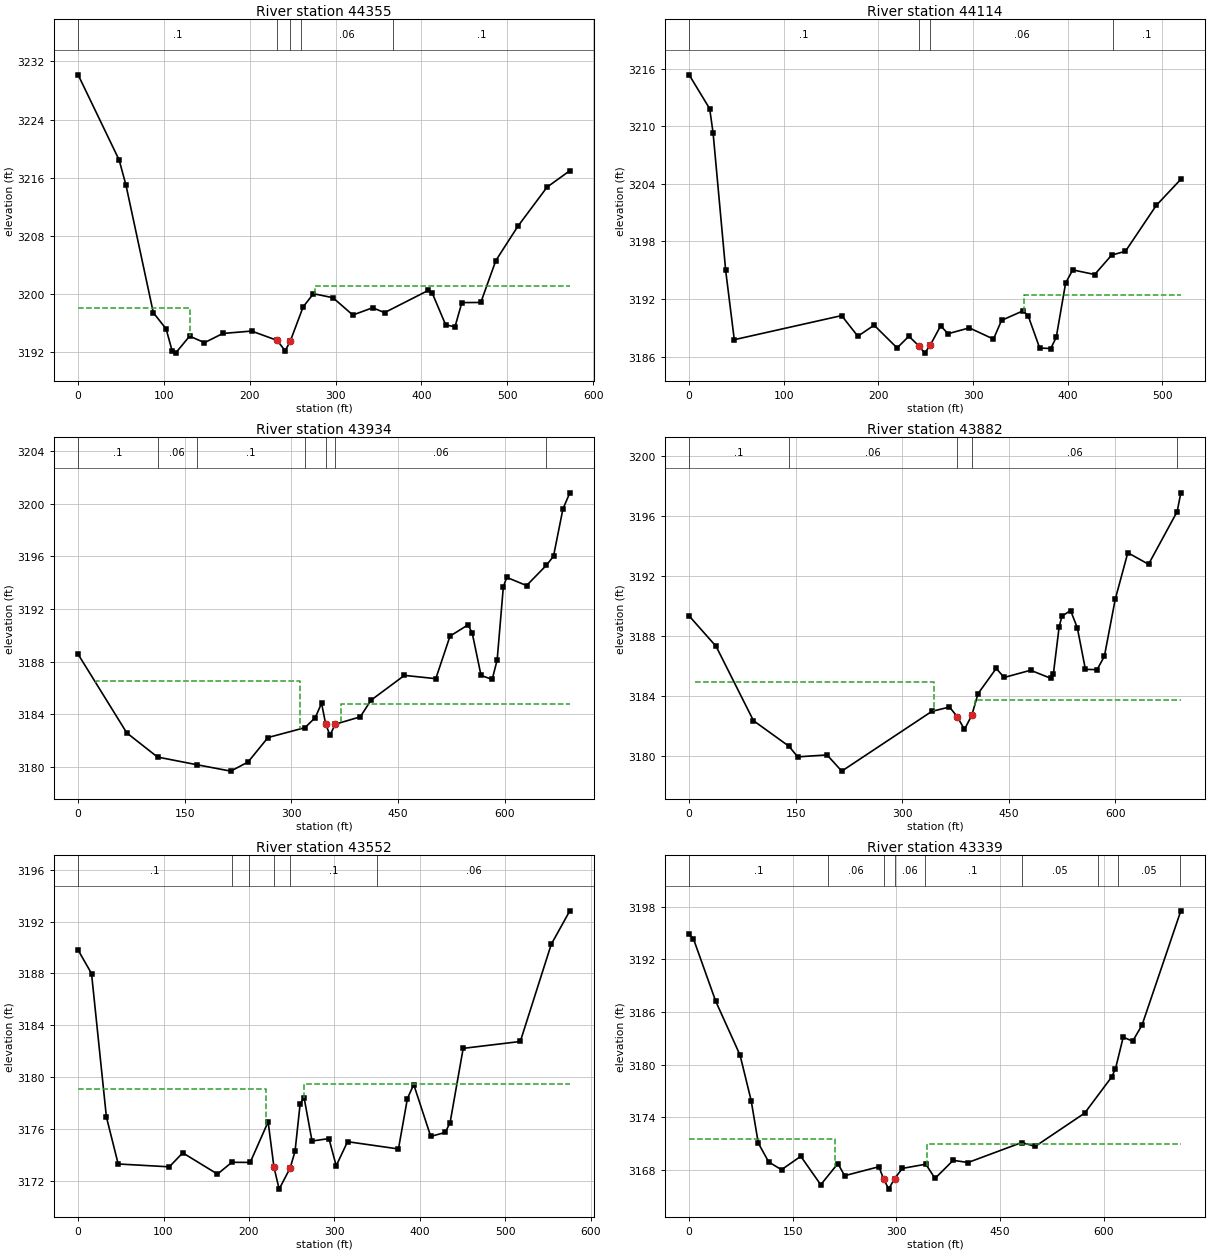
Type RM Length L Ch R = 1 ,44355   ,224.4,241.2,258.3
XS GIS Cut Line= 6
2247865.29182499   506809.3640552247960.53211989506898.430947259
 2248016.2473625506919.9211318422248102.70601042506923.607573706
2248288.81558239507031.7189696252248365.33278041507057.882914756
#Sta/Elev= 30
       0 3230.16    47.8 3218.42    55.7 3214.98    87.6 3197.39   102.5 3195.16
   109.4 3192.18   113.5 3191.82   129.9 3194.16   147.2 3193.26   168.6 3194.53
   202.1 3194.86  231.79 3193.58   241.2 3192.14   247.3 3193.52   262.1 3198.18
   274.1 3200.01   296.9 3199.45     320 3197.07   343.1 3198.07     357  3197.4
   407.9 3200.46   412.5  3200.1   428.1 3195.73     439 3195.43     447 3198.78
   469.1  3198.8   486.6 3204.57   512.3  3209.3   546.3 3214.69   572.8 3216.95
#Mann= 5 ,-1,0
       0      .1       0  231.79    .045       0   247.3      .1       0
  260.11     .06       0  366.65      .1       0
#XS Ineff= 2 , 0
           129.8  3198.1  275.83         3201.12
Permanent Ineff=
       F       F
Bank Sta=231.79,247.3
XS Rating Curve= 0 ,0
Exp/Cntr=0.3,0.1

Type RM Length L Ch R = 1 ,44114   ,209.3,180.5,75.1
BEGIN DESCRIPTION:
xs 4
END DESCRIPTION:
XS GIS Cut Line= 3
2247755.66349292506927.0631891012247998.54388923507175.867497516
2248146.64169186507262.751541725
#Sta/Elev= 30
       0 3215.35    21.7 3211.82    25.3 3209.31    38.6 3194.97    47.7 3187.76
   161.1 3190.27   178.2 3188.12   195.4 3189.27   219.7  3186.9   232.1 3188.12
   242.3 3187.15   248.9 3186.36  254.65 3187.18   265.7 3189.21   273.4 3188.38
     296 3188.99   321.5 3187.82     330 3189.77   352.8 3190.77   358.2 3190.23
   370.3 3186.89     382 3186.84   387.8 3188.01   397.7 3193.66   405.2 3195.03
   428.4 3194.55   446.3 3196.57   460.9 3196.97   493.4 3201.74519.4015 3204.47
#Mann= 4 ,-1,0
       0      .1       0   242.3    .045       0  254.65     .06       0
   447.7      .1       0
#XS Ineff= 2 , 0
                          353.58         3192.39
Permanent Ineff=
       F       F
Bank Sta=242.3,254.65
XS Rating Curve= 0 ,0
Exp/Cntr(USF)=0,0
Exp/Cntr=0.5,0.3

Type RM Length L Ch R = 1 ,43934   ,53.9,51.4,121.7
BEGIN DESCRIPTION:
xs 3
END DESCRIPTION:
XS GIS Cut Line= 6
 2247487.2225129507349.0322245152247650.46910465507292.354840652
2247745.92235488507286.2223686062247891.49801724507178.518286208
2247988.56100032507183.3820897232248112.52434622507256.882480657
#Sta/Elev= 30
       0 3188.57   68.48  3182.6  111.66 3180.77  166.65 3180.19  214.65  3179.7
  238.99 3180.39  267.04 3182.25  319.05    3183  333.67 3183.77  342.41 3184.86
  348.15 3183.29  354.26 3182.41  361.47 3183.26   396.8 3183.82  412.09 3185.09
  459.01 3186.97  503.08 3186.72  523.09 3189.95  548.53 3190.81  554.37 3190.17
  566.71 3186.97   582.4 3186.66   589.4 3188.14  598.08 3193.68  602.86 3194.41
  630.76 3193.79  658.66 3195.33  668.67 3196.02  681.91  3199.6  691.62 3200.83
#Mann= 7 ,-1,0
       0      .1       0  111.66     .06       0  166.65      .1       0
  319.05     .06       0  348.15    .045       0  361.47     .06       0
  658.66      .1       0
#XS Ineff= 3 ,-1
   25.05  312.553186.523  312.55     338    3182     370  691.62 3184.83
Permanent Ineff=
       F       F       F
Bank Sta=348.15,361.47
XS Rating Curve= 0 ,0
Exp/Cntr(USF)=0,0
Exp/Cntr=0.5,0.3

Type RM Length L Ch R = 1 ,43882   ,295.2,330.3,363.4
BEGIN DESCRIPTION:
xs 2
END DESCRIPTION:
XS GIS Cut Line= 6
2247468.57315998507362.7449840172247653.05726104 507300.31569007
2247779.90333372507326.4979188812247918.19782388507216.297218762
2248029.69927882507215.1956917692248094.42350368507257.979501417
#Sta/Elev= 30
       0 3189.32      38 3187.29    90.6 3182.34   140.5 3180.64   152.9 3179.93
   194.2 3180.06   214.9 3178.98   341.7 3182.96   366.6 3183.25   377.5 3182.61
   387.7 3181.76   397.9 3182.69   406.8 3184.14   432.4 3185.82   443.6 3185.22
   480.8  3185.7   508.9 3185.17   512.9 3185.46     521 3188.58   524.9  3189.3
   537.1 3189.68   546.6 3188.53     558 3185.76   574.4 3185.74   584.7 3186.63
     600 3190.43   617.7 3193.53   646.9 3192.76   687.2 3196.27692.3574 3197.52
#Mann= 5 ,-1,0
       0      .1       0   140.5     .06       0   377.5    .045       0
   397.9     .06       0   687.2      .1       0
#XS Ineff= 3 ,-1
    8.28  344.683184.918  344.68   373.5    3182   401.9 692.357  3183.7
Permanent Ineff=
       F       F       F
Bank Sta=377.5,397.9
XS Rating Curve= 0 ,0
Exp/Cntr(USF)=0,0
Exp/Cntr=0.5,0.3

Type RM Length L Ch R = 1 ,43552   ,210.8,213,214.4
BEGIN DESCRIPTION:
xs 1
END DESCRIPTION:
XS GIS Cut Line= 2
2247451.02082781507368.2300878182247888.73211114 507742.31416705
#Sta/Elev= 30
       0  3189.8    15.7 3187.99    33.1 3176.93    46.9  3173.3   106.8 3173.08
   122.5 3174.16   163.2 3172.52     180 3173.43   201.5 3173.42   222.5 3176.55
   229.3 3173.06   235.4 3171.36   248.3 3172.99     254 3174.28     260 3177.95
   264.6 3178.42   273.9 3175.07   293.7 3175.26   302.2 3173.16   315.5 3175.02
   375.1 3174.46   385.6 3178.35     393 3179.43   412.9 3175.43   429.9 3175.73
   435.6  3176.5   450.9 3182.22   517.8 3182.75     554 3190.24575.7865 3192.83
#Mann= 6 ,-1,0
       0      .1       0     180     .06       0     200      .1       0
   229.3    .045       0   248.3      .1       0     350     .06       0
#XS Ineff= 2 , 0
          220.06 3179.11  264.34         3179.45
Permanent Ineff=
       F       F
Bank Sta=229.3,248.3
XS Rating Curve= 0 ,0
Exp/Cntr(USF)=0,0
Exp/Cntr=0.3,0.1

Type RM Length L Ch R = 1 ,43339   ,251.2,251.5,250.8
XS GIS Cut Line= 4
2247240.31575195 507488.426468782247379.98550461 507568.76324975
2247717.81974421507894.5588527492247790.41719297507931.012283173
#Sta/Elev= 30
       0 3194.85     6.3 3194.32    38.5 3187.22    73.7 3181.09    89.8 3175.91
   100.1 3171.07   115.2 3168.92   133.7 3168.04   161.6 3169.57   190.5 3166.33
   215.3 3168.74   225.1 3167.36   274.7 3168.38  281.38 3167.01   288.9 3165.83
   297.3 3167.03   308.7 3168.19   342.6 3168.67   355.9 3167.05   382.2 3169.11
   403.7 3168.86   481.2 3171.13     501  3170.7   572.6 3174.49   611.5 3178.59
   617.1 3179.53   628.3 3183.13     642 3182.68   655.5  3184.5   711.7 3197.52
#Mann= 9 ,-1,0
       0      .1       0  201.13     .06       0  281.38    .045       0
   297.3     .06       0  341.13      .1       0  481.13     .05       0
  591.13     .06       0  621.13     .05       0  710.46      .1       0
#XS Ineff= 2 , 0
          211.83 3171.55  343.89         3170.94
Permanent Ineff=
       F       F
Bank Sta=281.38,297.3
XS Rating Curve= 0 ,0
Exp/Cntr=0.3,0.1

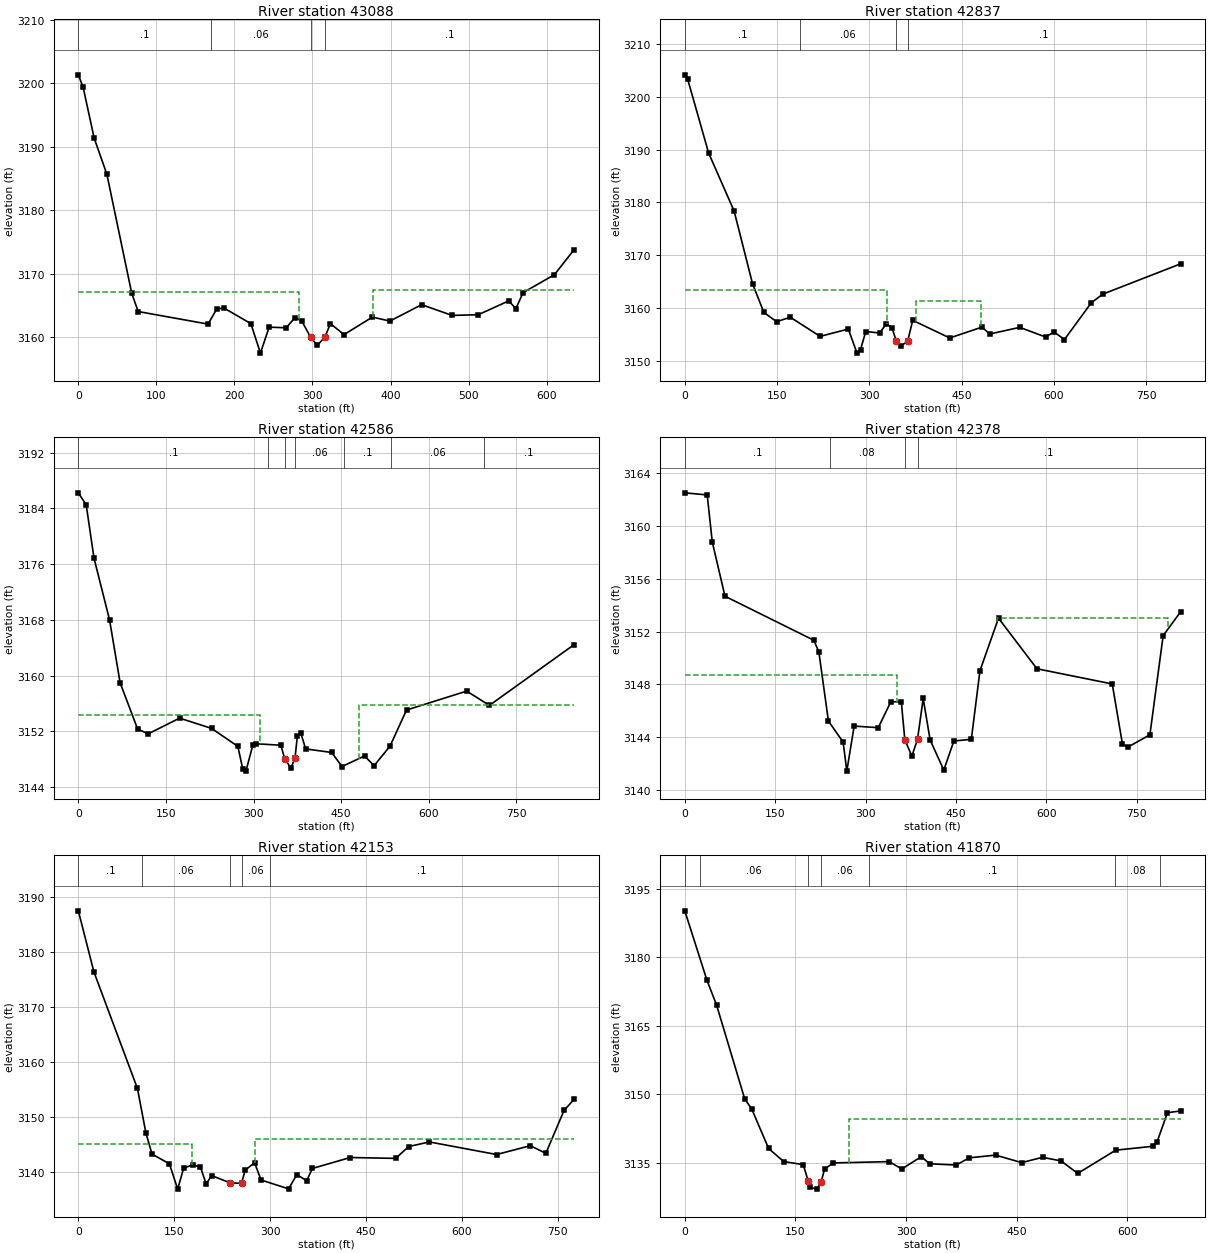
Type RM Length L Ch R = 1 ,43088   ,249,250.6,252.1
XS GIS Cut Line= 2
 2247073.0002713507611.6508926392247528.21121775508054.823202492
#Sta/Elev= 30
       0 3201.31     6.2 3199.32    20.3 3191.34    36.6 3185.63    68.4 3166.91
    76.7 3164.03   166.3 3162.05   177.5 3164.48   187.2 3164.54   221.1 3162.12
   233.3 3157.48   244.5 3161.57   266.4 3161.47   277.4 3163.06   286.2 3162.56
   297.5 3160.01   306.1 3158.69  315.98 3160.02     323 3162.12   340.5  3160.4
   376.7 3163.15   399.3 3162.53   439.9 3165.11   478.9 3163.42   512.5 3163.53
   551.5 3165.71   560.6 3164.49   569.9 3167.01     610 3169.83635.3099 3173.79
#Mann= 4 ,-1,0
       0      .1       0     170     .06       0   297.5    .045       0
  315.98      .1       0
#XS Ineff= 2 , 0
          282.56 3167.12   378.2         3167.41
Permanent Ineff=
       F       F
Bank Sta=297.5,315.98
XS Rating Curve= 0 ,0
Exp/Cntr(USF)=0,0
Exp/Cntr=0.3,0.1

Type RM Length L Ch R = 1 ,42837   ,252.8,250.8,248.4
XS GIS Cut Line= 3
2246916.19980334507704.7418647022246951.10907572507817.060129634
     2247410.828      508329.201
#Sta/Elev= 30
       0 3204.17     4.6 3203.38    38.7 3189.37    80.2 3178.36   110.1 3164.61
   128.5 3159.17   149.2 3157.43   171.5 3158.27   219.9 3154.64   265.7 3156.03
   279.9 3151.47   285.6 3152.14   294.1 3155.56   316.8 3155.28   327.4 3157.03
   336.6 3156.31   343.5 3153.83   350.7 3152.78   362.1 3153.71   370.4 3157.68
   430.6 3154.34   483.3 3156.41   495.2 3155.08   544.4 3156.35   586.3 3154.52
     600 3155.47     617 3154.05   660.7 3161.01   679.3 3162.64   805.8 3168.38
#Mann= 4 ,-1,0
       0      .1       0  187.62     .06       0   343.5    .045       0
   362.1      .1       0
#XS Ineff= 2 ,-1
       0  328.583163.458  375.42  481.73 3161.27
Permanent Ineff=
       F       F
Bank Sta=343.5,362.1
XS Rating Curve= 0 ,0
Exp/Cntr=0.3,0.1

Type RM Length L Ch R = 1 ,42586   ,213,208.1,203.3
XS GIS Cut Line= 4
2246720.87015074507881.015386573  2246801.378533508048.051469404
2247108.36376631508333.9690886632247352.14615747508339.235992176
#Sta/Elev= 30
       0 3186.25    13.5 3184.52    26.8 3176.88    53.5 3167.99    71.5 3158.98
   101.5 3152.34   119.5 3151.64   173.4  3153.9   228.2 3152.42   273.1 3149.84
   281.6 3146.54   286.9 3146.29   298.6    3150     304 3150.22   346.7 3150.01
   353.2  3148.1   363.7 3146.72  370.89 3148.13     375 3151.38   380.6 3151.83
   389.1 3149.48   433.6 3148.97   451.4 3146.95   489.9 3148.47   506.3 3147.07
   533.5 3149.87   561.8 3155.06   664.8 3157.78   703.7 3155.73848.7751 3164.46
#Mann= 7 ,-1,0
       0      .1       0  325.43     .06       0   353.2    .045       0
  370.89     .06       0  455.43      .1       0  535.43     .06       0
  694.94      .1       0
#XS Ineff= 2 , 0
          310.99 3154.32  480.07         3155.85
Permanent Ineff=
       F       F
Bank Sta=353.2,370.89
XS Rating Curve= 0 ,0
Exp/Cntr(USF)=0,0
Exp/Cntr=0.3,0.1

Type RM Length L Ch R = 1 ,42378   ,223.7,225.1,225.1
XS GIS Cut Line= 5
2246626.85115048508005.866932351 2246699.0501219508224.868944472
2246777.21126691508314.8924310492246921.76489901508404.696078691
2247154.43519297508598.833073938
#Sta/Elev= 30
       0  3162.5    37.2 3162.34    45.6 3158.78    66.7 3154.67   214.1 3151.34
   222.5 3150.46   238.4 3145.22   262.8 3143.63   268.9 3141.43   281.1 3144.84
   321.1 3144.72   342.1 3146.69   359.4 3146.67   365.2 3143.81   376.9 3142.56
   386.3 3143.85   395.7 3146.93   407.2 3143.79   429.9 3141.51   446.6 3143.71
   475.6 3143.84   489.9 3149.03   520.7 3153.01   584.5 3149.18   709.5 3148.03
   726.3 3143.51     735 3143.24     772 3144.18     794 3151.69     823 3153.49
#Mann= 4 ,-1,0
       0      .1       0   240.6     .08       0   365.2    .045       0
   386.3      .1       0
#XS Ineff= 2 ,-1
       0  351.55 3148.67  518.27  802.33 3152.99
Permanent Ineff=
       F       F
Bank Sta=365.2,386.3
XS Rating Curve= 0 ,0
Exp/Cntr=0.3,0.1

Type RM Length L Ch R = 1 ,42153   ,279,282.6,277.4
XS GIS Cut Line= 4
2246426.67596881508335.4739182382246584.68307419508420.496789229
2246810.40751045508555.1790361962247139.96518739508607.848071323
#Sta/Elev= 30
       0 3187.41    24.4  3176.3    92.5 3155.11   105.7 3147.05   115.3 3143.18
   142.5 3141.42   155.5 3136.81   164.8 3140.62   178.9 3141.23   191.2  3140.8
     200 3137.77   208.7 3139.27   237.9 3137.93   255.4 3137.88   261.2 3140.26
   275.8 3141.62     286 3138.47   329.1 3136.86   341.9 3139.43   357.5 3138.35
   366.3 3140.57   425.7 3142.56   496.7  3142.4     517 3144.55   549.4 3145.39
   654.7  3143.1   707.4 3144.71   731.7 3143.32   760.2 3151.13776.0212 3153.13
#Mann= 5 ,-1,0
       0      .1       0     100     .06       0   237.9    .045       0
   255.4     .06       0  299.43      .1       0
#XS Ineff= 2 , 0
          178.48    3145  276.28          3145.9
Permanent Ineff=
       F       F
Bank Sta=237.9,255.4
XS Rating Curve= 0 ,0
Exp/Cntr(USF)=0,0
Exp/Cntr=0.3,0.1

Type RM Length L Ch R = 1 ,41870   ,259.9,261,261.9
XS GIS Cut Line= 3
2246298.41361297508527.0092181292246576.40651153  508693.6233571
2246827.69176193508934.890414788
#Sta/Elev= 30
       0 3190.17      30    3175    43.1 3169.56    81.3 3148.99    90.7 3146.85
   113.7 3138.17   134.1 3135.31   160.6 3134.64   167.6 3130.95   169.9 3129.67
   179.3 3129.28     185 3130.92   189.5 3133.62   201.1 3135.01   277.2  3135.3
   294.4 3133.68   320.7 3136.39   332.1 3134.82   368.1 3134.55   385.9 3136.13
   421.6 3136.72   456.9 3135.08   485.2 3136.24   510.3 3135.45     533 3132.72
   584.4  3137.8   635.3 3138.66   640.5 3139.59   654.6    3146   672.5 3146.39
#Mann= 7 ,-1,0
       0      .1       0      20     .06       0   167.6    .045       0
     185     .06       0     250      .1       0   584.1     .08       0
   644.1     .06       0
#XS Ineff= 2 , 0
                          223.21         3144.52
Permanent Ineff=
       F       F
Bank Sta=167.6,185
XS Rating Curve= 0 ,0
Exp/Cntr=0.3,0.1

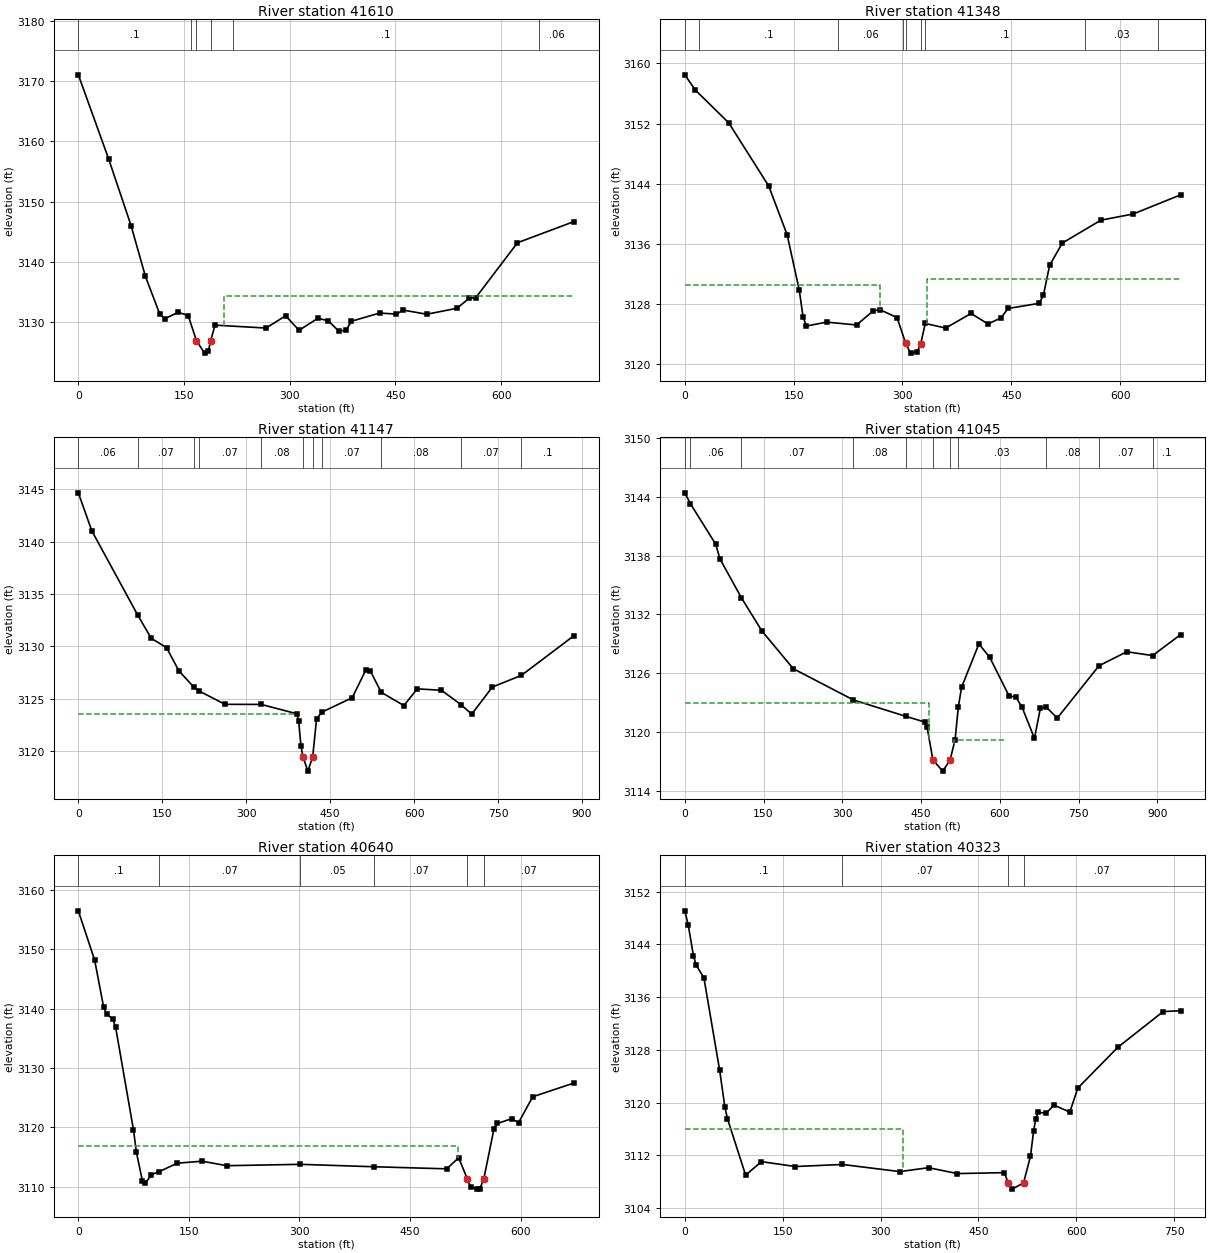
Type RM Length L Ch R = 1 ,41610   ,262.2,261.1,259.8
XS GIS Cut Line= 3
2246181.38874808508752.3117105272246671.21077476509069.830750863
2246723.87980989509177.426065479
#Sta/Elev= 30
       0 3171.05    43.1 3157.07    74.8 3146.05    95.2 3137.62   115.4 3131.41
   122.5 3130.58   141.6 3131.66   155.9 3131.13   167.5 3126.98   179.1 3124.89
   184.5  3125.2   187.7 3126.95     194 3129.53   266.3 3129.05   294.1 3131.08
   313.2 3128.68   339.9 3130.67   354.6 3130.26   369.3 3128.56   379.9 3128.68
   387.3 3130.17   427.6 3131.54   451.4 3131.36   460.9 3132.03   494.3 3131.34
   537.2 3132.33     555 3134.03   563.7 3134.05   623.1  3143.2703.5275 3146.72
#Mann= 6 ,-1,0
       0      .1       0     160     .06       0   167.5    .045       0
   187.7     .06       0     220      .1       0  653.73     .06       0
#XS Ineff= 2 , 0
                          207.32          3134.4
Permanent Ineff=
       F       F
Bank Sta=167.5,187.7
XS Rating Curve= 0 ,0
Exp/Cntr(USF)=0,0
Exp/Cntr=0.3,0.1

Type RM Length L Ch R = 1 ,41348   ,190.5,201.3,219.4
BEGIN DESCRIPTION:
xs 4
END DESCRIPTION:
XS GIS Cut Line= 4
2246007.05008912 508855.90665915 2246053.4782342508989.322368598
2246416.89457658 509201.503338682246536.67632827509220.370202947
#Sta/Elev= 30
       0 3158.47    14.5 3156.45    60.6 3152.09   115.7 3143.69   141.1 3137.21
   157.8 3129.85   162.9 3126.37   167.5  3125.1   195.3 3125.63   236.7 3125.25
     260 3127.15   269.4 3127.26   292.6 3126.22  304.43  3122.8   311.1 3121.51
   320.4 3121.71     325 3122.71   331.4 3125.45   359.5 3124.84   394.5 3126.78
   417.7 3125.39   435.6 3126.17   445.5 3127.44   488.2 3128.12   494.1 3129.17
   502.8 3133.18   520.4 3136.14   573.5 3139.17     618 3139.99   683.3 3142.53
#Mann= 9 ,-1,0
       0     .06       0      20      .1       0  211.26     .06       0
  301.26     .08       0  304.43    .045       0     325     .08       0
  331.26      .1       0  551.26     .03       0  652.09      .1       0
#XS Ineff= 2 , 0
          269.35  3130.6  333.72         3131.41
Permanent Ineff=
       F       F
Bank Sta=304.43,325
XS Rating Curve= 0 ,0
Exp/Cntr=0.5,0.3

Type RM Length L Ch R = 1 ,41147   ,79.6,102.3,109.9
BEGIN DESCRIPTION:
xs 3
END DESCRIPTION:
XS GIS Cut Line= 6
2245938.35877171508874.9553208942246063.55387329 509150.72683742
2246084.95756735509237.2056596492246109.73514427509257.610722993
2246122.18489225509412.545500173 2246403.0748759509529.292661574
#Sta/Elev= 30
       0 3144.65      24 3141.03   105.8    3133   130.4 3130.75   157.7 3129.86
   179.6 3127.65   206.2  3126.1   215.1 3125.74     262 3124.45   326.9 3124.44
   390.3 3123.55   393.6 3122.86   397.8 3120.43   401.5 3119.42   410.1 3118.07
   418.7 3119.44   425.7 3123.08   435.7 3123.72   489.3 3125.08   513.3 3127.69
   521.5 3127.66   541.1  3125.6   581.6 3124.33   605.5 3125.93   648.8 3125.79
   683.4 3124.43   702.8 3123.51   739.7  3126.1   791.7 3127.22885.8309 3131.02
#Mann= 11 ,-1,0
       0     .06       0   105.8     .07       0   206.2      .1       0
   215.1     .07       0   326.9     .08       0   401.5    .045       0
   418.7     .08       0   435.7     .07       0   541.1     .08       0
   683.4     .07       0   791.7      .1       0
#XS Ineff= 2 , 0
           389.5 3123.57   430.7         3122.56
Permanent Ineff=
       F       F
Bank Sta=401.5,418.7
XS Rating Curve= 0 ,0
Exp/Cntr(USF)=0,0
Exp/Cntr=0.5,0.3

Type RM Length L Ch R = 1 ,41045   ,466.7,405.1,351.9
BEGIN DESCRIPTION:
xs 2
END DESCRIPTION:
XS GIS Cut Line= 6
2245913.33134113508871.3937366882245929.13205167508957.169022466
2246015.65975224509140.7582306232246045.60134629509317.167896876
2246093.91089014509508.6890617232246370.04711716509535.023579286
#Sta/Elev= 30
       0 3144.42    10.8  3143.3    58.8 3139.18    66.9 3137.68   107.5 3133.73
   146.6 3130.33   206.6 3126.46     321 3123.27   421.2 3121.59   457.3 3121.01
   461.3 3120.55  472.55 3117.13   491.3    3116505.26633117.136   514.8 3119.22
   520.9 3122.54   527.1 3124.56   560.1 3128.99   580.8 3127.62   617.9 3123.64
   630.3 3123.59   642.4 3122.51   665.9 3119.35   677.2 3122.42   687.8 3122.58
   709.3 3121.41   788.8 3126.76   841.8 3128.19   890.9  3127.8   944.3 3129.94
#Mann= 11 ,-1,0
       0      .1       0    10.8     .06       0   107.5     .07       0
     321     .08       0   421.2     .07       0  472.55    .045       0
505.2663     .07       0   520.9     .03       0   687.8     .08       0
   788.8     .07       0   890.9      .1       0
#XS Ineff= 3 ,-1
       0     466    3123  512.61  607.32 3119.15  607.32  790.99 3124.42
Permanent Ineff=
       F       F       F
Bank Sta=472.55,505.2663
XS Rating Curve= 0 ,0
Exp/Cntr(USF)=0,0
Exp/Cntr=0.5,0.3

Type RM Length L Ch R = 1 ,40640   ,302.9,316.7,330.1
BEGIN DESCRIPTION:
xs 1
END DESCRIPTION:
XS GIS Cut Line= 3
2245618.27834696509767.338643593 2246128.1485344509687.471309196
2246259.23591071509601.696023419
#Sta/Elev= 30
       0 3156.52    22.2 3148.18    34.3 3140.29    38.4 3139.09    46.5 3138.33
    50.5 3136.96    74.8 3119.61    78.8 3115.81    86.9 3111.01      91 3110.59
    99.1 3112.03   110.1 3112.57   134.1 3113.97   167.9 3114.31   201.3 3113.55
   301.1 3113.78   401.7 3113.37   499.9 3113.02   516.1  3114.9   527.6 3111.37
   532.2 3109.96   540.9  3109.6   544.8 3109.67  550.18 3111.35   563.9 3119.73
   568.7 3120.67   587.8 3121.47   597.4 3120.82   616.5 3125.17672.7442  3127.5
#Mann= 6 ,-1,0
       0      .1       0   110.1     .07       0   301.1     .05       0
   401.7     .07       0   527.6    .045       0  550.18     .07       0
#XS Ineff= 2 , 0
          515.12 3116.95
Permanent Ineff=
       F       F
Bank Sta=527.6,550.18
XS Rating Curve= 0 ,0
Exp/Cntr(USF)=0,0
Exp/Cntr=0.3,0.1

Type RM Length L Ch R = 1 ,40323   ,240.4,233.2,225.8
XS GIS Cut Line= 3
2245682.85080939510000.1408333512246261.85704288509980.503779542
2246438.26495188509942.950738048
#Sta/Elev= 30
       0  3149.1     5.3 3146.93    13.3 3142.26    17.3 3140.89    29.3 3138.92
    53.4 3124.91    61.4 3119.32    65.4 3117.56    93.2    3109   117.4 3111.05
   169.4 3110.31   241.5 3110.62   329.3 3109.54   373.5 3110.13   417.6 3109.24
   489.6 3109.38   495.4 3107.83   501.6 3106.88     519 3107.82   529.6 3111.84
   534.5 3115.74   537.6 3117.47   541.6 3118.56   553.6 3118.37   565.6 3119.63
   589.9 3118.57   602.2 3122.21   663.5  3128.4     733 3133.82   759.7 3133.94
#Mann= 4 ,-1,0
       0      .1       0   241.5     .07       0   495.4    .045       0
     519     .07       0
#XS Ineff= 2 , 0
          334.88 3115.98
Permanent Ineff=
       F       F
Bank Sta=495.4,519
XS Rating Curve= 0 ,0
Exp/Cntr=0.3,0.1