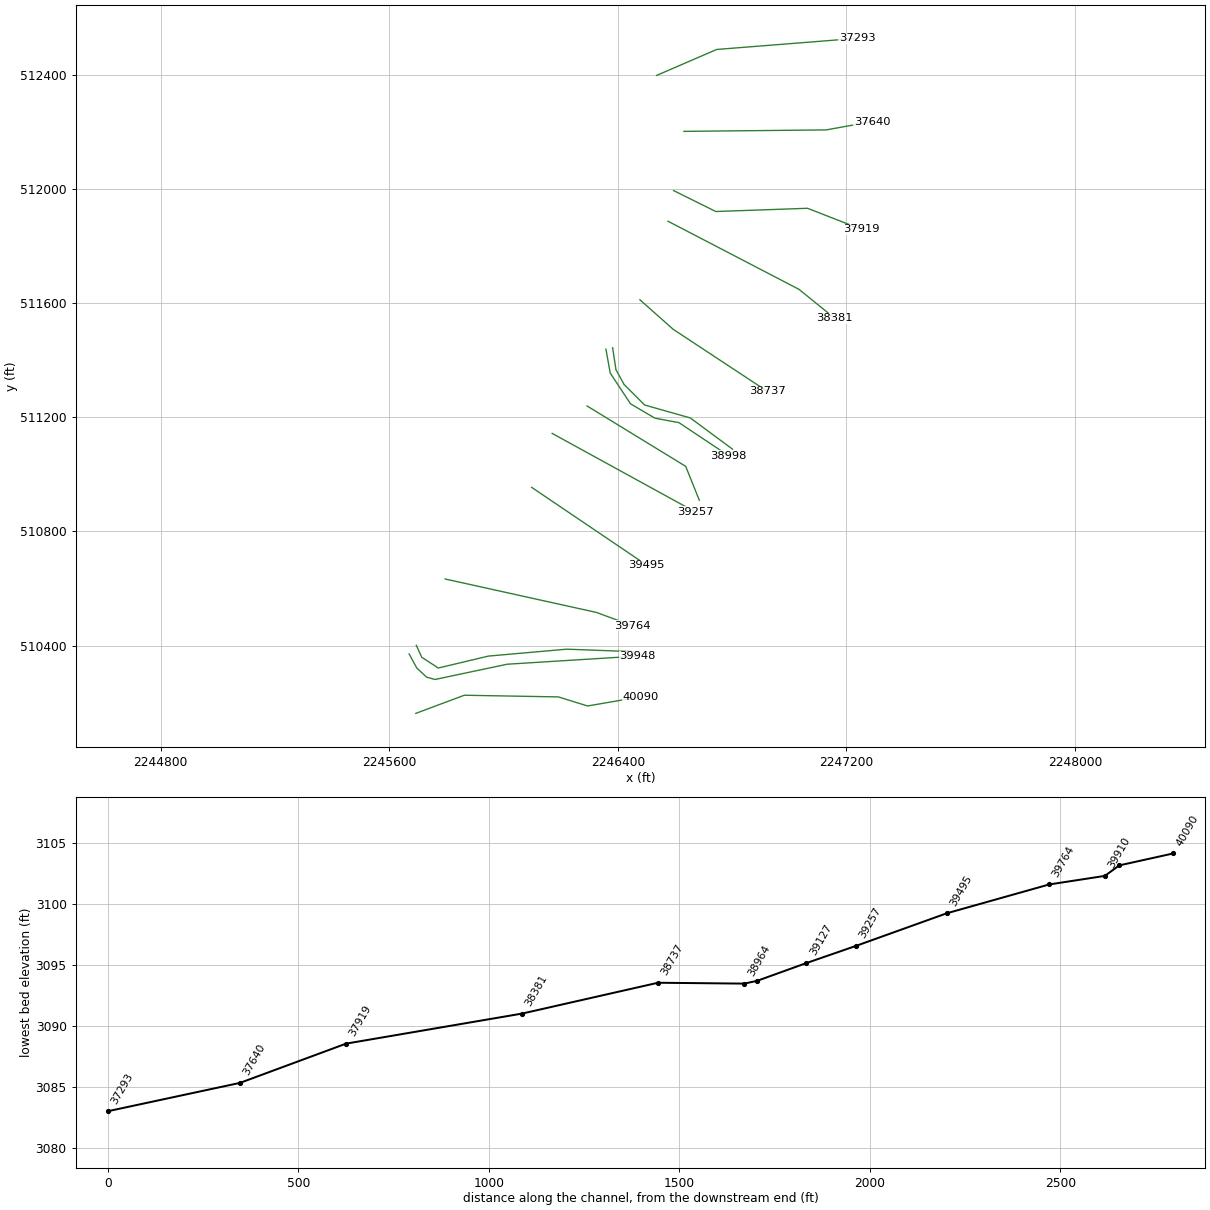
HEC-RAS study BIGSPRFK.prj: BIGSPRFK

--- BIGSPRFK.g01 (geometry) --- (continued)

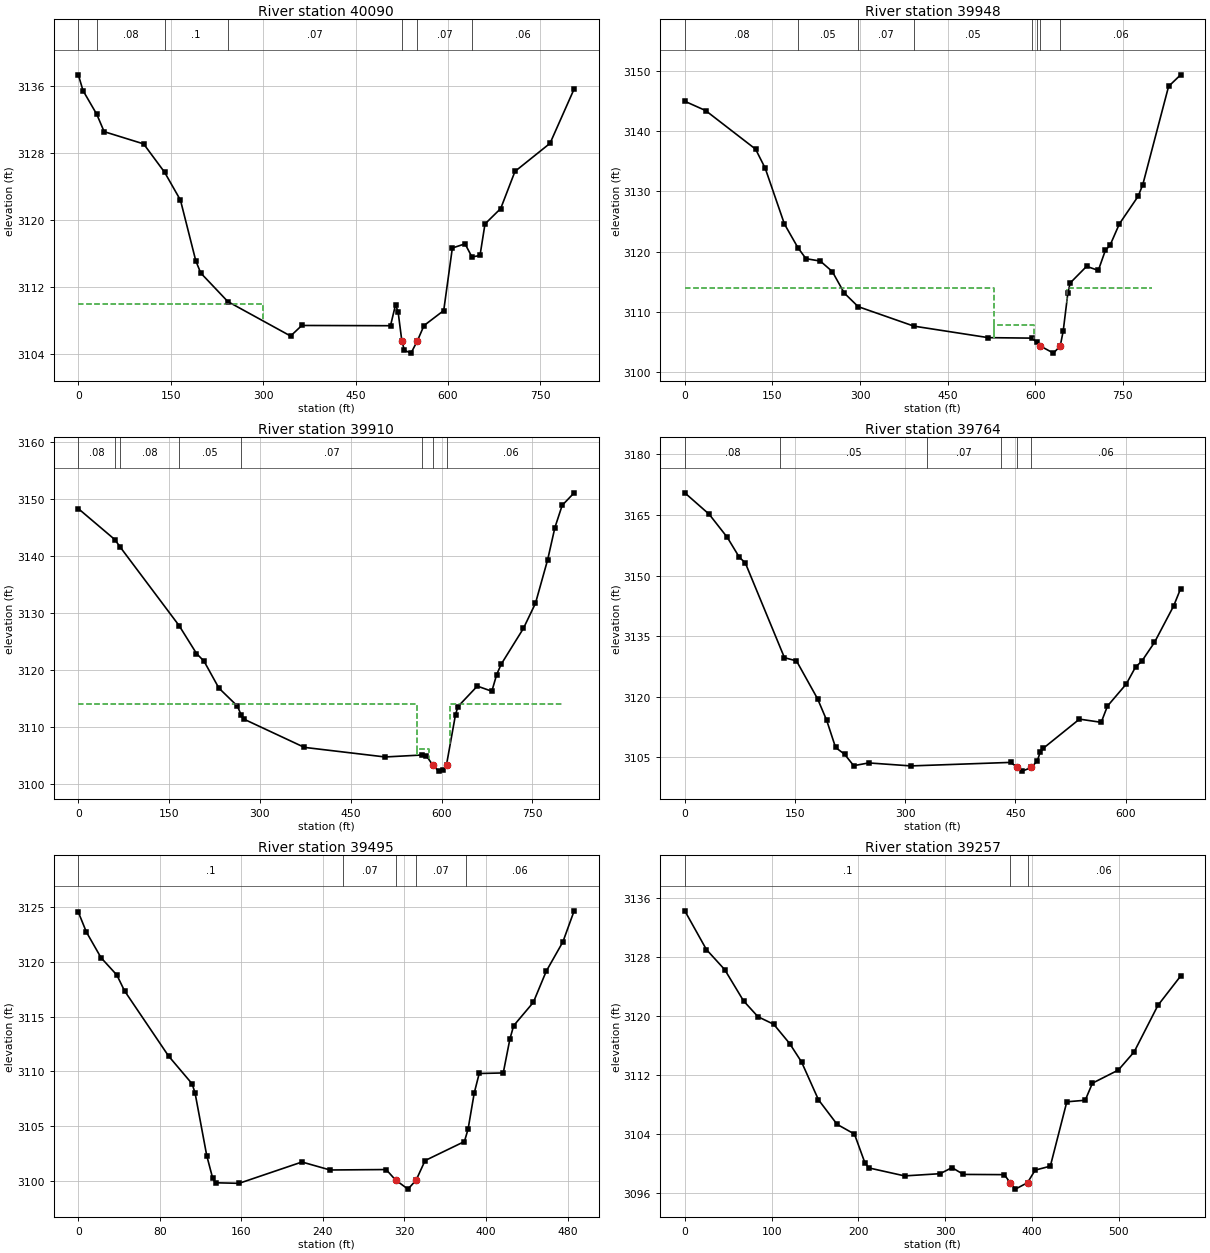
Type RM Length L Ch R = 1 ,40090   ,130,142.2,152.2
BEGIN DESCRIPTION:
xs 4
END DESCRIPTION:
XS GIS Cut Line= 5
2245692.94270127510162.6624706952245862.65403668510226.199719419
2246192.04451033510220.3476044052246294.03851486510188.578980043
2246478.79814602510220.347604405
#Sta/Elev= 30
       0 3137.33     7.6 3135.45      30 3132.61    41.9 3130.55     106 3129.09
   140.1  3125.7   165.8 3122.38   190.7 3115.14   198.7 3113.69   242.7 3110.28
   344.6 3106.17   362.8 3107.43   506.8  3107.4     515 3109.91   519.2 3109.02
  525.18  3105.6   529.3 3104.47   540.1 3104.13  550.49 3105.61   561.2 3107.42
   593.2 3109.21   607.2 3116.67   627.8 3117.17     639  3115.6   652.1 3115.78
   660.2 3119.54   685.7 3121.38   708.9 3125.81   765.8 3129.16804.9556 3135.65
#Mann= 7 ,-1,0
       0      .1       0      30     .08       0   140.1      .1       0
   242.7     .07       0  525.18    .045       0  550.49     .07       0
     639     .06       0
#XS Ineff= 2 , 0
             299 3109.98
Permanent Ineff=
       F       F
Bank Sta=525.18,550.49
XS Rating Curve= 0 ,0
Exp/Cntr(USF)=0,0
Exp/Cntr=0.5,0.3

Type RM Length L Ch R = 1 ,39948   ,40.1,37.9,36.6
BEGIN DESCRIPTION:
xs 3
END DESCRIPTION:
XS GIS Cut Line= 6
2245669.53424121510370.8305619112245696.28676699510321.505592506
2245730.56344065510289.7369681442245759.82401572510281.376803838
2246013.13699419510334.8818553952246468.76594885510363.306414035
#Sta/Elev= 30
       0 3144.96    35.6 3143.42   121.2 3137.01   137.7 3133.83   170.5 3124.59
   193.7 3120.64   207.4 3118.83     232 3118.43   252.5 3116.69     273 3113.12
   296.7 3110.87   392.2 3107.63   519.5 3105.72   594.3 3105.64   602.8 3104.93
   608.2 3104.35     631 3103.15  642.61 3104.33   647.7  3106.8   655.8 3113.21
   659.8 3114.81   687.8 3117.56   707.8 3116.88   719.9 3120.21   727.9 3121.05
   743.9 3124.61     776 3129.19     784 3131.14   828.1 3147.43848.7173 3149.35
#Mann= 8 ,-1,0
       0     .08       0   193.7     .05       0   296.7     .07       0
   392.2     .05       0   594.3     .07       0   602.8     .06       0
   608.2    .045       0  642.61     .06       0
#XS Ineff= 3 ,-1
       0     530    3114     530     597 3107.84   653.6     800    3114
Permanent Ineff=
       F       F       F
Bank Sta=608.2,642.61
XS Rating Curve= 0 ,0
Exp/Cntr(USF)=0,0
Exp/Cntr=0.5,0.3

Type RM Length L Ch R = 1 ,39910   ,151.7,146,140.8
BEGIN DESCRIPTION:
xs 2
END DESCRIPTION:
XS GIS Cut Line= 6
2245694.61473413510400.9271534122245713.84311204510359.126331882
2245771.52824575510321.5055925062245947.09169617510363.306414035
 2246221.3050854510387.5508905222246467.92993242510378.354709786
#Sta/Elev= 30
       0 3148.26    60.4 3142.83    68.8 3141.58   166.5 3127.77   195.2 3122.89
   207.6 3121.55   232.2 3116.83   262.8 3113.68   269.2 3112.07   273.4  3111.4
   373.4 3106.45   506.8 3104.77     567 3105.11   575.1 3104.96   585.4 3103.37
   595.1 3102.29   603.1 3102.41  608.23 3103.41   623.1 3112.19   627.1 3113.59
   659.1 3117.18   683.1 3116.28   691.1  3119.2   698.6 3121.02   735.2 3127.27
   755.2 3131.69   775.3 3139.31   787.3 3144.95   799.3 3148.84819.0994 3151.03
#Mann= 8 ,-1,0
       0     .08       0    60.4     .05       0    68.8     .08       0
   166.5     .05       0   269.2     .07       0     567     .06       0
   585.4    .045       0  608.23     .06       0
#XS Ineff= 3 ,-1
       0     560    3114     560  579.12  3106.1   614.3     800    3114
Permanent Ineff=
       F       F       F
Bank Sta=585.4,608.23
XS Rating Curve= 0 ,0
Exp/Cntr(USF)=0,0
Exp/Cntr=0.5,0.3

Type RM Length L Ch R = 1 ,39764   ,278.6,268.9,260.1
BEGIN DESCRIPTION:
xs 1
END DESCRIPTION:
XS GIS Cut Line= 3
2245795.77272223510633.3397211142246324.97112279510516.297420832
2246449.53757095 510470.31651715
#Sta/Elev= 30
       0 3170.47    33.2 3165.16    57.8 3159.45    74.2 3154.52    82.3 3153.14
   135.6 3129.67     152 3128.87   180.7 3119.49     193 3114.21   205.2 3107.44
   217.5 3105.76   229.8 3102.94   250.3 3103.62   307.7 3102.88   443.3 3103.75
   452.7 3102.53   459.2 3101.59  471.64 3102.49   479.7 3104.14   483.8 3106.35
   487.9 3107.25   537.1 3114.46   566.7 3113.67   575.2 3117.69   600.8 3123.15
   613.6 3127.41   621.7 3128.74   639.2 3133.45   665.3 3142.48674.7689 3146.75
#Mann= 6 ,-1,0
       0     .08       0     130     .05       0     330     .07       0
     430     .06       0   452.7    .045       0  471.64     .06       0
Bank Sta=452.7,471.64
XS Rating Curve= 0 ,0
Exp/Cntr(USF)=0,0
Exp/Cntr=0.3,0.1

Type RM Length L Ch R = 1 ,39495   ,235.2,237.6,239.9
XS GIS Cut Line= 2
 2246098.4106701510954.3700304592246501.37058965510681.828674088
#Sta/Elev= 30
       0 3124.55     7.9 3122.73    22.3 3120.38    37.8  3118.8    45.3 3117.36
    88.5  3111.4   111.6 3108.86   114.5 3108.03     126 3102.29   131.8 3100.23
   134.6 3099.81   157.7 3099.76   219.4 3101.71     247 3100.98     302 3101.02
   311.2 3100.07   323.4 3099.23  331.42 3100.05   340.2 3101.84   378.8 3103.58
   382.4 3104.72   388.4    3108   393.3  3109.8   416.9 3109.85   423.4 3112.94
   427.1 3114.17   446.4  3116.3   459.1 3119.15   475.4 3121.83486.4725 3124.67
#Mann= 5 ,-1,0
       0      .1       0     260     .07       0   311.2    .045       0
  331.42     .07       0     380     .06       0
Bank Sta=311.2,331.42
XS Rating Curve= 0 ,0
Exp/Cntr(USF)=0,0
Exp/Cntr=0.3,0.1

Type RM Length L Ch R = 1 ,39257   ,131.8,130.6,129.3
XS GIS Cut Line= 2
2246170.30808314511143.3097437712246671.08192506510868.260338109
#Sta/Elev= 30
       0 3134.24    24.9    3129      46 3126.28    67.7 3122.05    84.3 3119.91
   102.5 3118.88   120.8 3116.28   134.5 3113.79     154 3108.67   175.5 3105.34
   195.5 3104.02   207.5 3100.14   212.1 3099.44   253.3 3098.36   294.2 3098.66
   307.9 3099.48   321.1 3098.56   368.2 3098.53  375.08 3097.41   380.9 3096.57
   394.9 3097.44   403.7 3099.14   421.2 3099.68   440.2 3108.39   461.4  3108.6
   469.7 3110.91   499.6 3112.69   517.8 3115.15   545.2 3121.45571.3376 3125.41
#Mann= 3 ,-1,0
       0      .1       0  375.08    .045       0   394.9     .06       0
Bank Sta=375.08,394.9
XS Rating Curve= 0 ,0
Exp/Cntr(USF)=0,0
Exp/Cntr=0.3,0.1

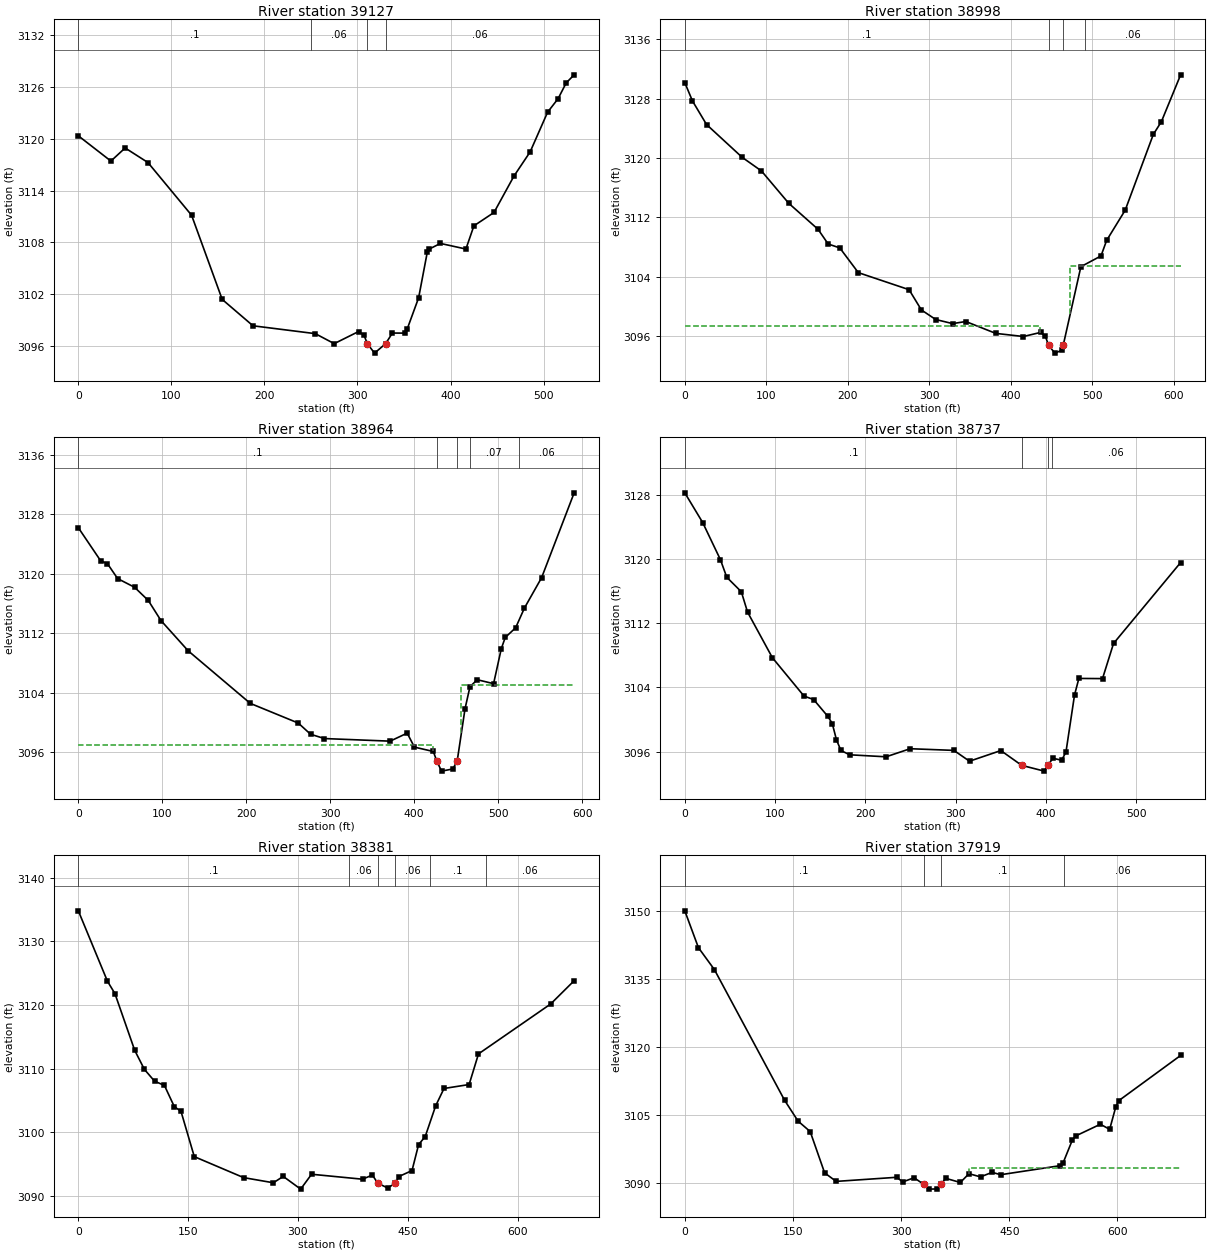
Type RM Length L Ch R = 1 ,39127   ,128.5,129,129.1
BEGIN DESCRIPTION:
xs 4
END DESCRIPTION:
XS GIS Cut Line= 3
  2246292.366482511239.4516332892246637.64126783511027.939476351
2246685.29420438510909.225143207
#Sta/Elev= 30
       0 3120.36      35 3117.43    50.3 3118.95    74.8 3117.26   121.7 3111.15
   154.6 3101.39   187.7 3098.33   254.6 3097.42     275 3096.26   301.1 3097.66
   306.9 3097.26   310.6 3096.25   318.3 3095.16   330.2 3096.25   337.5 3097.49
   350.6 3097.48   353.5 3097.98   365.7 3101.58     375 3106.87   376.8 3107.21
   389.1 3107.88   416.5 3107.23   425.1 3109.92   446.7 3111.47   468.2  3115.7
   485.5 3118.49   504.3  3123.1   515.6 3124.67   524.3  3126.5532.8314 3127.43
#Mann= 4 ,-1,0
       0      .1       0     250     .06       0   310.6    .045       0
   330.2     .06       0
Bank Sta=310.6,330.2
XS Rating Curve= 0 ,0
Exp/Cntr(USF)=0,0
Exp/Cntr=0.5,0.3

Type RM Length L Ch R = 1 ,38998   ,34.2,33.7,33.6
BEGIN DESCRIPTION:
xs 3
END DESCRIPTION:
XS GIS Cut Line= 6
2246358.41178002511438.4235437682246373.46007577511354.821900709
2246444.52147237511246.9757811642246529.79514829511196.814795329
2246614.23280778511180.9304831482246787.28820891511065.560215727
#Sta/Elev= 30
       0 3130.17     9.4  3127.7    26.7 3124.52    70.4  3120.1    94.1 3118.26
   127.5 3113.91   163.5  3110.4   175.9 3108.42   190.2 3107.89   212.9 3104.56
   275.2 3102.26   290.3 3099.53   307.9 3098.24   328.6 3097.69   344.8 3097.97
   381.6 3096.37   415.5 3095.95   436.5  3096.5   442.3 3096.01  446.32 3094.79
     454 3093.71   462.6 3094.09  464.43 3094.81     486 3105.36   510.7 3106.81
   517.6  3108.9   540.4 3112.98   574.9 3123.19   584.8 3124.91   608.4 3131.22
#Mann= 4 ,-1,0
       0      .1       0  446.32    .045       0  464.43      .1       0
  491.45     .06       0
#XS Ineff= 2 , 0
             436 3097.36     473          3105.4
Permanent Ineff=
       F       F
Bank Sta=446.32,464.43
XS Rating Curve= 0 ,0
Exp/Cntr(USF)=0,0
Exp/Cntr=0.5,0.3

Type RM Length L Ch R = 1 ,38964   ,227.9,226.7,225.6
BEGIN DESCRIPTION:
xs 2
END DESCRIPTION:
XS GIS Cut Line= 6
2246381.82024007511443.439642351 2246393.5244701511366.526130738
2246421.94902874511314.6931120412246493.84644177511242.795699011
2246653.52558001511197.6508117592246801.50048823511088.132659353
#Sta/Elev= 30
       0 3126.21    26.6 3121.76    34.7 3121.37    46.8 3119.37      67  3118.2
    83.3 3116.43    98.4 3113.73   130.8 3109.66   204.8 3102.59     262 3099.94
   276.6 3098.44   293.1 3097.86   371.4 3097.51   391.7 3098.59   400.3 3096.71
   422.8 3096.12  426.96 3094.84   432.6 3093.48   446.1 3093.77   451.3 3094.87
   460.6 3101.87   466.5 3104.84   475.2 3105.77   494.6 3105.24   503.8 3109.95
   508.5 3111.45   520.9 3112.76   531.3  3115.4   551.8 3119.49 590.576  3130.9
#Mann= 5 ,-1,0
       0      .1       0  426.96    .045       0   451.3      .1       0
  466.01     .07       0  524.44     .06       0
#XS Ineff= 2 , 0
             422    3097   456.3            3105
Permanent Ineff=
       F       F
Bank Sta=426.96,451.3
XS Rating Curve= 0 ,0
Exp/Cntr(USF)=0,0
Exp/Cntr=0.5,0.3

Type RM Length L Ch R = 1 ,38737   ,352.5,356.4,358.7
BEGIN DESCRIPTION:
xs 1
END DESCRIPTION:
XS GIS Cut Line= 3
2246477.35415182511611.3045961662246594.26622737511507.690849108
2246922.18801671511291.365904103
#Sta/Elev= 30
       0 3128.32    19.8 3124.61    39.4 3119.98    46.5 3117.77    62.6 3115.96
    69.5 3113.42      97 3107.72     132 3102.93   142.7 3102.49   158.5 3100.38
   163.3  3099.5     168 3097.45   172.9 3096.13   182.6 3095.59   222.9 3095.34
   249.6 3096.35     298 3096.14   315.3 3094.79     350 3096.12   373.1 3094.27
   398.1 3093.55   401.9 3094.26   407.7 3095.16   417.3 3094.91   422.1 3095.92
   431.6 3103.06   436.4 3105.13   462.6 3105.11   474.8  3109.5   549.1 3119.61
#Mann= 4 ,-1,0
       0      .1       0   373.1    .045       0   401.9      .1       0
  406.22     .06       0
Bank Sta=373.1,401.9
XS Rating Curve= 0 ,0
Exp/Cntr=0.3,0.1

Type RM Length L Ch R = 1 ,38381   ,397.2,462.1,461.2
XS GIS Cut Line= 3
2246575.83393766511886.470183698 2247034.0947959511648.050683124
2247158.98120097511546.903016213
#Sta/Elev= 30
       0  3134.8    39.8 3123.72      50 3121.78      77 3112.86    90.2 3109.87
   104.1 3108.01   117.6 3107.34   131.1    3104   140.2 3103.27   158.4 3096.14
   225.8 3092.84   266.4 3092.03   279.9 3093.03   303.7 3091.03   318.6 3093.37
   388.2 3092.59   401.7 3093.25  408.98 3091.96   422.4 3091.22   433.2 3091.95
   437.8 3093.01   455.8 3093.95   464.8 3098.04   473.8 3099.29   488.1 3104.13
   499.5 3106.86   533.8 3107.48   546.6  3112.3   645.2 3120.15677.2815 3123.81
#Mann= 6 ,-1,0
       0      .1       0     370     .06       0  408.98    .045       0
   433.2     .06       0     480      .1       0  556.57     .06       0
Bank Sta=408.98,433.2
XS Rating Curve= 0 ,0
Exp/Cntr(USF)=0,0
Exp/Cntr=0.3,0.1

Type RM Length L Ch R = 1 ,37919   ,305.1,278.4,278
XS GIS Cut Line= 4
2246595.44419961511993.8105649092246743.03722377511920.530112351
2247064.02624836511931.8834219022247251.87191548511858.602969345
#Sta/Elev= 30
       0 3150.13    18.9 3141.98      41 3137.14   138.3 3108.25   157.1 3103.61
   173.9  3101.3   193.9 3092.17   209.9 3090.28     294 3091.19   302.2 3090.16
     318 3091.09   331.3 3089.63     338 3088.57     350 3088.61  355.06 3089.62
     362 3090.95   382.1 3090.04   394.1 3091.98   410.1 3091.28   426.1 3092.28
   438.1 3091.76   520.5 3093.76   524.8 3094.45   537.4 3099.41   541.9 3100.32
   576.3 3102.92   589.2  3101.8   597.8 3106.83   602.1 3108.17 687.607 3118.14
#Mann= 4 ,-1,0
       0      .1       0   331.3    .045       0  355.06      .1       0
  525.97     .06       0
#XS Ineff= 2 , 0
                          394.27         3093.28
Permanent Ineff=
       F       F
Bank Sta=331.3,355.06
XS Rating Curve= 0 ,0
Exp/Cntr(USF)=0,0
Exp/Cntr=0.3,0.1

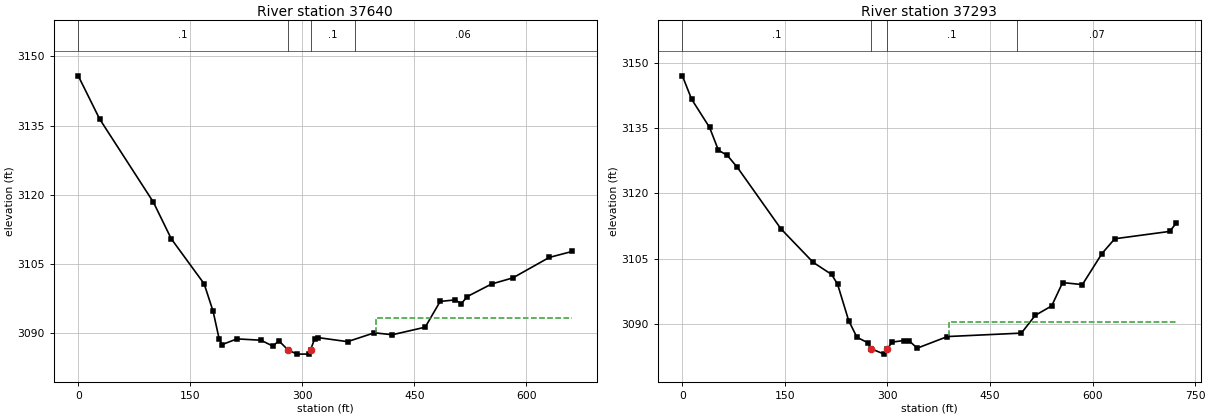
Type RM Length L Ch R = 1 ,37640   ,313.3,347,348.5
XS GIS Cut Line= 3
2246631.56836636 512201.266493982247129.04974851512206.427089231
2247290.06032033512235.326422633
#Sta/Elev= 30
       0  3145.8    28.6 3136.44   100.6 3118.37   124.6  3110.4   168.6 3100.63
   180.6 3094.66   188.6 3088.74   192.6 3087.43   212.6 3088.67   244.6 3088.38
   260.6  3087.1   268.6 3088.25   280.6 3086.33   292.6 3085.36   308.6 3085.37
  311.15 3086.33   316.6 3088.69   320.6 3088.96   360.6 3088.07   396.6 3089.99
   420.6 3089.57   464.6 3091.21   484.6  3096.8   504.7 3097.14   512.9 3096.31
     521 3097.87   553.5 3100.59     582 3101.92   630.7 3106.36661.0917 3107.65
#Mann= 4 ,-1,0
       0      .1       0   280.6    .045       0  311.15      .1       0
     370     .06       0
#XS Ineff= 2 , 0
                           398.7         3093.28
Permanent Ineff=
       F       F
Bank Sta=280.6,311.15
XS Rating Curve= 0 ,0
Exp/Cntr(USF)=0,0
Exp/Cntr=0.3,0.1

Type RM Length L Ch R = 1 ,37293   ,360.8,389.7,410.8
XS GIS Cut Line= 3
2246535.81552422512397.2228573072246746.13358092512488.195589909
  2247237.665619512527.175785647
#Sta/Elev= 30
       0 3147.02    13.5 3141.65    39.8 3135.15    52.7 3129.92    65.8 3128.72
    80.5 3125.96   144.2 3111.84   191.3 3104.14   218.3 3101.36     227 3099.12
   243.2 3090.77   255.3 3086.92   271.3 3085.65   276.6 3084.24   295.2 3083.04
     300 3084.18   306.3 3085.79   323.5 3086.16   331.5 3086.13   343.5 3084.41
   387.7 3087.08   495.9 3087.87   516.1 3091.95   540.2 3094.12   556.2 3099.49
   585.1 3099.02   613.8 3106.17   632.5 3109.56   712.7 3111.25   722.2  3113.1
#Mann= 4 ,-1,0
       0      .1       0   276.6    .045       0     300      .1       0
  489.15     .07       0
#XS Ineff= 2 , 0
                          390.31         3090.38
Permanent Ineff=
       F       F
Bank Sta=276.6,300
XS Rating Curve= 0 ,0
Exp/Cntr=0.3,0.1