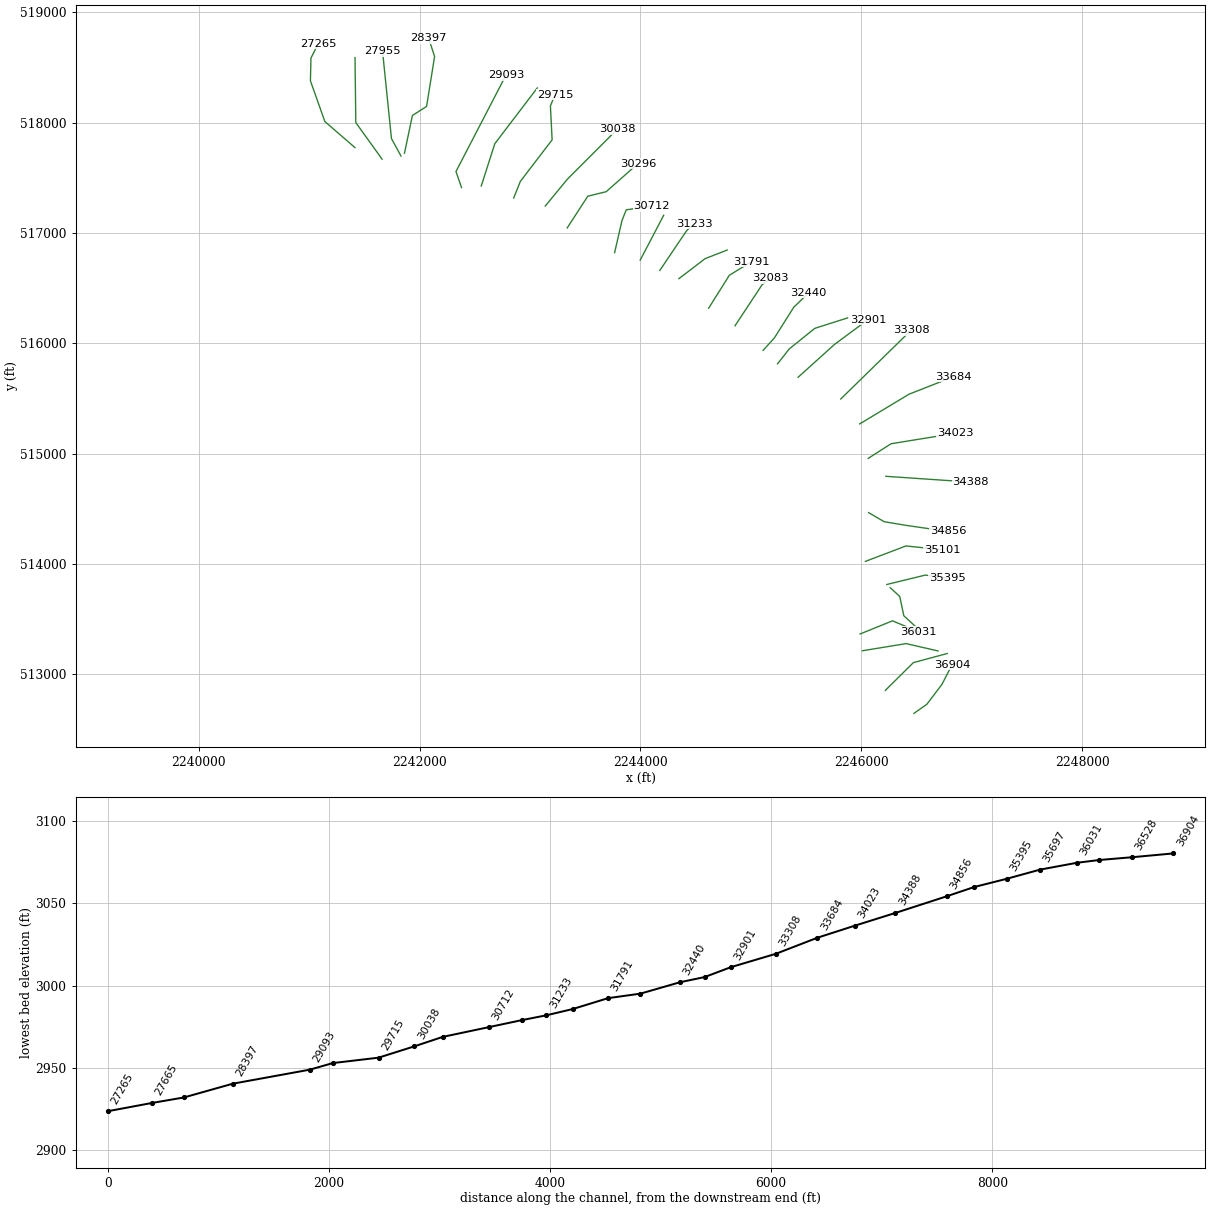
HEC-RAS study BIGSPRFK.prj: BIGSPRFK

--- BIGSPRFK.g01 (geometry) --- (continued)

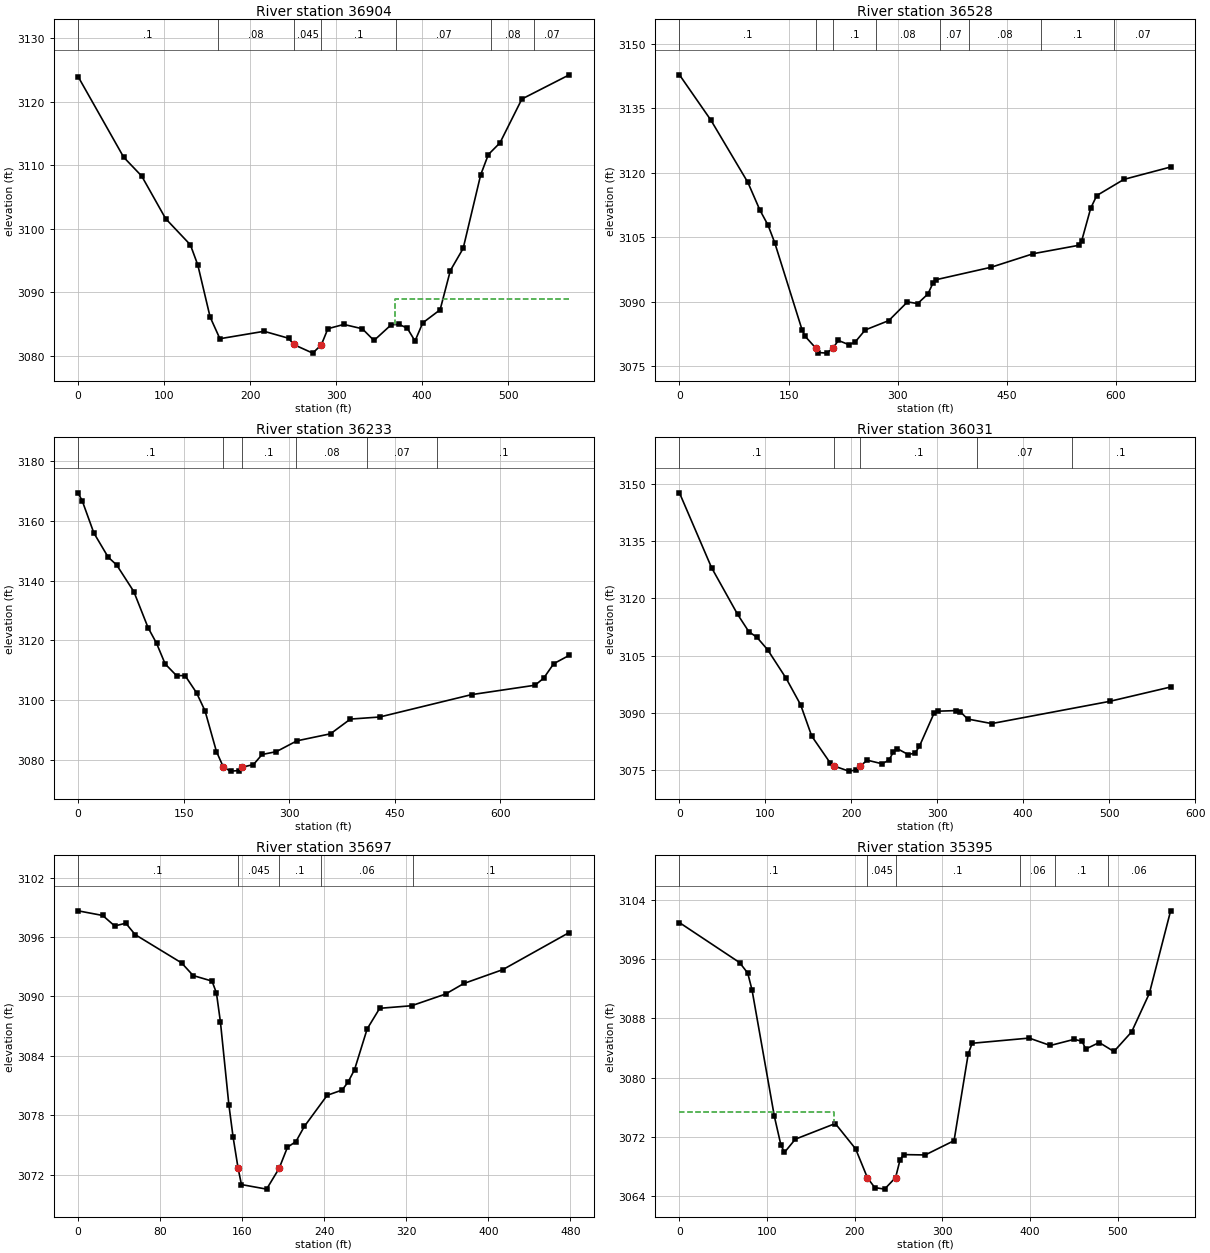
Type RM Length L Ch R = 1 ,36904   ,377.2,375.6,370.9
XS GIS Cut Line= 4
2246476.83166712512646.5159528192246593.37996151512728.679328584
2246731.01376221512909.9855716082246822.51039063513088.888877071
#Sta/Elev= 30
       0 3123.96      53 3111.26      74 3108.28   101.8 3101.58   130.6 3097.45
   139.2 3094.28   153.5 3086.09   164.9 3082.66   216.3 3083.83   244.9 3082.73
   250.6 3081.75   272.9 3080.39   282.9 3081.71   290.5 3084.24     309 3084.91
   330.5 3084.23   344.1 3082.38   364.2 3084.87   373.5 3084.91   382.8 3084.32
   391.8  3082.3   400.8 3085.16     421 3087.22   432.9  3093.4   447.8 3096.89
   468.2 3108.49   477.1 3111.68   490.6 3113.52   516.1 3120.43   571.2 3124.24
#Mann= 7 ,-1,0
       0      .1       0   162.6     .08       0   250.6    .045       0
   282.9      .1       0  370.23     .07       0  480.23     .08       0
  530.23     .07       0
#XS Ineff= 2 , 0
                          368.79         3088.92
Permanent Ineff=
       F       F
Bank Sta=250.6,282.9
XS Rating Curve= 0 ,0
Exp/Cntr=0.3,0.1

Type RM Length L Ch R = 1 ,36528   ,311.3,295.3,277.2
XS GIS Cut Line= 3
2246217.68862727512854.597852697 2246471.5899136513106.434900922
2246778.12927148513189.004424931
#Sta/Elev= 30
       0 3142.82    43.2 3132.28    94.1 3117.77   110.5 3111.37   121.8 3107.82
   130.9 3103.78   168.4 3083.55   172.5 3082.02   187.4 3079.23   191.1  3078.2
   202.5 3078.06  210.86 3079.22   218.5 3081.01   232.7 3080.03   241.2 3080.58
   255.3 3083.45   287.7 3085.63   313.4 3089.98   327.4 3089.59   341.5 3091.82
   348.7 3094.45   352.8 3095.15   428.3 3098.04   486.6 3101.21   548.8 3103.15
   552.9 3104.22   565.3 3111.81   573.6 3114.73   610.9 3118.49675.0791 3121.37
#Mann= 8 ,-1,0
       0      .1       0   187.4    .045       0  210.86      .1       0
     270     .08       0  357.61     .07       0  397.61     .08       0
  497.61      .1       0  597.61     .07       0
Bank Sta=187.4,210.86
XS Rating Curve= 0 ,0
Exp/Cntr(USF)=0,0
Exp/Cntr=0.3,0.1

Type RM Length L Ch R = 1 ,36233   ,194.5,201.5,207.2
XS GIS Cut Line= 3
2246010.04023852513213.9375480692246405.53429439 513278.79878229
2246695.61571399 513212.23569024
#Sta/Elev= 30
       0 3169.26     6.2 3166.38    22.4 3155.86    42.7 3147.81    54.9 3145.16
    79.2 3136.31    99.4 3124.31   111.6 3119.02   123.8 3112.15     140 3108.24
   152.1 3108.27   168.4 3102.53   180.5 3096.48   196.7 3082.93  206.68 3077.66
   216.8 3076.38   229.2 3076.56   233.2 3077.68   249.4 3078.58   261.6 3081.93
   281.9 3082.88   311.1 3086.49   358.9 3088.84   387.2 3093.75   428.8 3094.44
   559.4 3101.91   649.7 3105.05     662  3107.4   676.3 3112.24   698.4 3115.03
#Mann= 6 ,-1,0
       0      .1       0  206.68    .045       0   233.2      .1       0
     310     .08       0  410.78     .07       0  510.78      .1       0
Bank Sta=206.68,233.2
XS Rating Curve= 0 ,0
Exp/Cntr=0.3,0.1

Type RM Length L Ch R = 1 ,36031   ,386.8,334.3,274.2
XS GIS Cut Line= 3
2245989.49742648513366.2739681442246282.93919362513485.155504573
2246517.69260733513385.836752619
#Sta/Elev= 30
       0 3147.69    37.4 3128.05    67.6 3115.84    80.6 3111.32    90.3 3109.76
   102.6 3106.54   124.1 3099.05     141  3092.1   153.9 3083.89   175.5 3076.82
   179.8 3076.05   197.1  3074.7   205.7 3074.99   210.1 3076.03   218.7 3077.56
   235.9 3076.62   243.9 3077.63   248.9 3079.71   253.2 3080.63   266.2 3079.04
   274.1 3079.44   279.1 3081.16   296.4 3089.97   300.7 3090.42   322.3 3090.58
   326.7  3090.3   335.3 3088.37   363.3 3087.17   500.4 3092.99571.5072 3096.76
#Mann= 5 ,-1,0
       0      .1       0   179.8    .045       0   210.1      .1       0
  346.61     .07       0  456.61      .1       0
Bank Sta=179.8,210.1
XS Rating Curve= 0 ,0
Exp/Cntr(USF)=0,0
Exp/Cntr=0.3,0.1

Type RM Length L Ch R = 1 ,35697   ,256.4,301.5,362.5
XS GIS Cut Line= 4
2246261.87157957513785.3690047962246348.39928013513706.365452106
2246385.26760472513531.0528066122246519.94985169513407.656781458
#Sta/Elev= 30
       0 3098.65      24 3098.18    35.7 3097.12    46.5  3097.4    55.6 3096.25
   100.9 3093.39   112.2 3092.11   130.6 3091.55   134.9 3090.35   138.8 3087.42
     147 3079.08   151.1 3075.82  156.04 3072.63   159.3 3070.99   183.8 3070.53
     196 3072.62   204.2 3074.77   212.4 3075.33   220.6 3076.86   242.9 3080.01
   257.4 3080.54   263.2 3081.33   269.6 3082.61   281.9 3086.72   294.1  3088.8
   325.2 3089.06   358.3 3090.24   376.2 3091.31   414.2 3092.71478.9799 3096.46
#Mann= 5 ,-1,0
       0      .1       0  156.04    .045       0     196      .1       0
  237.17     .06       0  326.32      .1       0
Bank Sta=156.04,196
XS Rating Curve= 0 ,0
Exp/Cntr(USF)=0,0
Exp/Cntr=0.3,0.1

Type RM Length L Ch R = 1 ,35395   ,290.3,294.4,298.4
XS GIS Cut Line= 3
2246231.77498807 513814.713181512246580.14303469  513899.7360525
2246780.28536817513874.153949724
#Sta/Elev= 30
       0 3100.91    68.6 3095.52    77.9  3094.1    82.8 3091.83   108.3 3074.76
   115.7 3070.93   119.8  3069.9   132.2 3071.69   177.8  3073.8     201 3070.38
   214.5 3066.47   222.8 3065.16     234 3064.95   246.6 3066.51   251.6 3068.86
   255.7 3069.61   280.4 3069.56   313.3 3071.49   329.4 3083.15   333.9 3084.63
     399 3085.33   423.1 3084.33   450.3 3085.16   459.4  3084.9   463.5 3083.85
   478.9 3084.73   495.7 3083.52   515.9 3086.17   536.1 3091.36 560.364  3102.5
#Mann= 6 ,-1,0
       0      .1       0   214.5    .045       0   246.6      .1       0
  388.59     .06       0  428.59      .1       0  488.59     .06       0
#XS Ineff= 2 , 0
          176.86  3075.4
Permanent Ineff=
       F       F
Bank Sta=214.5,246.6
XS Rating Curve= 0 ,0
Exp/Cntr(USF)=0,0
Exp/Cntr=0.3,0.1

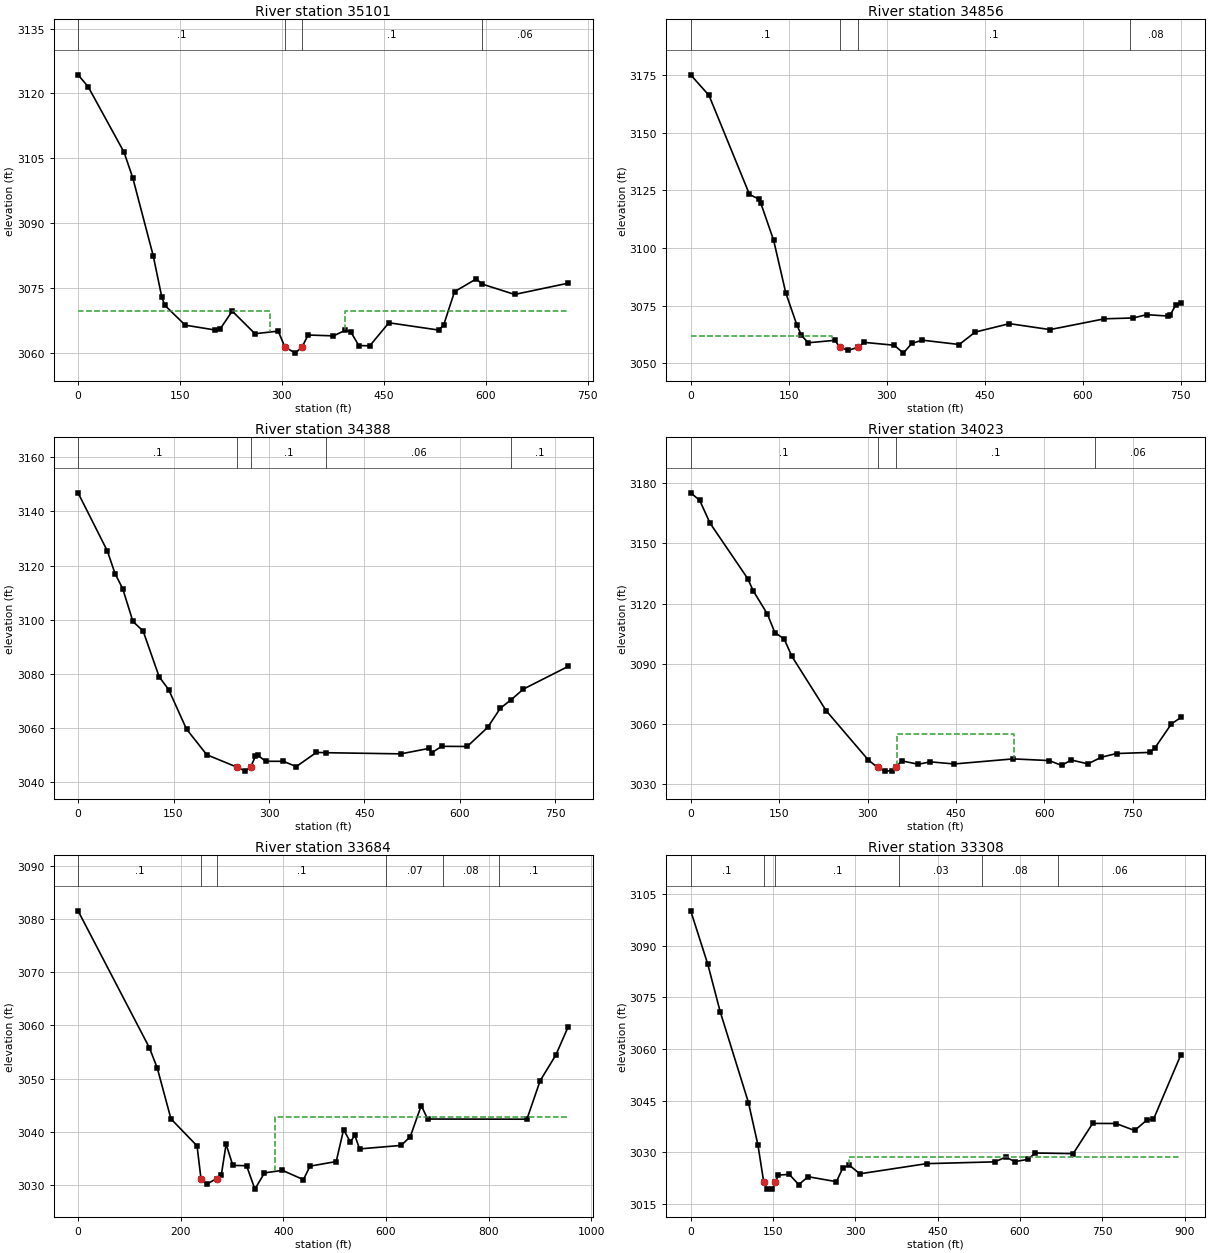
Type RM Length L Ch R = 1 ,35101   ,260.1,245,229.8
XS GIS Cut Line= 3
 2246036.8995581514023.884492442 2246404.8303892514163.833642922
 2246730.6259922514129.974977483
#Sta/Elev= 30
       0 3124.31    14.9 3121.55    67.7  3106.4    80.5 3100.48   110.5 3082.52
   123.3 3072.85   127.6 3071.03   157.6 3066.42     202 3065.29   208.9 3065.49
   226.8 3069.67   260.3 3064.44   294.5 3065.04   304.3 3061.35   319.8 3059.95
   329.9 3061.46   338.4 3064.14   375.8 3063.94   392.9 3065.21     401 3064.92
   413.1  3061.7   429.2 3061.64   457.3 3066.97   530.3 3065.29   537.8 3066.42
   553.9 3074.16     586 3077.13   594.1 3075.94   642.3 3073.52721.1984 3076.13
#Mann= 4 ,-1,0
       0      .1       0   304.3    .045       0   329.9      .1       0
   594.1     .06       0
#XS Ineff= 2 , 0
          282.59  3069.7  393.46          3069.7
Permanent Ineff=
       F       F
Bank Sta=304.3,329.9
XS Rating Curve= 0 ,0
Exp/Cntr(USF)=0,0
Exp/Cntr=0.3,0.1

Type RM Length L Ch R = 1 ,34856   ,464.3,467.8,467.5
XS GIS Cut Line= 4
2246066.39260668514465.7700802262246207.69771487 514383.53876088
2246404.07797441514350.4325102292246788.02148873514295.049971162
#Sta/Elev= 30
       0 3175.06    28.1  3166.1      90 3123.19   103.9 3121.24   107.1 3119.61
     127 3103.31   145.5  3080.6   162.6 3066.56   169.4 3062.19   179.8 3058.88
   220.8 3059.94   228.4 3056.87     241 3055.61   256.2 3056.88   265.4 3059.06
   311.7 3057.81   325.6 3054.39   338.4 3058.57   354.6 3060.01   411.2 3058.13
   435.5  3063.5     488 3067.17   550.2 3064.59   633.5 3069.27   677.7 3069.64
   698.2 3071.07   730.5 3070.46   734.5 3071.07   742.6  3075.2   750.6 3075.99
#Mann= 4 ,-1,0
       0      .1       0   228.4    .045       0   256.2      .1       0
  672.64     .08       0
#XS Ineff= 2 , 0
          217.07 3061.86
Permanent Ineff=
       F       F
Bank Sta=228.4,256.2
XS Rating Curve= 0 ,0
Exp/Cntr=0.3,0.1

Type RM Length L Ch R = 1 ,34388   ,356.9,364.8,366.3
XS GIS Cut Line= 2
2246222.17536346514794.9043853882246990.53065632514742.661322358
#Sta/Elev= 30
       0 3146.84    46.1 3125.36    58.1 3117.04    70.2 3111.47    86.2 3099.38
   102.2 3095.89   127.4 3078.99   142.4 3074.24   170.4 3059.68   202.3 3050.22
  249.26  3045.7   262.6 3044.19   271.3 3045.74   278.6 3049.66   282.7    3050
   294.7 3047.82   322.6 3047.81   342.8 3045.86   374.5  3051.1   390.2 3050.98
   507.2 3050.56   551.3 3052.57   555.3 3050.93   571.3 3053.34   611.4 3053.28
   643.5 3060.32   663.5 3067.42     680 3070.43   699.6 3074.44770.1293 3082.83
#Mann= 5 ,-1,0
       0      .1       0  249.26    .045       0   271.3      .1       0
   390.2     .06       0     680      .1       0
Bank Sta=249.26,271.3
XS Rating Curve= 0 ,0
Exp/Cntr(USF)=0,0
Exp/Cntr=0.3,0.1

Type RM Length L Ch R = 1 ,34023   ,328,339,351.3
XS GIS Cut Line= 3
2246062.88371584514957.3382621172246269.30752586515089.857251266
2246847.80388234 515184.14960893
#Sta/Elev= 30
       0 3175.26    15.3 3171.49    32.7 3160.19    96.6 3132.53   106.1 3126.37
   129.9 3114.92   142.7 3105.56   158.4 3102.46   171.6 3093.74   229.7 3066.65
   300.9 3042.17   316.9 3038.31   329.3  3036.5   341.6  3036.7   348.3 3038.44
   357.6 3041.64     386 3039.93   406.3 3041.13   446.8 3040.07   546.9  3042.6
   607.9 3041.77   629.2 3039.35   645.4 3042.06   673.7 3040.11   696.7 3043.46
   722.4 3045.28   779.1 3045.83   787.1 3047.94   815.2 3060.01831.4305 3063.27
#Mann= 4 ,-1,0
       0      .1       0   316.9    .045       0   348.3      .1       0
   685.3     .06       0
#XS Ineff= 1 ,-1
   350.5  547.723054.834
Permanent Ineff=
       F
Bank Sta=316.9,348.3
XS Rating Curve= 0 ,0
Exp/Cntr(USF)=0,0
Exp/Cntr=0.3,0.1

Type RM Length L Ch R = 1 ,33684   ,368.4,376.8,385.5
XS GIS Cut Line= 3
2245985.15623182515269.5224192482246431.13359915515538.383060695
2246835.06167184515697.660691884
#Sta/Elev= 30
       0 3081.61   138.9 3055.82   154.3 3051.99     181  3042.4   231.8 3037.31
   239.5  3031.1   251.1 3030.11   269.8 3031.15   279.1 3031.84   288.4 3037.63
   301.5 3033.63   328.3 3033.57   344.5 3029.16   363.2 3032.22   398.2 3032.69
     439 3030.95   451.9 3033.49   502.9 3034.36   517.3 3040.37   530.5 3038.04
   539.1 3039.32   548.4 3036.74   629.4  3037.4   647.1 3039.03   668.6 3044.92
     681 3042.37   874.4 3042.34   900.2 3049.59   930.8 3054.44954.9485 3059.79
#Mann= 6 ,-1,0
       0      .1       0   239.5    .045       0   269.8      .1       0
  600.75     .07       0  710.75     .08       0  820.75      .1       0
#XS Ineff= 2 , 0
                          383.72          3042.8
Permanent Ineff=
       F       F
Bank Sta=239.5,269.8
XS Rating Curve= 0 ,0
Exp/Cntr(USF)=0,0
Exp/Cntr=0.3,0.1

Type RM Length L Ch R = 1 ,33308   ,408.6,406.9,403.9
XS GIS Cut Line= 2
2245813.90491527515495.5462415662246452.48774669516120.154210199
#Sta/Elev= 30
       0 3100.08    31.2 3084.56    53.7 3070.85   105.3 3044.43   122.5 3032.19
  133.14 3021.35   138.5 3019.37   148.7 3019.47   154.2 3021.35   159.8 3023.45
   179.7 3023.64   196.8 3020.68     214 3022.97   265.5 3021.53   276.9 3025.39
   288.4  3026.4   308.2 3023.81   429.9 3026.76   554.3 3027.28   574.1 3028.66
   590.7 3027.34   614.4    3028   627.9 3029.85     697 3029.66   732.5 3038.43
     775  3038.4   808.9 3036.38   831.8 3039.47   843.2 3039.57   893.3 3058.36
#Mann= 6 ,-1,0
       0      .1       0  133.14    .045       0   154.2      .1       0
     380     .03       0     530     .08       0     670     .06       0
#XS Ineff= 2 , 0
                          288.15         3028.63
Permanent Ineff=
       F       F
Bank Sta=133.14,154.2
XS Rating Curve= 0 ,0
Exp/Cntr=0.3,0.1

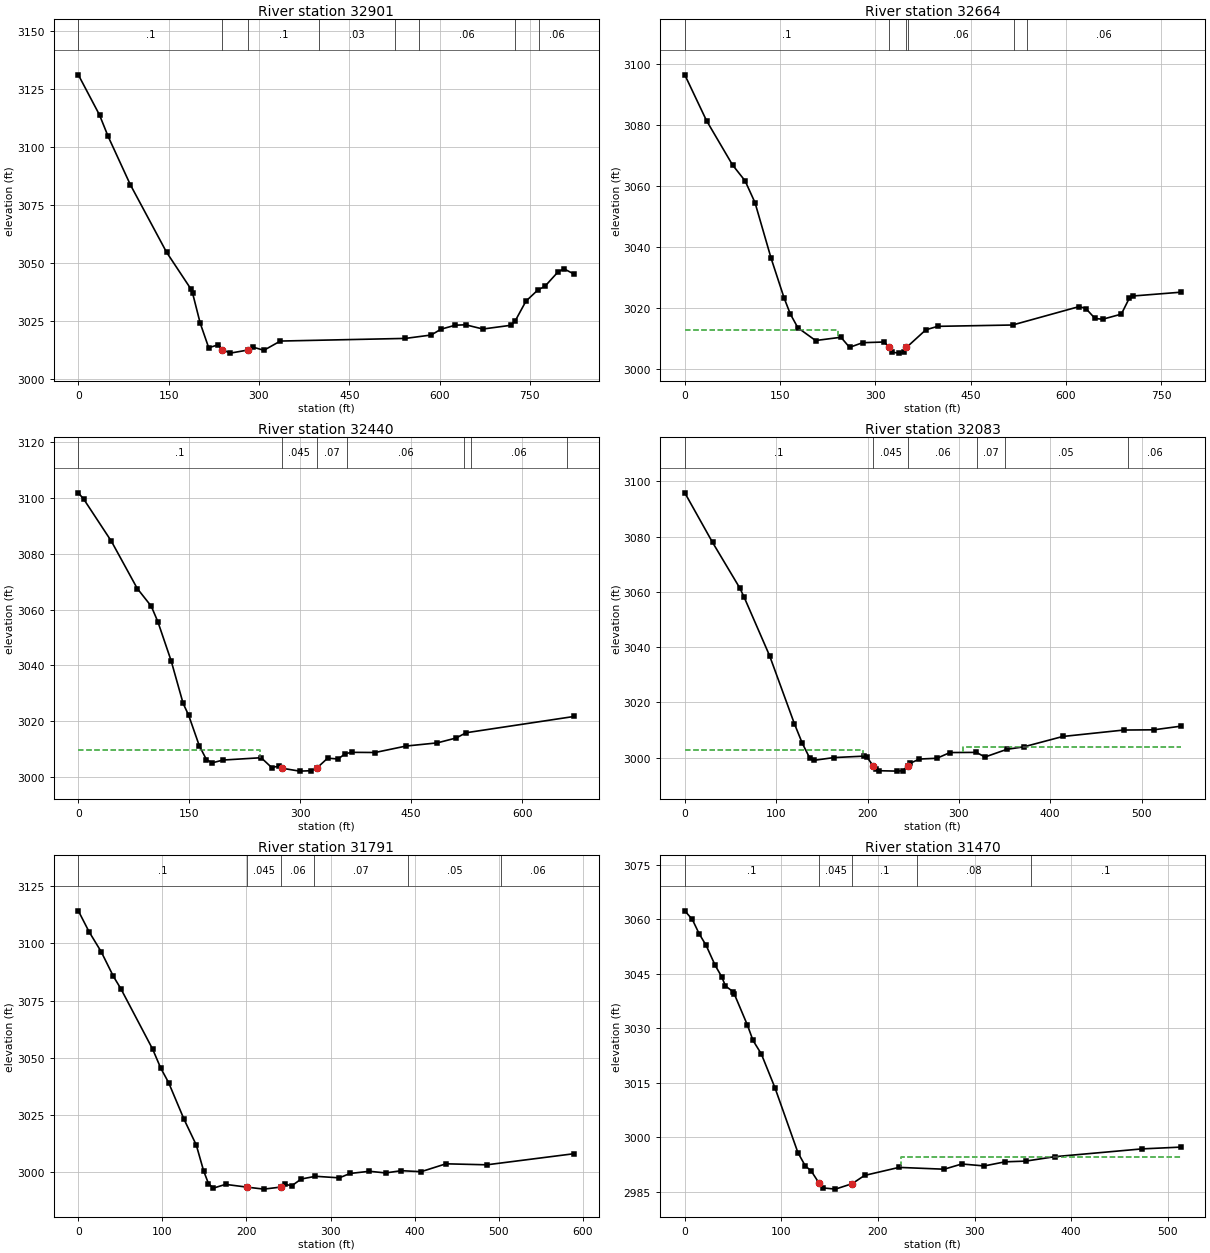
Type RM Length L Ch R = 1 ,32901   ,238.9,237.2,234.7
XS GIS Cut Line= 3
2245427.40124157515692.1677578422245758.34488501515990.731533272
2246062.00790501516215.385305188
#Sta/Elev= 30
       0 3131.09    35.2 3113.79    49.4 3104.61    86.2 3083.85   146.5  3054.7
   186.6 3038.99   189.6 3037.21   202.3 3024.22   216.5 3013.56   232.7 3014.85
   239.2  3012.7   252.3 3011.24   282.2  3012.6   290.1 3013.83   308.1 3012.46
   335.5 3016.44   543.2 3017.58     586 3019.04   602.2 3021.54   626.1 3023.27
   643.2 3023.44   671.8 3021.62   718.9 3023.25   725.6 3025.16   743.3 3033.61
   763.4  3038.5   774.8 3039.99   796.3 3046.13   806.3 3047.56   823.4 3045.26
#Mann= 8 ,-1,0
       0      .1       0   239.2    .045       0   282.2      .1       0
     400     .03       0  525.72     .08       0  565.72     .06       0
  725.72     .07       0  765.72     .06       0
Bank Sta=239.2,282.2
XS Rating Curve= 0 ,0
Exp/Cntr=0.3,0.1

Type RM Length L Ch R = 1 ,32664   ,213.3,223.7,232.5
XS GIS Cut Line= 4
2245241.76675199515814.3245485142245347.66216653515949.016084553
2245578.96004566516135.7264207172245876.21033209516230.474949517
#Sta/Elev= 30
       0 3096.47    34.2 3081.45    75.1 3066.94    94.9 3061.72   110.5 3054.59
   135.9 3036.31   156.3 3023.33   166.1 3018.07     178 3013.55   205.9 3009.36
   245.8 3010.43   259.4 3007.12   279.9 3008.65     314 3008.88   321.1 3007.25
   326.2 3005.56   336.5 3005.23   345.3 3005.49  348.97 3007.09   379.5 3012.88
   398.2 3014.01     516 3014.45     621  3020.5   631.4 3019.85   645.8  3016.6
   657.8 3016.34   687.2 3018.01   699.9 3023.29     705 3023.95780.5737  3025.2
#Mann= 6 ,-1,0
       0      .1       0   321.1    .045       0  348.97      .1       0
  351.33     .06       0  518.59     .07       0  538.59     .06       0
#XS Ineff= 2 , 0
          240.84 3012.77
Permanent Ineff=
       F       F
Bank Sta=321.1,348.97
XS Rating Curve= 0 ,0
Exp/Cntr(USF)=0,0
Exp/Cntr=0.3,0.1

Type RM Length L Ch R = 1 ,32440   ,357,356.7,356.1
XS GIS Cut Line= 4
2245110.79084453515936.0113845222245213.89953763516050.266963369
2245388.53408091516327.0812926072245524.15452409 516458.98610721
#Sta/Elev= 30
       0 3101.87     7.5 3099.52    44.7  3084.5    79.7 3067.55    98.6 3061.21
   107.5 3055.67   125.5 3041.63   141.7 3026.35   149.1 3022.14   163.5 3011.21
   173.2  3006.2     181 3005.04   195.6 3006.04   247.2 3006.88   261.4 3003.36
   270.8 3003.84  274.71 3003.14   299.2 3002.07   314.3 3002.21   322.5 3003.17
   337.1 3006.72   351.3 3006.42   360.7 3008.29   369.4 3008.81   401.3 3008.75
     443 3011.06   485.3  3012.2   510.7 3013.94   524.4 3015.84   670.4 3021.68
#Mann= 7 ,-1,0
       0      .1       0  274.71    .045       0   322.5     .07       0
   363.9     .06       0   521.2     .07       0   531.2     .06       0
   661.2     .08       0
#XS Ineff= 2 , 0
          246.09  3009.5
Permanent Ineff=
       F       F
Bank Sta=274.71,322.5
XS Rating Curve= 0 ,0
Exp/Cntr(USF)=0,0
Exp/Cntr=0.3,0.1

Type RM Length L Ch R = 1 ,32083   ,291.6,292.4,293.2
XS GIS Cut Line= 3
2244856.27028677516158.9490993452245101.50177308516530.511957383
2245179.52997326516589.033107524
#Sta/Elev= 30
       0 3095.83    30.4 3077.88    60.2 3061.39    65.1 3057.97    92.8 3036.92
   119.9 3012.37   128.6 3005.24   136.9 2999.79   141.7 2999.08   163.2 3000.06
   195.9 3000.58   199.2 3000.29  206.36 2997.01   208.8 2995.92   212.3 2995.31
   232.7 2995.16   238.3  2995.3   244.1 2997.05   246.9 2998.02   256.7 2999.53
   275.9 2999.81   290.3 3001.88   319.1 3001.94   328.6 3000.27   352.5 3003.04
   371.1 3003.95   413.7 3007.69   480.4 3010.02   513.5 3010.11542.7289 3011.41
#Mann= 6 ,-1,0
       0      .1       0  206.36    .045       0   244.1     .06       0
     320     .07       0     350     .05       0  485.19     .06       0
#XS Ineff= 2 , 0
           195.1  3002.8  304.72         3004.05
Permanent Ineff=
       F       F
Bank Sta=206.36,244.1
XS Rating Curve= 0 ,0
Exp/Cntr(USF)=0,0
Exp/Cntr=0.3,0.1

Type RM Length L Ch R = 1 ,31791   ,331.1,320.7,308.1
XS GIS Cut Line= 3
2244617.63312874516318.2553219992244805.18039379516616.900321877
 2245007.3311215516740.925299655
#Sta/Elev= 30
       0 3114.31    12.7 3105.19    27.2 3096.39    41.7 3085.61    50.7 3080.12
    88.5 3053.65    97.9 3045.52   107.4 3039.06   125.8 3022.95   140.3 3011.74
     149 3000.47   154.8 2994.83   160.6 2992.86   175.1  2994.5   200.3 2993.31
   220.7 2992.42  241.47 2993.35   245.5 2994.62   253.8 2993.86   265.1 2996.84
   282.1 2998.04   310.5 2997.36   323.1 2999.27   346.3 3000.24   365.5 2999.51
   384.3  3000.5   407.8 3000.06   437.3 3003.51   485.9 3003.07   589.8 3007.94
#Mann= 6 ,-1,0
       0      .1       0   200.3    .045       0  241.47     .06       0
     280     .07       0  392.65     .05       0  502.65     .06       0
Bank Sta=200.3,241.47
XS Rating Curve= 0 ,0
Exp/Cntr=0.3,0.1

Type RM Length L Ch R = 1 ,31470   ,226.5,236.6,247.4
XS GIS Cut Line= 3
2244348.36233339516586.0213641842244585.37299146516767.353327979
2244785.51532494516845.604465881
#Sta/Elev= 30
       0 3062.37     7.8 3059.99    14.9 3056.04    22.1 3052.85    31.5 3047.33
    38.1 3044.28    42.1 3041.69    50.1 3040.09    51.3 3039.45    64.9 3030.88
    70.6 3026.71    79.2    3023    93.4 3013.64   117.1 2995.84   124.8 2992.15
   130.7 2990.85   139.1  2987.4   143.4 2986.12   155.9 2985.79   173.3 2987.29
   186.1 2989.56   221.8 2991.77   268.5 2991.27   286.8 2992.71     310 2992.17
   331.5  2993.3     353  2993.5     383 2994.72   473.2 2996.86513.3172 2997.35
#Mann= 5 ,-1,0
       0      .1       0   139.1    .045       0   173.3      .1       0
     240     .08       0  358.42      .1       0
#XS Ineff= 2 , 0
                             224          2994.7
Permanent Ineff=
       F       F
Bank Sta=139.1,173.3
XS Rating Curve= 0 ,0
Exp/Cntr(USF)=0,0
Exp/Cntr=0.3,0.1

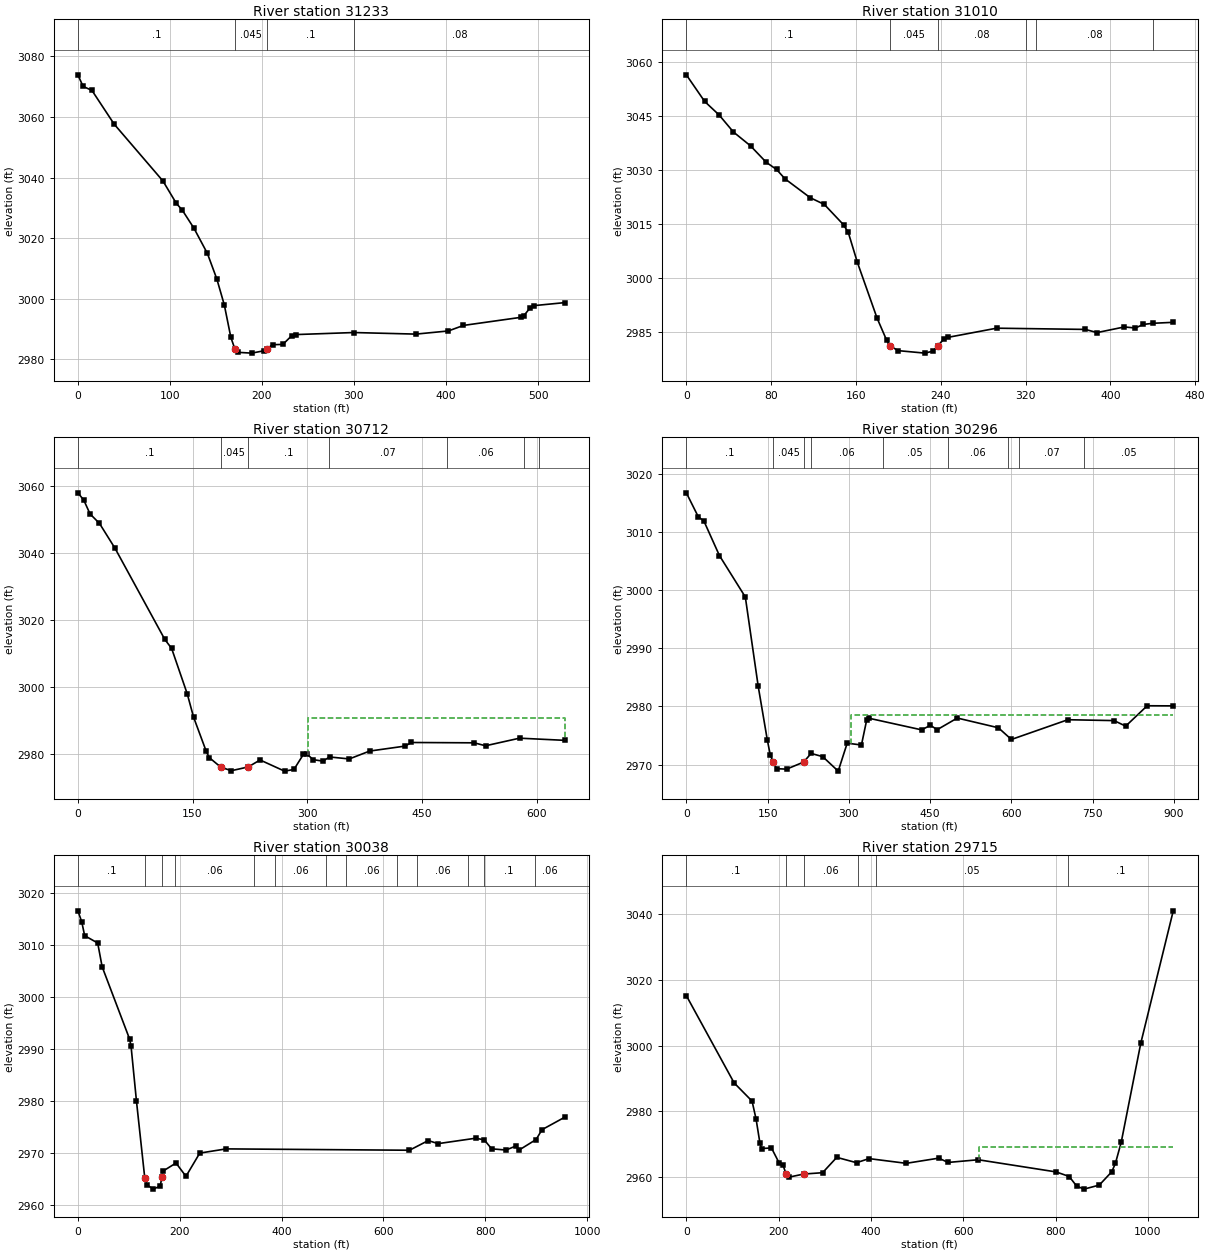
Type RM Length L Ch R = 1 ,31233   ,219.2,223.7,227.8
XS GIS Cut Line= 3
2244175.30693226 516660.510428152244419.08932342 517022.42194095
2244488.31148387517084.119953528
#Sta/Elev= 30
       0 3073.91     5.6 3070.11    15.3 3068.75    39.4 3057.63    92.4 3038.86
   106.9  3031.5   113.5  3029.2   126.2 3023.21   140.7 3014.94     151 3006.47
   159.1 2997.93   166.2 2987.23  170.43 2983.51   174.4 2982.26   188.9 2982.01
     202 2982.78   205.7 2983.51   211.5 2984.79   222.7 2984.89   232.3 2987.75
   237.1 2988.14   299.8 2988.81   367.3 2988.29   402.5 2989.33     419 2991.16
   481.6 2993.84   484.4 2994.31   491.4 2996.96   495.7  2997.7 529.087 2998.69
#Mann= 4 ,-1,0
       0      .1       0  170.43    .045       0   205.7      .1       0
     300     .08       0
Bank Sta=170.43,205.7
XS Rating Curve= 0 ,0
Exp/Cntr(USF)=0,0
Exp/Cntr=0.3,0.1

Type RM Length L Ch R = 1 ,31010   ,287.4,297.6,306.5
XS GIS Cut Line= 2
 2243997.7370424516753.8098618032244210.67042727517160.866261856
#Sta/Elev= 30
       0 3056.39    17.3 3048.99    30.9 3045.24    44.4 3040.51    60.6 3036.64
    75.4 3032.08    85.1 3030.09    93.2 3027.46   116.9 3022.24   130.2 3020.37
   148.3 3014.72   152.8 3012.58   161.4 3004.25   179.9 2988.82   188.9 2982.68
  192.37 2981.03   199.9 2979.74     225 2979.05   232.5 2979.58  236.98 2980.99
   243.1 2983.03   247.3 2983.46   292.7 2985.98   376.3 2985.64   387.5 2984.76
   413.3 2986.33   423.6 2986.03   431.1 2987.02     440 2987.34 459.386 2987.61
#Mann= 6 ,-1,0
       0      .1       0  192.37    .045       0  236.98     .08       0
     320      .1       0     330     .08       0     440     .05       0
Bank Sta=192.37,236.98
XS Rating Curve= 0 ,0
Exp/Cntr(USF)=0,0
Exp/Cntr=0.3,0.1

Type RM Length L Ch R = 1 ,30712   ,430,416.6,405.4
XS GIS Cut Line= 4
2243766.07835082516821.7114939352243832.84881071517112.373218129
 2243871.3313581517209.773223045 2244102.7450928517243.814007368
#Sta/Elev= 30
       0  3057.9     7.7 3055.73    15.9  3051.6    28.2 3048.78    48.7 3041.29
   113.7 3014.12   122.6 3011.45   143.1 2997.83   151.3 2990.93   167.7 2980.82
   171.8 2978.85  186.73 2976.02   200.6 2974.92  222.67 2976.04   238.3 2978.13
   270.3  2974.8   282.6  2975.3     295 2979.81   299.1 2980.02   307.7 2978.22
   320.6 2977.79   329.2 2979.03     355 2978.44   381.6 2980.79   428.1 2982.28
   436.2 2983.35   518.4 2983.25   533.2 2982.37   577.7 2984.64   636.9 2983.99
#Mann= 7 ,-1,0
       0      .1       0  186.73    .045       0  222.67      .1       0
  328.23     .07       0  482.96     .06       0  582.96     .07       0
  602.96     .05       0
#XS Ineff= 2 , 0
                          300.51         2990.65
Permanent Ineff=
       F       F
Bank Sta=186.73,222.67
XS Rating Curve= 0 ,0
Exp/Cntr=0.3,0.1

Type RM Length L Ch R = 1 ,30296   ,263.4,258,254.4
XS GIS Cut Line= 4
2243336.88896748517045.9073686092243522.96331147517333.169248199
2243690.04985346517374.4626111962243977.92243553517629.028390008
#Sta/Elev= 30
       0 3016.69    22.1 3012.57    32.5 3011.83    61.1 3005.91   108.9 2998.79
   132.6 2983.49   149.4 2974.27   155.1 2971.58   160.6 2970.42   166.7  2969.3
     185 2969.22   216.4 2970.43   230.3 2971.92   251.7 2971.37   280.3 2968.88
   296.9 2973.68   323.2 2973.37   332.7 2977.58   337.4 2977.96   434.2 2975.97
   450.6 2976.75     463    2976   500.1    2978   575.9 2976.33     600 2974.32
   704.1 2977.71   789.5 2977.56   810.9 2976.61   850.6 2980.11   898.7 2980.09
#Mann= 9 ,-1,0
       0      .1       0   160.6    .045       0   216.4      .1       0
     230     .06       0  362.26     .05       0  482.26     .06       0
  594.38     .05       0  614.38     .07       0  734.38     .05       0
#XS Ineff= 2 , 0
                          304.79         2978.54
Permanent Ineff=
       F       F
Bank Sta=160.6,216.4
XS Rating Curve= 0 ,0
Exp/Cntr=0.3,0.1

Type RM Length L Ch R = 1 ,30038   ,321.3,322.9,323.1
XS GIS Cut Line= 3
2243138.22327484517244.3877436682243339.48648961517488.999958543
2243791.55463356 517941.06810249
#Sta/Elev= 30
       0 3016.64     7.6 3014.51    13.3 3011.86    38.9 3010.45    47.6 3005.89
   101.4 2992.01   104.3 2990.69     115 2980.06  131.24 2965.32   135.5 2963.95
   147.9 2963.11   161.6 2963.69  164.92 2965.35   166.8 2966.56   192.7 2968.13
   212.2 2965.57   239.3 2970.04   291.1 2970.85   651.1 2970.59   687.9 2972.45
   707.3 2971.86   780.9  2972.9   797.9 2972.59   812.4 2970.86   840.6 2970.63
   860.4 2971.42   866.5 2970.64   899.7 2972.65   911.4 2974.55 956.089 2976.95
#Mann= 13 ,-1,0
       0      .1       0  131.24    .045       0  164.92      .1       0
     190     .06       0  346.77     .07       0  386.77     .06       0
  486.77     .08       0  526.77     .06       0  626.77     .03       0
  666.77     .06       0  766.77     .07       0  796.77      .1       0
  896.77     .06       0
Bank Sta=131.24,164.92
XS Rating Curve= 0 ,0
Exp/Cntr(USF)=0,0
Exp/Cntr=0.3,0.1

Type RM Length L Ch R = 1 ,29715   ,412.8,412.8,411.3
XS GIS Cut Line= 5
 2242852.0968572517316.9712148752242912.18920287517467.325458491
2243200.15041785 517844.04891178 2243184.6686321518151.620388712
2243227.25685699518253.928834291
#Sta/Elev= 30
       0 3015.26   103.6 2988.63   142.4 2983.08   151.1 2977.61   159.6 2970.16
   163.2 2968.62   184.4  2968.8   201.4 2964.14   209.6 2963.53  216.11 2960.83
   223.2 2959.92   254.5 2960.84   295.2 2961.25   325.9 2965.93   368.7  2964.3
   395.8 2965.55   476.4 2964.11   546.9 2965.69     567 2964.38   632.5  2965.2
   801.4 2961.48   829.5 2960.09   845.5 2957.18   861.5 2956.24   894.6 2957.47
   921.6 2961.52   929.6  2964.1   942.2 2970.55   984.6 3000.77  1054.9 3041.12
#Mann= 6 ,-1,0
       0      .1       0  216.11    .045       0   254.5     .06       0
  371.92     .07       0  411.92     .05       0  826.09      .1       0
#XS Ineff= 2 , 0
                          634.48         2969.17
Permanent Ineff=
       F       F
Bank Sta=216.11,254.5
XS Rating Curve= 0 ,0
Exp/Cntr=0.3,0.1

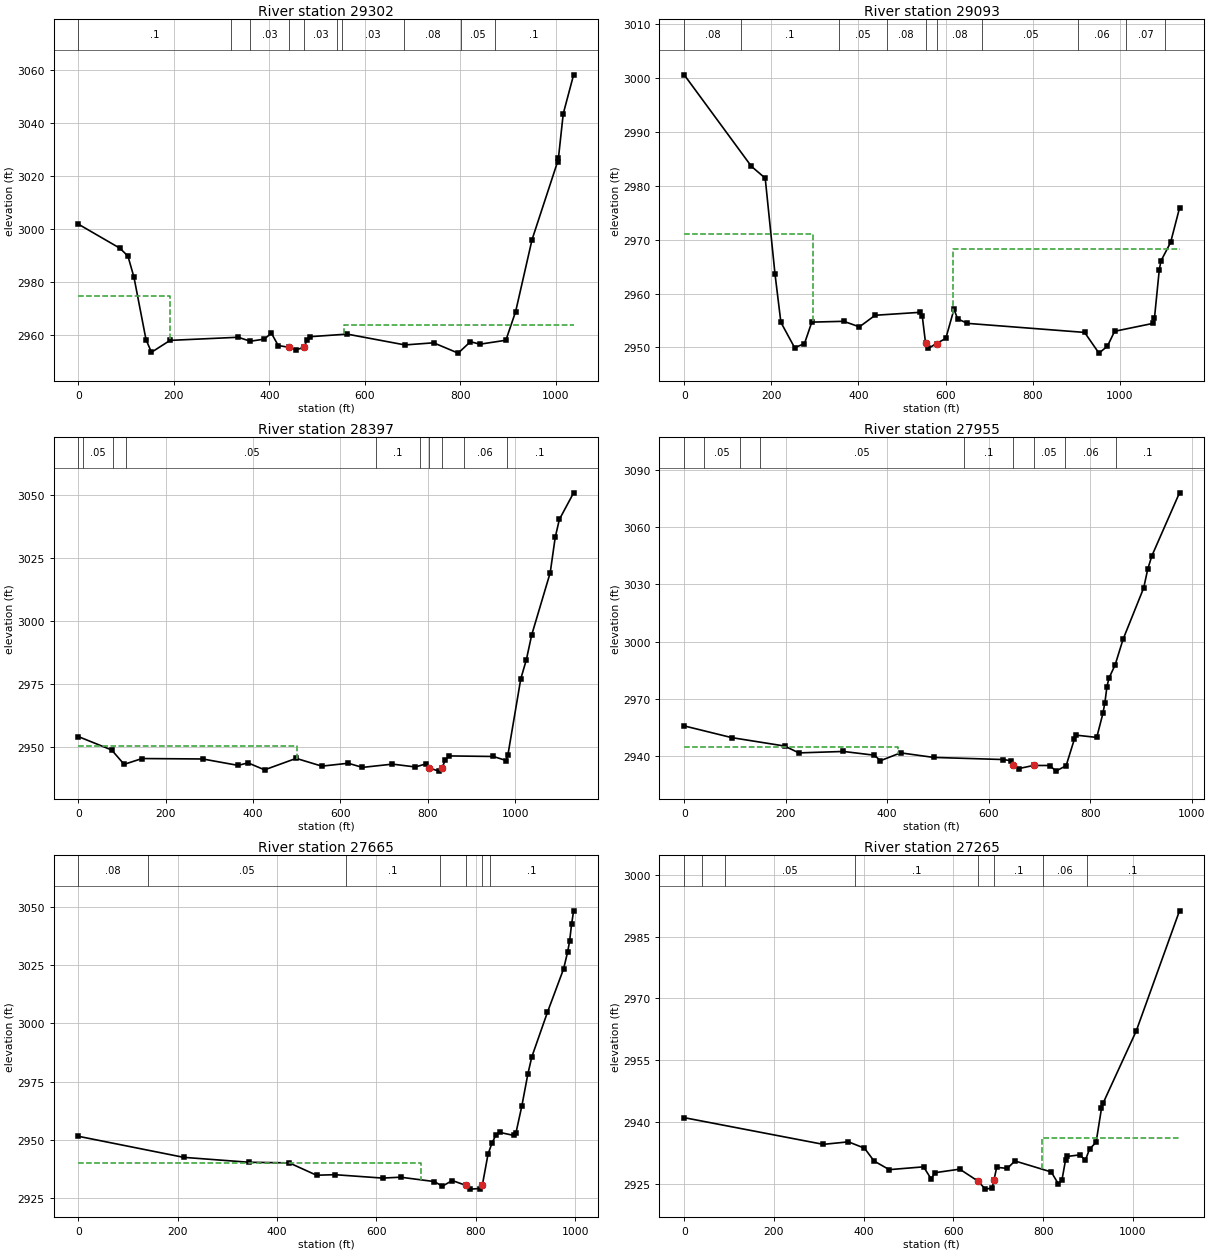
Type RM Length L Ch R = 1 ,29302   ,204.2,209.2,215.1
XS GIS Cut Line= 3
2242558.64023841517426.2484760962242680.99453565517808.956864077
 2243065.6945715518314.379905115
#Sta/Elev= 30
       0 3001.74    87.1 2992.63   103.9 2989.65   116.5 2981.69   141.7 2958.12
   153.1 2953.28   192.1 2957.79   334.8 2958.97     360 2957.47   389.4 2958.26
   404.2 2960.53   418.5 2955.85   440.1 2955.19   455.6 2954.22  473.54 2955.19
   478.4 2958.11   484.1 2959.17   562.9 2960.16   683.9 2956.07   743.9 2956.87
   795.3 2952.97     821 2957.29   840.9 2956.35   895.2 2957.84   915.6 2968.67
     950  2995.9  1003.6 3025.41  1005.3 3026.84  1015.3 3043.49    1037 3058.19
#Mann= 10 ,-1,0
       0      .1       0     320     .05       0     360     .03       0
   440.1    .045       0  473.54     .03       0  541.79      .1       0
  551.79     .03       0  681.79     .08       0  801.79     .05       0
  871.79      .1       0
#XS Ineff= 2 , 0
          191.36 2974.64  557.03         2963.64
Permanent Ineff=
       F       F
Bank Sta=440.1,473.54
XS Rating Curve= 0 ,0
Exp/Cntr=0.3,0.1

Type RM Length L Ch R = 1 ,29093   ,690.8,696.2,706.5
XS GIS Cut Line= 3
2242379.78554494 517411.232763532242329.56608757517557.325730438
2242781.54120394518429.318126672
#Sta/Elev= 30
       0 3000.56   154.3 2983.58   185.9  2981.4   208.4 2963.61   221.9 2954.66
   253.4 2949.96     276 2950.71   292.8  2954.7   366.1 2954.85   402.1 2953.82
   438.2 2955.97   541.8 2956.52   546.3 2955.84   553.9 2950.82   559.8 2949.81
   579.12950.733   600.4 2951.69   619.2 2957.09   627.4 2955.31   649.9 2954.47
   918.9 2952.79   951.8 2948.95   971.2 2950.23   987.8    2953  1076.2 2954.47
  1079.2 2955.42  1090.2 2964.34    1094 2966.03  1116.3 2969.49  1136.7 2975.85
#Mann= 10 ,-1,0
       0     .08       0     130      .1       0  354.48     .05       0
  464.48     .08       0   553.9    .045       0   579.1     .08       0
  684.48     .05       0  904.48     .06       0 1014.48     .07       0
 1104.48      .1       0
#XS Ineff= 2 , 0
          295.02 2971.03  615.95         2968.29
Permanent Ineff=
       F       F
Bank Sta=553.9,579.1
XS Rating Curve= 0 ,0
Exp/Cntr(USF)=0,0
Exp/Cntr=0.3,0.1

Type RM Length L Ch R = 1 ,28397   ,433.7,442,446.6
XS GIS Cut Line= 5
2241862.88930428517722.5207326922241934.72389387518064.444101615
2242063.18880292518147.0839351892242135.86719685518599.283975231
2242082.01371895518764.026105544
#Sta/Elev= 30
       0 2954.16    76.3 2948.83   104.9 2943.12   145.8 2945.43   284.7 2945.26
   365.4 2942.72   388.6  2943.7   426.2 2940.94   498.6  2945.5   557.2 2942.41
   617.7 2943.56   650.1 2941.91     719 2943.21   771.6 2942.08     796 2943.35
   803.22941.732   824.3 2940.43   832.4  2941.6   839.9 2945.03   848.6 2946.47
   949.9 2946.25     979 2944.65   983.2 2946.94  1012.6  2977.1  1025.3 2984.65
  1037.5 2994.49    1080 3019.31  1091.4 3033.31  1100.9 3040.43  1133.5    3051
#Mann= 10 ,-1,0
       0     .08       0      10     .05       0      80      .1       0
     110     .05       0  682.14      .1       0  782.14     .08       0
   803.2    .045       0   832.4     .08       0  882.14     .06       0
  980.14      .1       0
#XS Ineff= 2 , 0
          500.96  2950.4
Permanent Ineff=
       F       F
Bank Sta=803.2,832.4
XS Rating Curve= 0 ,0
Exp/Cntr=0.3,0.1

Type RM Length L Ch R = 1 ,27955   ,291.2,289.5,282.9
XS GIS Cut Line= 3
2241831.46994613517697.418632408  2241745.106075517855.988363014
2241664.40540853518647.421214879
#Sta/Elev= 30
       0 2955.76    93.7 2949.62   197.8 2945.22     226 2941.62   313.9 2942.37
   374.8  2940.4   386.8 2937.53   426.3 2941.64   491.4 2939.25   628.1 2938.14
   644.1 2937.53   648.2 2935.18   659.9 2933.43   688.4 2935.03   720.5 2935.01
   732.6 2932.06   752.7 2934.93   768.8 2948.72   772.8 2950.91     813 2949.73
   825.1 2962.28   829.1 2968.02   833.1 2976.36   837.1 2980.83   849.2 2987.71
   864.8 3001.12   905.5 3028.09   913.5 3037.94   921.6  3044.9976.0999 3077.95
#Mann= 9 ,-1,0
       0     .08       0      40     .05       0     110     .08       0
     150     .05       0  550.56      .1       0   648.2    .045       0
   688.4     .05       0  750.56     .06       0  850.56      .1       0
#XS Ineff= 2 , 0
          421.87 2944.57
Permanent Ineff=
       F       F
Bank Sta=648.2,688.4
XS Rating Curve= 0 ,0
Exp/Cntr(USF)=0,0
Exp/Cntr=0.3,0.1

Type RM Length L Ch R = 1 ,27665   ,387.8,400.2,409.2
XS GIS Cut Line= 3
2241660.15800503517669.1026090852241422.30340912518000.400081959
2241415.22440329518589.373367068
#Sta/Elev= 30
       0 2951.44   212.1 2942.38     344 2940.26   424.6    2940   479.4 2934.69
   516.6 2934.92   612.3 2933.46   648.6 2933.84   716.6 2931.96   732.6 2929.96
   752.6 2932.41   780.6 2930.28   788.6 2928.71   808.6 2928.98  813.16 2930.41
   824.6 2943.73   832.6 2948.54   840.6 2952.04   848.6 2953.09   876.7 2951.79
   880.7 2952.77   892.7 2964.53   904.8 2978.25   912.7 2985.58   944.3 3004.84
   976.7 3023.44   984.7 3030.63   988.7 3035.22   992.7 3042.56 996.855 3048.41
#Mann= 7 ,-1,0
       0     .08       0     140     .05       0  537.84      .1       0
  727.84     .07       0   780.6    .045       0  813.16     .07       0
  827.84      .1       0
#XS Ineff= 2 , 0
          689.37 2939.92
Permanent Ineff=
       F       F
Bank Sta=780.6,813.16
XS Rating Curve= 0 ,0
Exp/Cntr(USF)=0,0
Exp/Cntr=0.3,0.1

Type RM Length L Ch R = 1 ,27265   ,450.5,450.7,447.2
XS GIS Cut Line= 5
2241414.50377725517774.1321230362241141.97477823518010.310690122
2241011.30090183518378.9921838972241016.00392286518584.873665191
2241081.99786148518715.363521401
#Sta/Elev= 30
       0 2941.04     310 2934.56     366 2935.17   401.8 2933.63   423.1 2930.52
     457 2928.42   533.5  2929.1   550.4 2926.17   558.9 2927.68   614.1 2928.54
   654.22925.679   671.3 2923.69   686.2 2923.94   690.4 2925.86   696.4 2928.99
   720.2 2928.72   737.1 2930.53     818 2927.86     834 2924.95     842 2925.95
     850 2930.82     854 2931.63     882 2932.01     894 2930.68   903.4 2933.41
     918 2935.07     930 2943.29     934 2944.66  1007.4 2962.07  1103.9 2991.26
#Mann= 8 ,-1,0
       0     .05       0      40      .1       0      90     .05       0
  380.63      .1       0   654.2    .045       0   690.4      .1       0
  800.63     .06       0  897.67      .1       0
#XS Ineff= 2 , 0
                          797.34          2936.1
Permanent Ineff=
       F       F
Bank Sta=654.2,690.4
XS Rating Curve= 0 ,0
Exp/Cntr=0.3,0.1