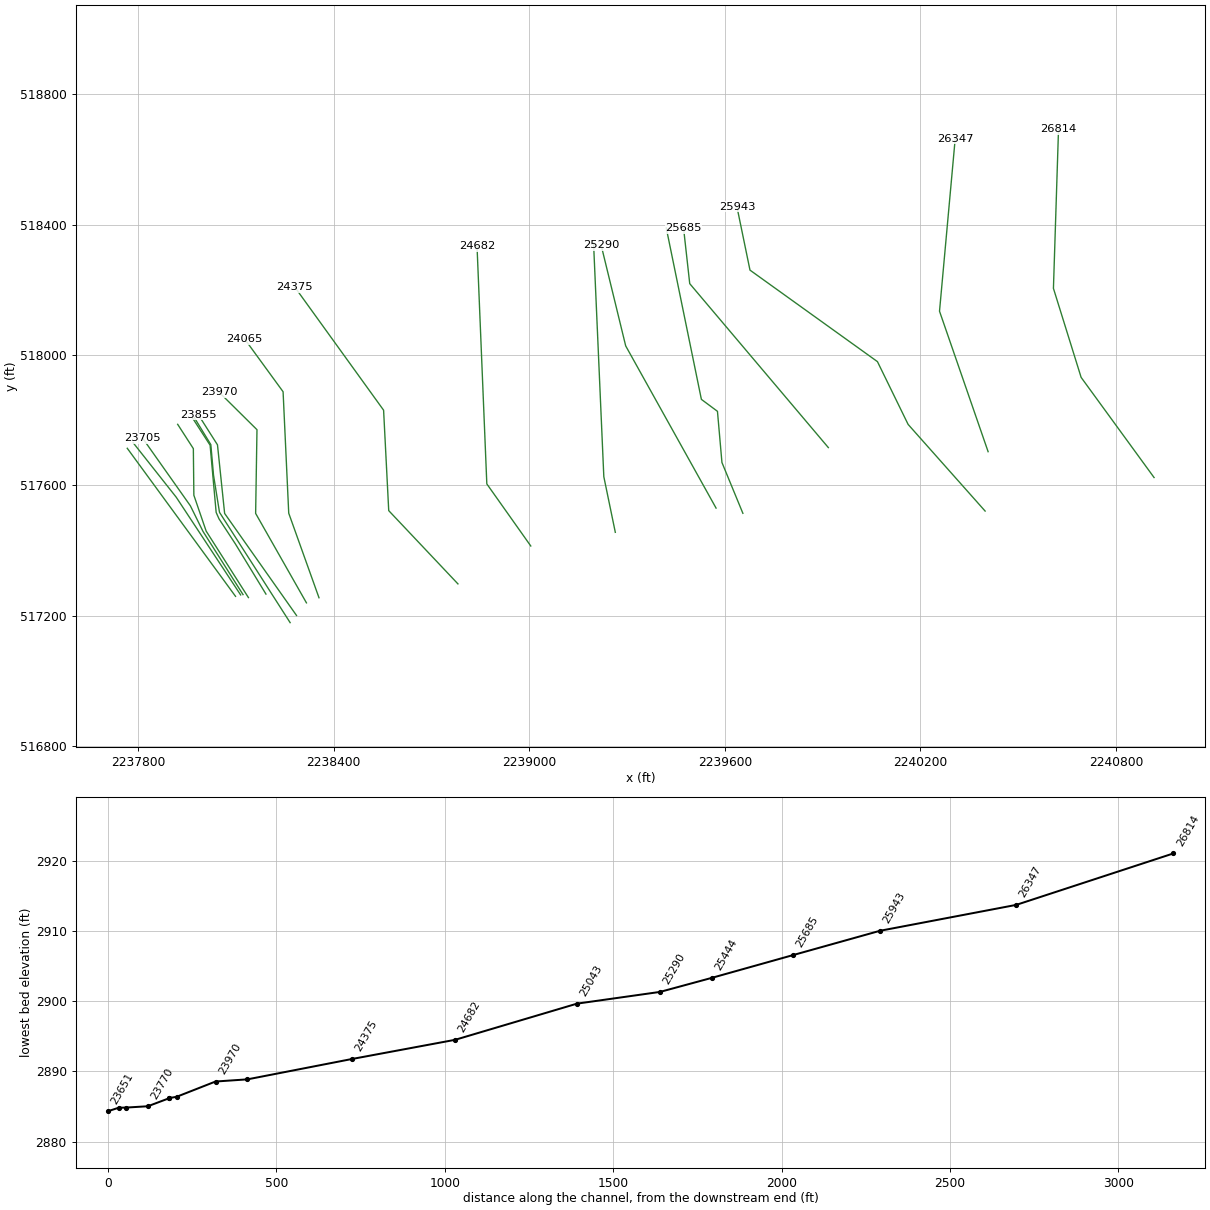
HEC-RAS study BIGSPRFK.prj: BIGSPRFK

--- BIGSPRFK.g01 (geometry) --- (continued)

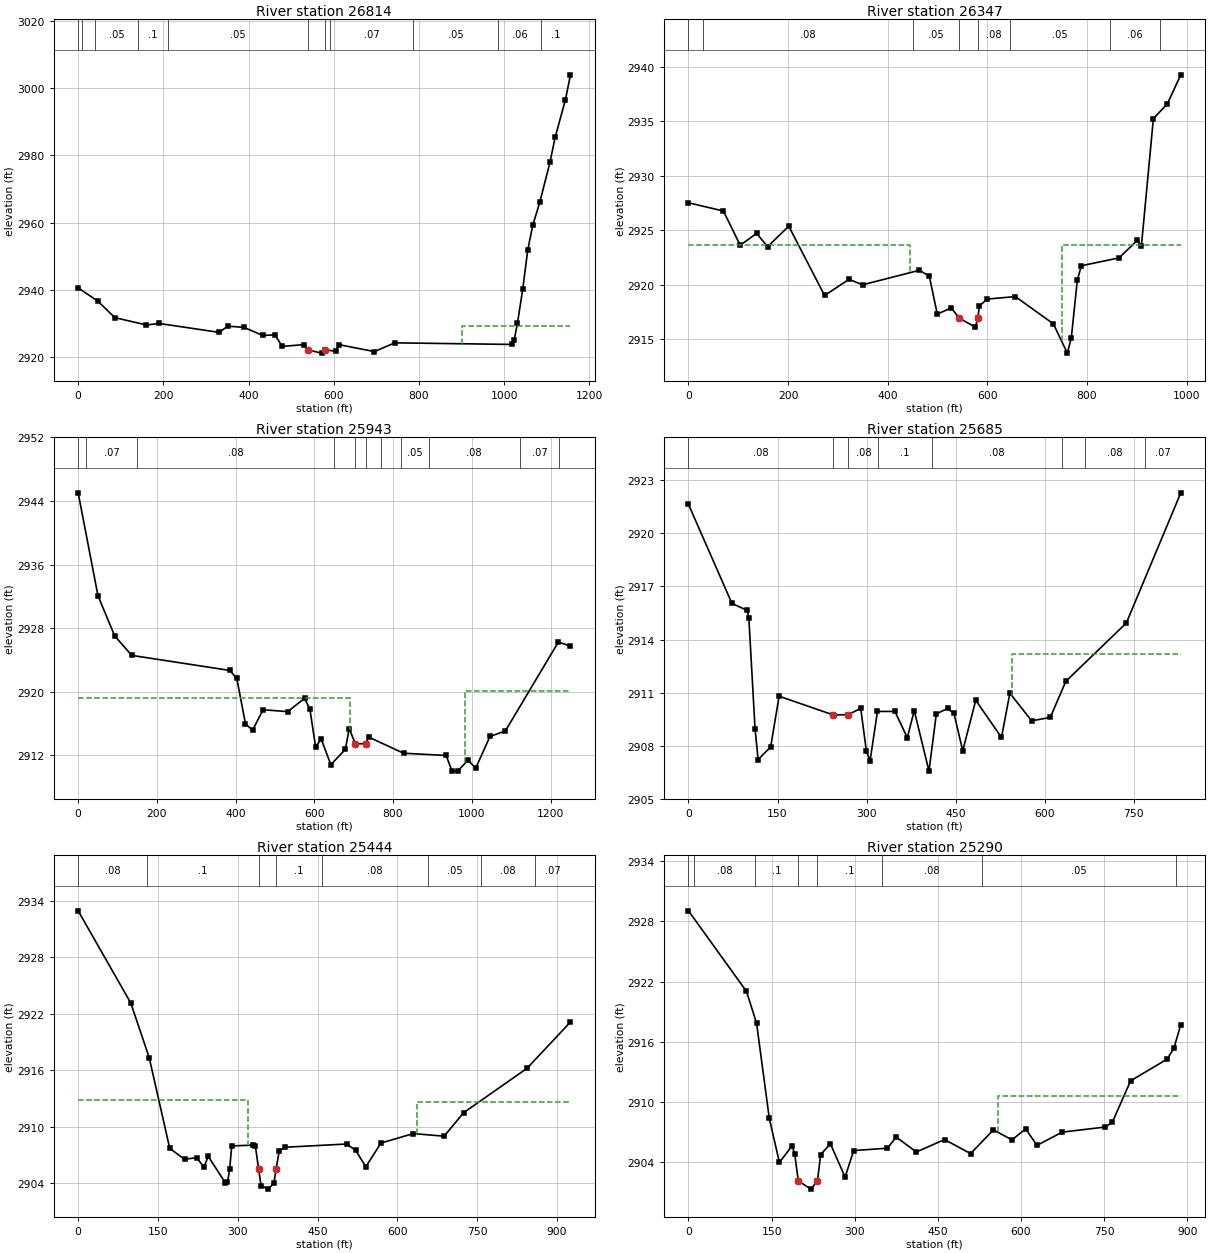
Type RM Length L Ch R = 1 ,26814   ,477,466.8,446.7
XS GIS Cut Line= 4
2240916.95953177517623.5719650162240693.16580857517931.025824819
 2240608.2177386518204.2754498822240623.84901749518693.308678131
#Sta/Elev= 30
       0 2940.53    46.5 2936.52    86.1 2931.64   160.3 2929.44     190  2929.9
     331 2927.24     351  2929.1   389.2 2928.73   432.8 2926.35   462.1 2926.48
   478.9 2923.06   529.1 2923.57  539.81 2922.02   571.3 2921.05   579.4 2922.01
   604.5 2921.64   612.9 2923.57   695.3 2921.51   743.4 2924.12  1019.5 2923.64
  1023.5 2924.97  1031.2 2929.92  1043.6 2940.17  1055.5 2951.94  1067.5 2959.36
  1083.5 2965.98  1107.6 2978.01  1119.6 2985.37  1143.6 2996.51  1155.7 3004.06
#Mann= 11 ,-1,0
       0     .05       0      10      .1       0      40     .05       0
     140      .1       0     210     .05       0  539.81    .045       0
   579.4     .05       0  590.28     .07       0  786.43     .05       0
  986.43     .06       0 1086.43      .1       0
#XS Ineff= 2 , 0
                             901         2929.27
Permanent Ineff=
       F       F
Bank Sta=539.81,579.4
XS Rating Curve= 0 ,0
Exp/Cntr=0.3,0.1

Type RM Length L Ch R = 1 ,26347   ,372.6,404.6,438.7
XS GIS Cut Line= 3
2240407.81164985517702.9738114432240258.72778706518134.170214599
2240306.89334273518663.991326988
#Sta/Elev= 30
       0 2927.52    70.1 2926.76   103.9 2923.62   136.7 2924.71   158.9 2923.49
   201.3 2925.37   273.2 2919.01   322.2 2920.49   349.4 2919.99   463.3 2921.32
   483.4  2920.8   499.4  2917.3   527.5 2917.87   543.6 2916.93   575.7 2916.11
  580.98 2916.92   583.8 2918.05   599.8 2918.68   656.1 2918.91   732.4 2916.41
   760.5 2913.72   768.5 2915.13   780.5 2920.41   788.6 2921.74   864.4 2922.46
   901.1 2924.08   909.1 2923.53   933.2 2935.24   961.3  2936.6988.2475 2939.26
#Mann= 8 ,-1,0
       0     .05       0      30     .08       0     450     .05       0
   543.6    .045       0  580.98     .08       0  646.24     .05       0
  846.24     .06       0  946.24      .1       0
#XS Ineff= 2 , 0
          445.63 2923.64  749.17         2923.67
Permanent Ineff=
       F       F
Bank Sta=543.6,580.98
XS Rating Curve= 0 ,0
Exp/Cntr(USF)=0,0
Exp/Cntr=0.3,0.1

Type RM Length L Ch R = 1 ,25943   ,264.1,258,250.3
XS GIS Cut Line= 5
 2240398.6372583517520.6327792582240162.39667572517786.690134396
2240068.35916226517979.3523570832239677.30072217518260.318098501
2239637.16275911518455.273919077
#Sta/Elev= 30
       0 2945.02    50.3 2932.09    92.8 2927.03   136.2 2924.58   385.3 2922.69
   403.1 2921.68   425.1 2915.96   443.1 2915.18   469.8 2917.75   532.2 2917.51
   575.3 2919.18   588.8 2917.81   603.2 2913.08   617.5 2914.06   641.9 2910.84
   678.8 2912.76   688.6 2915.38  704.32 2913.46  730.66 2913.49     738 2914.31
   826.7 2912.28   934.9    2912   949.7 2910.04   964.3 2910.03   990.1  2911.4
  1010.1 2910.42  1046.3 2914.39  1085.3 2915.08    1220 2926.261250.762 2925.75
#Mann= 11 ,-1,0
       0      .1       0      20     .07       0     150     .08       0
  650.19     .05       0  704.32    .045       0  730.66     .05       0
  770.19     .08       0  820.19     .05       0  890.19     .08       0
 1121.72     .07       0 1221.72     .06       0
#XS Ineff= 2 , 0
          690.14 2919.25  983.72         2920.06
Permanent Ineff=
       F       F
Bank Sta=704.32,730.66
XS Rating Curve= 0 ,0
Exp/Cntr(USF)=0,0
Exp/Cntr=0.3,0.1

Type RM Length L Ch R = 1 ,25685   ,229,240.3,242.2
XS GIS Cut Line= 3
2239917.69104422517715.5131014332239492.46522699 518218.78669524
2239473.62610851518388.338761603
#Sta/Elev= 30
       0 2921.63    73.2 2916.04    98.8 2915.64   101.7 2915.23   112.2 2908.94
   117.4 2907.22   138.5 2907.94   152.7  2910.8   244.1 2909.74   269.2 2909.76
   290.2 2910.11   299.8 2907.69     306 2907.16   318.4 2909.94   347.8 2909.94
   368.7 2908.46   380.4 2909.99   405.2 2906.57   417.6  2909.8   436.5 2910.11
   447.3 2909.83   462.1 2907.72     484 2910.57   527.4 2908.47   541.5 2910.97
   578.2 2909.41   609.6  2909.6   635.8 2911.64   737.7 2914.93   829.5 2922.28
#Mann= 8 ,-1,0
       0     .08       0   244.1    .045       0   269.2     .08       0
     320      .1       0     410     .08       0     630     .05       0
  668.86     .08       0  768.86     .07       0
#XS Ineff= 2 , 0
                          544.85         2913.16
Permanent Ineff=
       F       F
Bank Sta=244.1,269.2
XS Rating Curve= 0 ,0
Exp/Cntr(USF)=0,0
Exp/Cntr=0.3,0.1

Type RM Length L Ch R = 1 ,25444   ,165.6,154.4,141.5
XS GIS Cut Line= 5
2239655.51154222 517513.751985592239591.29080132517669.716642051
2239577.52921399517826.8280974562239528.21685937517863.525663682
2239420.41775858518389.906379237
#Sta/Elev= 30
       0 2932.95    98.9 2923.14   133.5 2917.33   172.1 2907.67   199.9 2906.52
   222.7 2906.68   236.4 2905.68   244.4 2906.83   276.5 2904.02   280.6 2904.05
   284.6 2905.43   288.6 2907.94     329 2908.02   333.1 2907.88  339.15 2905.46
   343.7 2903.72   357.1 2903.34     368    2904   371.9 2905.49   377.9 2907.42
   389.5  2907.8   504.5 2908.14   521.5 2907.46   540.6 2905.72   568.9 2908.24
   629.9 2909.25   687.7 2908.97   724.3 2911.47   843.4 2916.19925.1566 2921.12
#Mann= 8 ,-1,0
       0     .08       0     130      .1       0  339.15    .045       0
   371.9      .1       0  457.85     .08       0  657.85     .05       0
  757.85     .08       0  857.85     .07       0
#XS Ineff= 2 , 0
             320  2912.8  636.21         2912.56
Permanent Ineff=
       F       F
Bank Sta=339.15,371.9
XS Rating Curve= 0 ,0
Exp/Cntr(USF)=0,0
Exp/Cntr=0.3,0.1

Type RM Length L Ch R = 1 ,25290   ,262.6,246.5,233
XS GIS Cut Line= 3
2239573.20430621517529.8132192262239296.00013422518027.704207752
2239220.64366028 518337.20401143
#Sta/Elev= 30
       0 2929.06   104.6 2921.04   122.9 2917.86   145.8 2908.39   164.1 2903.99
     187 2905.64   191.6 2904.87   198.22902.149   220.9 2901.33   232.8 2902.13
   238.5 2904.77   256.1 2905.85   282.6 2902.53   298.1 2905.17   359.1 2905.41
   374.7 2906.52   411.3 2905.03     462 2906.27   509.1 2904.87   550.2 2907.23
   583.7 2906.24   608.4 2907.33     629 2905.69   674.3 2907.01   752.5 2907.52
   764.9    2908   797.8 2912.12   863.7 2914.28     876 2915.38   888.4 2917.72
#Mann= 8 ,-1,0
       0     .05       0      10     .08       0     120      .1       0
   198.2    .045       0   232.8      .1       0     350     .08       0
     530     .05       0  879.86     .06       0
#XS Ineff= 2 , 0
                          558.14         2910.64
Permanent Ineff=
       F       F
Bank Sta=198.2,232.8
XS Rating Curve= 0 ,0
Exp/Cntr(USF)=0,0
Exp/Cntr=0.3,0.1

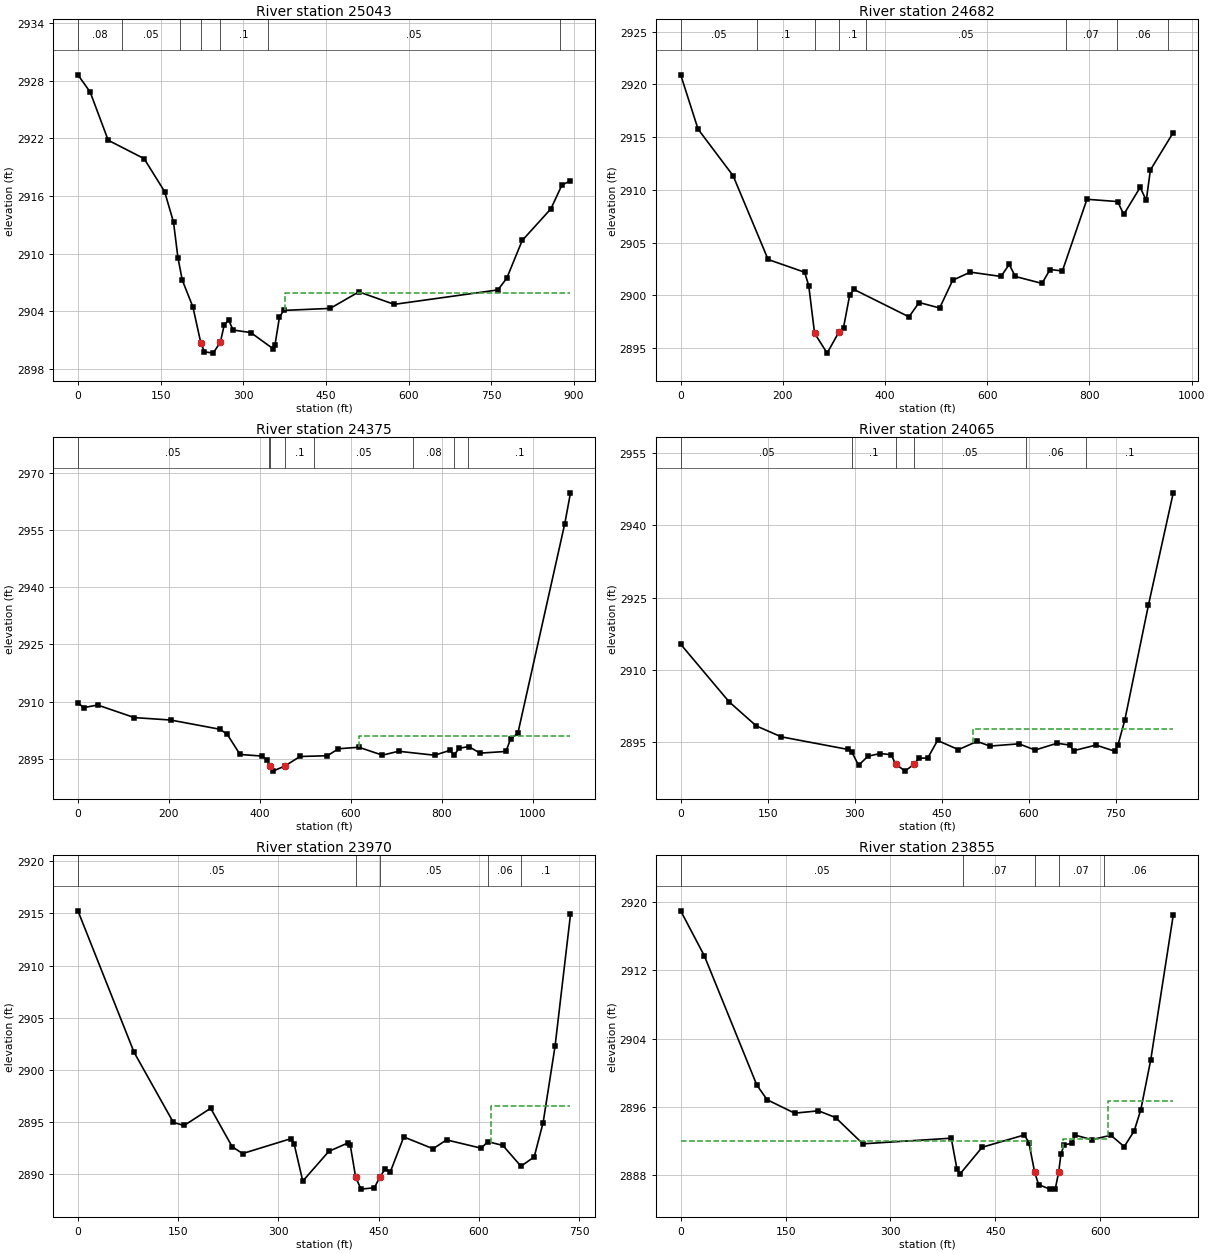
Type RM Length L Ch R = 1 ,25043   ,361.8,361.8,360.8
XS GIS Cut Line= 3
2239264.15900475517455.4056142432239228.90233484517626.138282158
2239197.35248127518344.701825853
#Sta/Elev= 30
       0 2928.59    22.2  2926.8    54.9 2921.79     120 2919.88   157.2 2916.46
   173.4 2913.28   181.4  2909.6   189.3 2907.25   208.6 2904.46   222.8 2900.76
   229.4  2899.8   245.4 2899.66   258.5 2900.81   265.5 2902.62   273.5 2903.09
   281.5 2902.06   313.5  2901.8   353.5 2900.14   357.6 2900.54   365.6  2903.4
   373.3  2904.1   457.6 2904.31   509.7 2906.03   573.8 2904.73   761.9 2906.23
     778 2907.45     806 2911.37     858 2914.66   878.1 2917.14   893.6 2917.57
#Mann= 7 ,-1,0
       0     .08       0      80     .05       0  184.33      .1       0
   222.8    .045       0   258.5      .1       0  344.33     .05       0
  874.33     .06       0
#XS Ineff= 2 , 0
                          376.02         2905.95
Permanent Ineff=
       F       F
Bank Sta=222.8,258.5
XS Rating Curve= 0 ,0
Exp/Cntr=0.3,0.1

Type RM Length L Ch R = 1 ,24682   ,307,307.1,307.3
XS GIS Cut Line= 3
2239004.79359514517413.456630982 2238869.9796278517604.028728541
2238839.92253871518333.948399733
#Sta/Elev= 30
       0  2920.9      34 2915.75   102.6 2911.33   171.1 2903.39   242.6 2902.18
   250.6 2900.91     262  2896.4   286.6 2894.51   309.3 2896.48   318.7 2896.94
   330.7    2900   338.7 2900.56   446.8 2897.95   466.6 2899.31   506.8 2898.79
   532.3 2901.42   566.8 2902.19   626.9 2901.78   642.9 2902.92   654.9 2901.78
     707 2901.12     723 2902.44     747  2902.3   795.1  2909.1   855.1 2908.88
   867.1 2907.66   899.2 2910.23   911.2 2908.99   919.2 2911.87     964 2915.43
#Mann= 8 ,-1,0
       0     .05       0     150      .1       0     262    .045       0
   309.3      .1       0  363.44     .05       0  753.44     .07       0
  853.44     .06       0  953.44      .1       0
Bank Sta=262,309.3
XS Rating Curve= 0 ,0
Exp/Cntr=0.3,0.1

Type RM Length L Ch R = 1 ,24375   ,309.4,309.4,308.9
XS GIS Cut Line= 4
2238781.41163337517297.0463128782238569.04145846517522.001387052
2238553.31033439517830.3314187862238281.16188801 518207.87839642
#Sta/Elev= 30
       0 2909.59    13.5 2908.45    43.4 2909.11   124.2 2905.81   203.7 2905.18
   312.5 2902.75   328.5 2901.42   356.6 2896.14   404.7 2895.72   416.7  2894.7
   421.5 2893.01   428.7 2891.77  454.88 2893.08   488.5 2895.61   548.9 2895.81
   572.9 2897.64   618.1 2898.03   669.7 2895.96   705.4 2896.98   784.6 2895.94
   818.4 2897.22   827.3    2896   838.7 2897.75   859.5 2898.23   884.6 2896.49
   941.5 2896.93     952 2900.27   967.7 2901.69  1070.8 2956.621083.505 2964.78
#Mann= 8 ,-1,0
       0     .05       0  419.36      .1       0   421.5    .045       0
  454.88      .1       0  519.36     .05       0  738.09     .08       0
  828.09     .06       0  858.09      .1       0
#XS Ineff= 2 , 0
                          617.58         2900.97
Permanent Ineff=
       F       F
Bank Sta=421.5,454.88
XS Rating Curve= 0 ,0
Exp/Cntr(USF)=0,0
Exp/Cntr=0.3,0.1

Type RM Length L Ch R = 1 ,24065   ,96.9,94.8,92.7
XS GIS Cut Line= 4
2238355.09817113517254.5722778942238262.28453913517514.135825018
2238244.98030265517886.9634654312238126.99687214518048.994043332
#Sta/Elev= 30
       0 2915.28    83.5  2903.3   130.2  2898.3   173.3 2896.02   288.2  2893.4
   294.7 2892.95   306.7 2890.09   322.8 2891.98   343.8 2892.54   362.8  2892.3
   370.4  2890.4   386.8 2888.88   402.8 2890.36   410.8 2891.56     426 2891.62
   442.9 2895.26   478.9 2893.35     511 2895.07   533.1 2894.09   583.2 2894.56
   611.1 2893.27   648.9 2894.68   670.6  2894.3   677.4 2893.13     716  2894.3
   748.4 2893.03   754.1 2894.38   765.8 2899.53   806.5 2923.44   849.3 2946.79
#Mann= 6 ,-1,0
       0     .05       0  295.66      .1       0   370.4    .045       0
   402.8     .05       0  595.66     .06       0  698.89      .1       0
#XS Ineff= 2 , 0
                          503.32         2897.75
Permanent Ineff=
       F       F
Bank Sta=370.4,402.8
XS Rating Curve= 0 ,0
Exp/Cntr(USF)=0,0
Exp/Cntr=0.3,0.1

Type RM Length L Ch R = 1 ,23970   ,110,115.7,117.5
BEGIN DESCRIPTION:
xs 4
END DESCRIPTION:
XS GIS Cut Line= 4
2238316.60400628517238.8924972762238160.75402972517513.436164607
2238164.88250592517770.4338080872238048.25305325517886.031141701
#Sta/Elev= 30
       0 2915.24    84.1 2901.67   142.8 2894.96     159 2894.67   198.6 2896.32
   230.8 2892.63   246.4 2891.98   319.4 2893.42   323.4 2892.92   336.4 2889.34
   375.4 2892.19   403.4 2892.98   407.4 2892.81   415.5 2889.72   423.5 2888.57
   443.5  2888.7   451.5  2889.7   459.5 2890.49   467.5 2890.24   487.5 2893.57
   531.4 2892.44   551.5 2893.29   603.5 2892.49   613.1 2893.12   635.7 2892.76
   662.8 2890.77   682.6 2891.65     696 2894.95   713.8 2902.25736.9367 2914.89
#Mann= 5 ,-1,0
       0     .05       0   415.5    .045       0   451.5     .05       0
   613.1     .06       0   662.8      .1       0
#XS Ineff= 2 , 0
                          618.29         2896.57
Permanent Ineff=
       F       F
Bank Sta=415.5,451.5
XS Rating Curve= 0 ,0
Exp/Cntr(USF)=0,0
Exp/Cntr=0.5,0.3

Type RM Length L Ch R = 1 ,23855   ,21.8,21.4,20.9
BEGIN DESCRIPTION:
xs 3
END DESCRIPTION:
XS GIS Cut Line= 4
2238286.16400883517200.1318704192238065.66283603517513.331297463
2238043.72242082517723.959283427 2237984.9446356517816.408901974
#Sta/Elev= 30
       0 2918.95    33.8 2913.69   108.9 2898.56   123.6 2896.85   162.9 2895.28
     197 2895.55   221.4 2894.77   260.5 2891.69   386.9 2892.35   394.9  2888.8
     399 2888.12   431.1 2891.29   491.5 2892.73   497.9 2891.81  506.02 2888.43
   511.7 2886.93   527.7 2886.39   535.7 2886.45  540.46 2888.36   543.7 2890.46
   548.2 2891.58   559.8 2891.74   563.9 2892.71   587.7 2892.18   615.2 2892.69
   634.2 2891.36   648.4 2893.18   657.9 2895.67   672.1 2901.49704.3536 2918.46
#Mann= 5 ,-1,0
       0     .05       0  403.03     .07       0  506.02    .045       0
  540.46     .07       0   604.8     .06       0
#XS Ineff= 3 ,-1
       0   500.4 2891.99   546.2  611.61 2892.28  611.61704.3536 2896.65
Permanent Ineff=
       F       F       F
Bank Sta=506.02,540.46
XS Rating Curve= 0 ,0
Exp/Cntr(USF)=0,0
Exp/Cntr=0.5,0.3

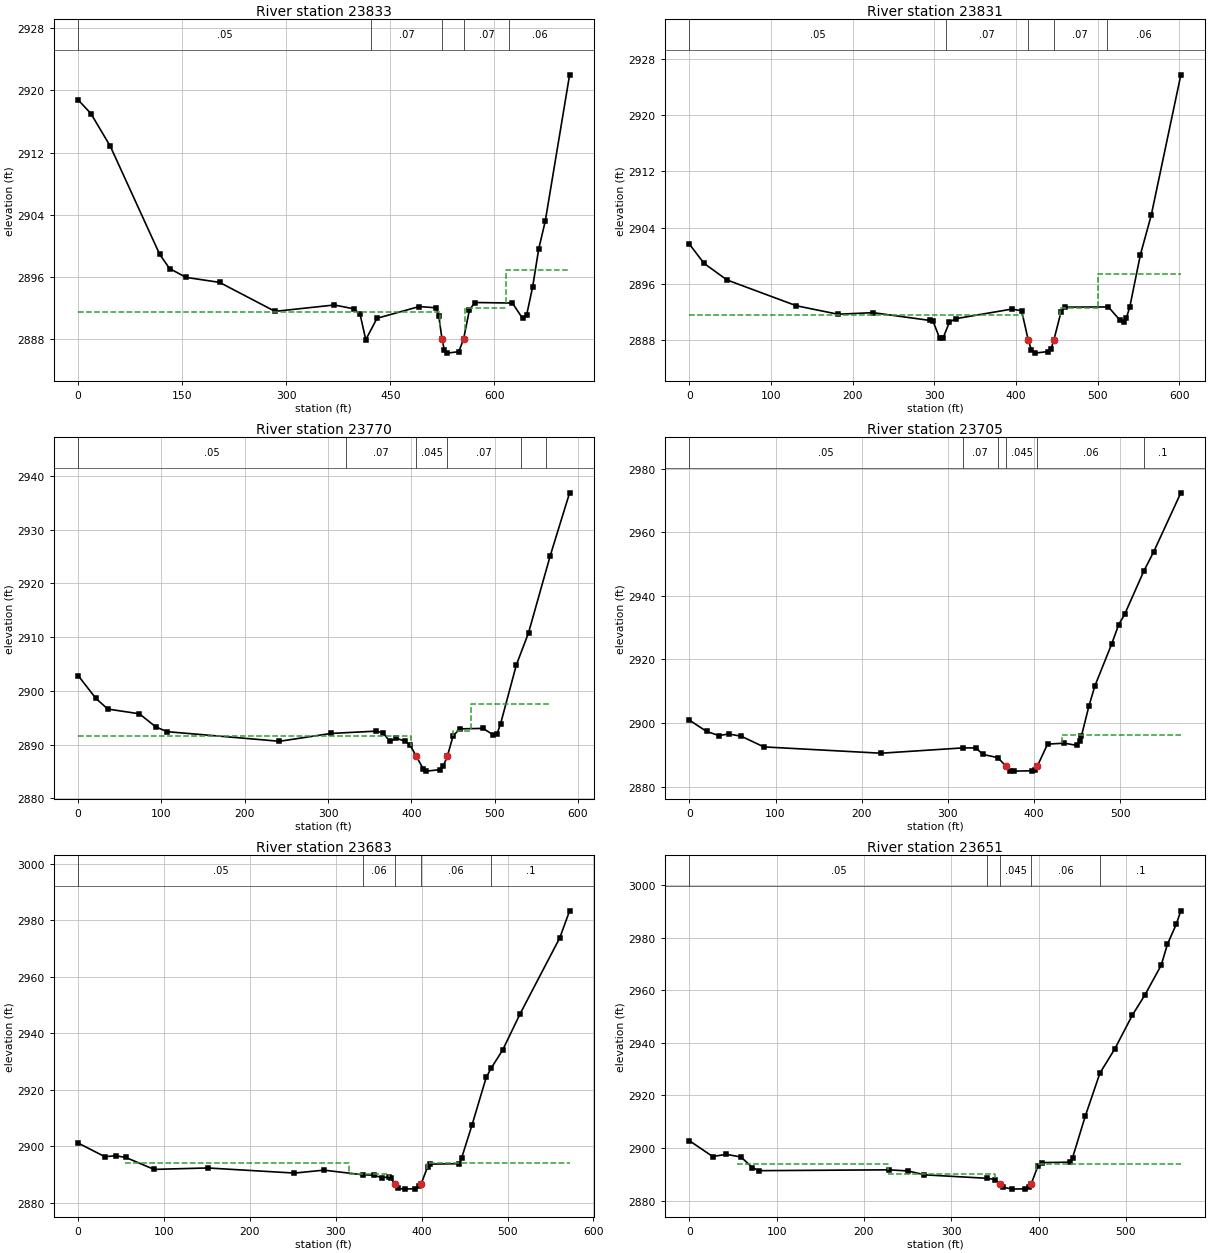
Type RM Length L Ch R = 1 ,23833   ,2.8,2.3,2.3
BEGIN DESCRIPTION:
xs 2
END DESCRIPTION:
XS GIS Cut Line= 5
2238266.60577082517178.1354326662238049.91031201517516.722087057
2238031.58405066 517630.683557462238023.30686447517724.611626822
 2237972.9281309517807.172051504
#Sta/Elev= 30
       0 2918.79    18.4 2917.03    46.4 2912.82   117.6 2898.92   131.8  2897.1
   155.6 2895.96   203.8 2895.32   283.8 2891.59   369.3 2892.41   397.8 2891.91
   406.5 2891.19   414.6 2887.94   430.8  2890.7   491.6 2892.21   515.9 2892.05
   519.9 2890.99  524.54 2887.99     528 2886.59     532 2886.22   548.7 2886.41
  555.55 2888.01   564.1 2891.81   572.1 2892.73     626 2892.66   640.6 2890.69
   646.4 2891.09   655.1 2894.71   663.9 2899.62   673.3 2903.18708.4273 2922.01
#Mann= 5 ,-1,0
       0     .05       0  421.99     .07       0  524.54    .045       0
  555.55     .07       0  621.71     .06       0
#XS Ineff= 3 ,-1
       0   521.9  2891.5   558.3  617.01    2892  617.01708.4273 2896.86
Permanent Ineff=
       F       F       F
Bank Sta=524.54,555.55
XS Rating Curve= 0 ,0
Exp/Cntr(USF)=0,0
Exp/Cntr=0.5,0.3

Type RM Length L Ch R = 1 ,23831   ,66.3,61.4,56.2
BEGIN DESCRIPTION:
xs 3
END DESCRIPTION:
XS GIS Cut Line= 6
2238192.38598074 517265.765349632238098.68084882517419.749080609
 2238048.3412518517496.8315885432238039.64961777517516.491733983
2238021.06096163517722.8870201232237966.27888897517807.639814977
#Sta/Elev= 30
       0 2901.66      18 2898.92    46.1 2896.56   131.2 2892.89     182 2891.69
     225 2891.91   294.5 2890.81   298.5 2890.69   306.6 2888.27   310.6 2888.24
   318.6 2890.59   326.6 2891.06   394.9 2892.42     407 2892.18     415 2888.06
     419 2886.59     423 2886.16   439.1 2886.38   443.1 2886.81  446.51 2888.03
   455.2 2892.01   459.8  2892.7   513.3 2892.72   527.6 2890.82   532.3 2890.57
   535.2 2891.12   539.5 2892.74   552.5 2900.17   565.7 2905.74     602 2925.72
#Mann= 5 ,-1,0
       0     .05       0  313.81     .07       0     415    .045       0
  446.51     .07       0  511.04     .06       0
#XS Ineff= 3 ,-1
       0     409 2891.63   453.9  500.45 2892.54  500.45     602  2897.4
Permanent Ineff=
       F       F       F
Bank Sta=415,446.51
XS Rating Curve= 0 ,0
Exp/Cntr(USF)=0,0
Exp/Cntr=0.5,0.3

Type RM Length L Ch R = 1 ,23770   ,43.9,65,85.3
BEGIN DESCRIPTION:
xs 2
END DESCRIPTION:
XS GIS Cut Line= 5
2238138.62647838517255.1023078412238009.01344163517459.076890779
2237971.25874387517569.1947592562237969.68563146517712.347988275
 2237921.6171961517786.897953697
#Sta/Elev= 30
       0 2902.85    21.4 2898.58    35.6 2896.61    73.5 2895.73    93.1  2893.3
   106.7  2892.4   241.7 2890.61   303.8 2892.07   358.1  2892.5   366.1 2892.15
   374.1 2890.58   382.1 2891.17   392.8 2890.59   398.1 2889.97406.02472887.793
   414.1 2885.49   418.1 2885.05   434.1 2885.32   438.1 2885.92443.14472887.814
   450.1 2891.63   458.1 2892.92   486.1 2893.01   498.1 2891.81   502.9 2892.04
     507 2893.84     526 2904.84   540.6 2910.81   566.6 2925.14   589.9 2936.88
#Mann= 6 ,-1,0
       0     .05       0  321.67     .07       0406.0247    .045       0
443.1447     .07       0  531.24     .06       0  561.24      .1       0
#XS Ineff= 3 ,-1
       0     399  2891.5   450.1  471.55  2892.5  471.55  566.54 2897.64
Permanent Ineff=
       F       F       F
Bank Sta=406.0247,443.1447
XS Rating Curve= 0 ,0
Exp/Cntr(USF)=0,0
Exp/Cntr=0.5,0.3

Type RM Length L Ch R = 1 ,23705   ,21.5,21.6,23.2
BEGIN DESCRIPTION:
xs 4
END DESCRIPTION:
XS GIS Cut Line= 4
2238122.08305253517264.2016126862237999.49646768 517457.78738114
2237960.55223069517536.7728758762237814.64846958517743.561289179
#Sta/Elev= 30
       0 2900.89    20.1 2897.33    34.3 2896.04    45.6 2896.53    60.1 2895.85
    86.4 2892.48   222.4 2890.49   317.2 2892.16   332.4 2892.16   340.7 2890.11
   357.9  2889.1   367.2 2886.48   372.3 2885.05   376.4 2884.86   398.1 2884.97
   400.9 2885.24   403.9  2886.5   415.6 2893.35   435.2 2893.65   449.7 2892.94
   452.7 2894.32   454.8 2895.75   463.6 2905.29   470.5 2911.61     490 2924.82
   498.2 2930.93   505.2 2934.23   527.3 2947.74   538.8 2953.83570.2794 2972.36
#Mann= 6 ,-1,0
       0     .05       0   317.2     .07       0   357.9     .06       0
   367.2    .045       0   403.9     .06       0   527.3      .1       0
#XS Ineff= 2 , 0
                          432.29         2896.37
Permanent Ineff=
       F       F
Bank Sta=367.2,403.9
XS Rating Curve= 0 ,0
Exp/Cntr(USF)=0,0
Exp/Cntr=0.5,0.3

Type RM Length L Ch R = 1 ,23683   ,33.2,32.1,30.6
BEGIN DESCRIPTION:
xs 3
END DESCRIPTION:
XS GIS Cut Line= 3
2238114.74398365517263.2362344172237917.21991066517563.101374122
2237785.02890906517730.397040057
#Sta/Elev= 30
       0 2901.15    31.1 2896.32    43.7 2896.65    55.6 2896.04    88.5 2891.82
   150.8 2892.33   251.9 2890.52   286.2 2891.56   331.9  2889.9     344 2889.78
   353.7 2888.91   361.7 2889.11   364.1 2888.79  368.44 2886.81   371.9  2885.1
   380.1 2884.84   392.3 2885.01   397.4 2885.79   399.5 2886.75   406.9  2892.7
   409.7 2893.69   443.9 2893.84   446.7    2896   458.6 2907.46   475.2 2924.38
   480.9 2927.62   494.3 2934.03   514.7 2946.91   560.8 2973.73572.2939 2983.32
#Mann= 5 ,-1,0
       0     .05       0   331.9     .06       0  368.44    .045       0
   399.5     .06       0   480.9      .1       0
#XS Ineff= 3 ,-1
      55     315 2894.16     315   361.8  2890.3   406.1572.2939 2894.15
Permanent Ineff=
       F       F       F
Bank Sta=368.44,399.5
XS Rating Curve= 0 ,0
Exp/Cntr(USF)=0,0
Exp/Cntr=0.5,0.3

Type RM Length L Ch R = 1 ,23651   ,119.6,120.1,121.6
BEGIN DESCRIPTION:
xs 2
END DESCRIPTION:
XS GIS Cut Line= 2
 2238099.0949825517258.8481513762237766.92806651517713.393218273
#Sta/Elev= 30
       0 2902.77    26.7 2896.74    42.5 2897.58    59.2 2896.53    72.2 2892.56
    79.5 2891.36   228.7 2891.68   250.6 2891.25   269.3 2889.78   341.5 2888.45
   349.7    2888   355.8 2886.33   359.6 2885.08   369.5 2884.34   384.6 2884.47
   389.3 2885.03   391.4 2886.14   399.2 2893.08   404.2 2894.43     436 2894.58
   438.9 2896.23   453.7 2912.29   470.3 2928.47   487.5 2937.78   507.5 2950.54
   521.9 2958.22   540.5 2969.52   547.6 2977.45   557.8 2985.14562.9796 2990.19
#Mann= 5 ,-1,0
       0     .05       0   341.5     .06       0   355.8    .045       0
   391.4     .06       0   470.3      .1       0
#XS Ineff= 3 ,-1
   54.92  227.15 2894.07  227.15   349.8 2890.15   397.4562.9796    2894
Permanent Ineff=
       F       F       F
Bank Sta=355.8,391.4
XS Rating Curve= 0 ,0
Exp/Cntr(USF)=0,0
Exp/Cntr=0.5,0.3