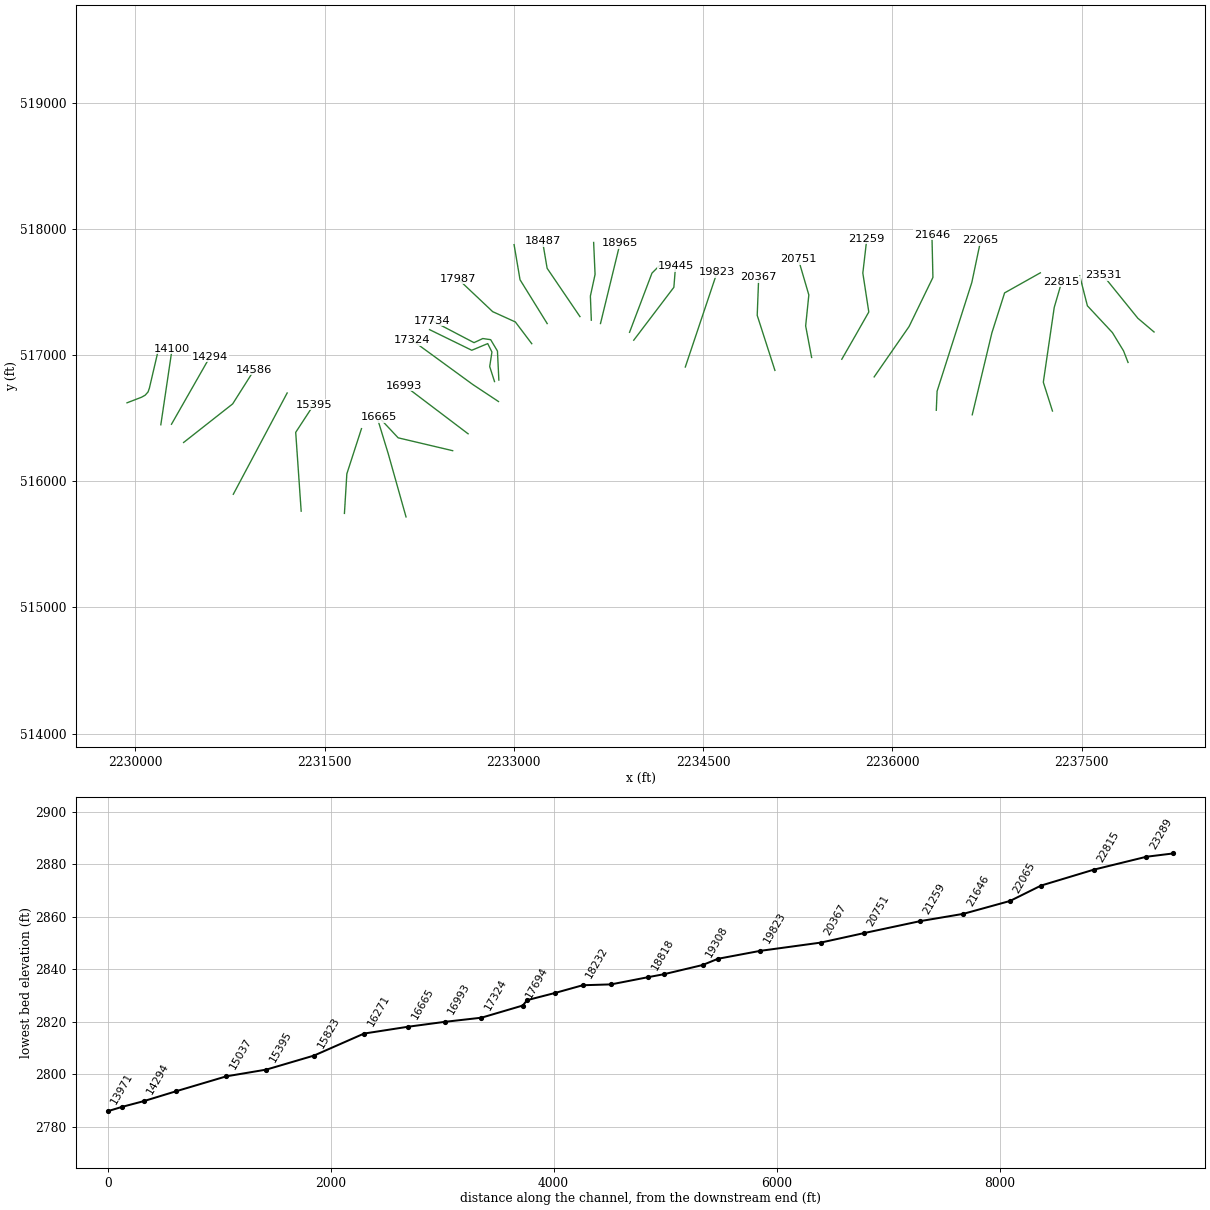
HEC-RAS study BIGSPRFK.prj: BIGSPRFK

--- BIGSPRFK.g01 (geometry) --- (continued)

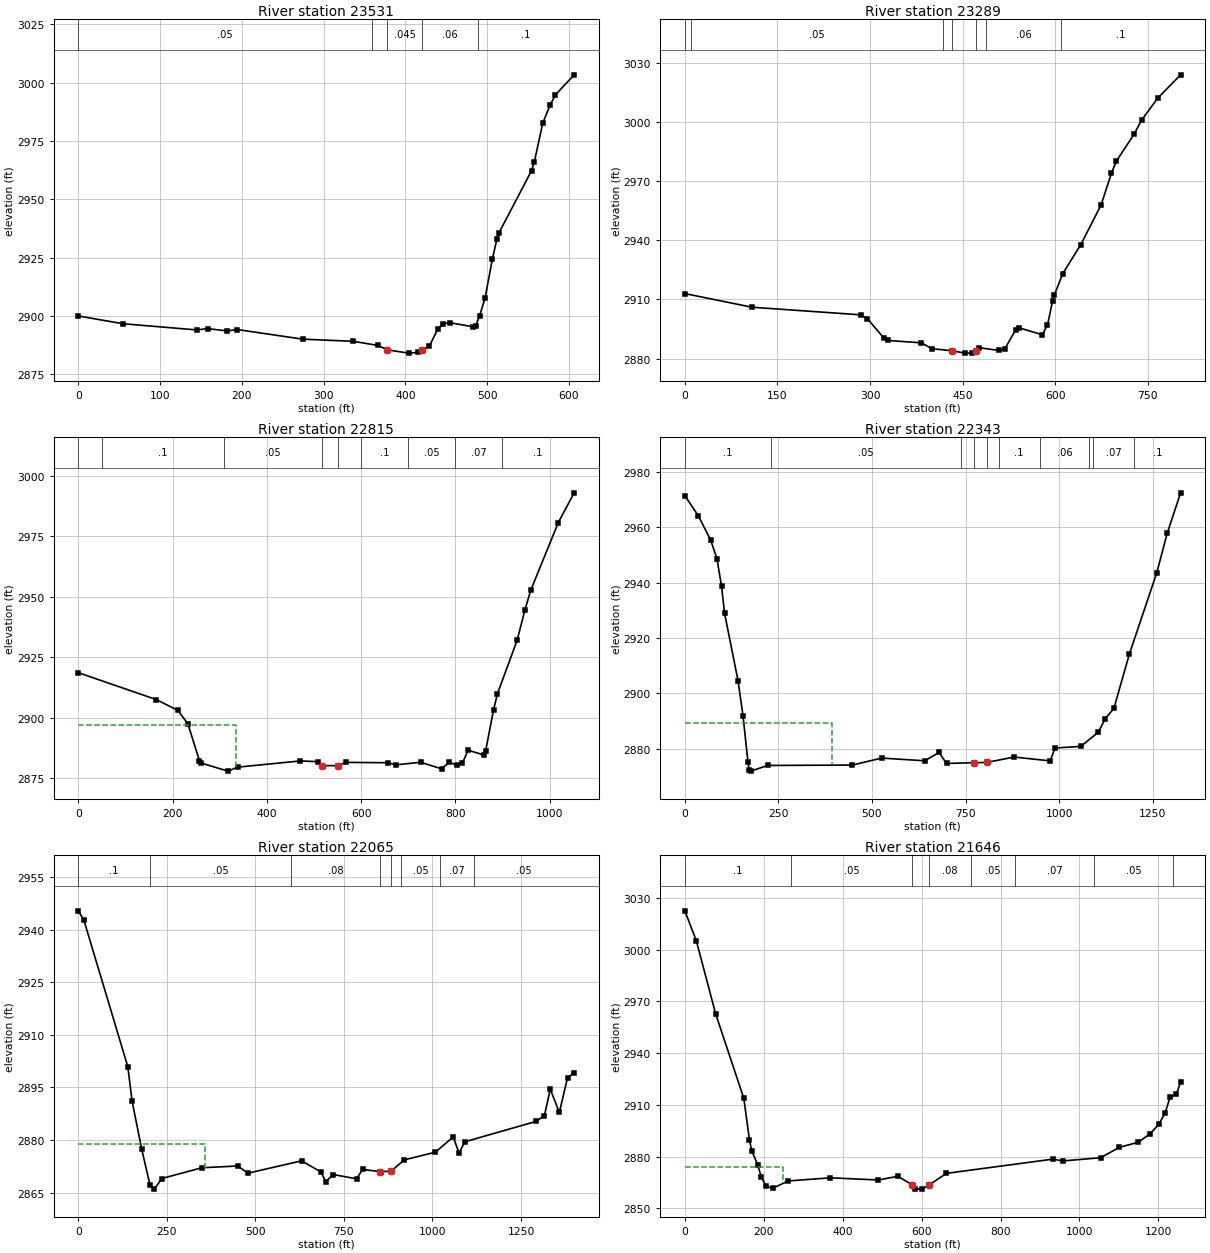
Type RM Length L Ch R = 1 ,23531   ,239.5,242.2,244.4
BEGIN DESCRIPTION:
xs 1
END DESCRIPTION:
XS GIS Cut Line= 3
2238072.77284131 517181.794986542237944.10991265517290.895130733
2237668.72610041  517630.9866147
#Sta/Elev= 30
       0 2900.01    54.7 2896.68   144.7 2894.04   158.1 2894.58   181.9  2893.6
     194 2894.21   274.6 2890.07   336.3 2889.15   366.5 2887.37   377.5 2885.52
   403.8 2884.09   414.9  2884.4   420.5 2885.54   429.1 2886.96   439.3 2894.28
   446.1 2896.75   454.6  2897.1   483.1 2895.36     486 2895.82   490.7 2900.12
   497.3  2907.6   506.2 2924.23   511.8 2932.96   514.4 2935.63   554.2 2962.29
   557.6 2966.02   567.9 2982.66     577 2990.46   583.4 2994.78606.2974 3003.34
#Mann= 5 ,-1,0
       0     .05       0  358.69     .06       0   377.5    .045       0
   420.5     .06       0  488.69      .1       0
Bank Sta=377.5,420.5
XS Rating Curve= 0 ,0
Exp/Cntr(USF)=0,0
Exp/Cntr=0.3,0.1

Type RM Length L Ch R = 1 ,23289   ,498.3,473.3,441.4
XS GIS Cut Line= 5
2237866.66539132516940.3728526092237830.85900104 517032.33832134
2237742.76470626517177.064662767  2237544.552543517389.434837686
2237483.99435309517626.137077423
#Sta/Elev= 30
       0 2912.98     109 2906.06   284.7 2902.22   295.4 2900.32     323 2890.26
   328.5 2889.23   383.2 2888.03   400.2 2885.05   432.4 2884.05   453.6 2882.82
   465.3 2882.84   471.2 2884.11   477.1 2885.55     509 2884.16   518.1 2884.91
   535.7 2894.61   541.7 2895.61     579  2892.1   587.3 2897.05   595.5 2909.12
   598.2 2912.06     612  2923.1     641 2937.65     674 2957.78   690.9 2973.97
   698.7    2980   727.6 2993.72     740 3000.98   765.8 3011.96   802.9 3023.78
#Mann= 7 ,-1,0
       0     .06       0      10     .05       0  418.12     .07       0
   432.4    .045       0   471.2     .07       0  488.12     .06       0
  608.62      .1       0
Bank Sta=432.4,471.2
XS Rating Curve= 0 ,0
Exp/Cntr=0.3,0.1

Type RM Length L Ch R = 1 ,22815   ,474.5,471.8,464.7
XS GIS Cut Line= 4
 2237267.6847594516555.6852620772237195.32158869516783.786561064
2237281.84277106517376.8499384322237341.62104252517581.354551317
#Sta/Elev= 30
       0 2918.57   165.2 2907.47   211.1 2902.99   232.4 2897.44   256.9 2882.21
   260.9 2881.19   317.5 2877.89   337.7 2879.53   471.1  2882.1   507.5  2881.8
  517.69 2880.18     550 2880.15   568.1  2881.5   657.1 2881.36   673.2 2880.47
   725.8 2881.55   770.4 2878.85   786.4 2881.51   802.6 2880.44   814.7 2881.26
   826.9 2886.53   859.8 2884.58     864 2886.31   880.7 2903.19     889 2909.88
   930.7 2931.94   947.3 2944.52   959.8 2952.72    1018 2980.571051.708 2992.89
#Mann= 9 ,-1,0
       0     .08       0      50      .1       0   309.3     .05       0
  517.69    .045       0     550     .05       0   599.3      .1       0
   699.3     .05       0   799.3     .07       0  898.65      .1       0
#XS Ineff= 2 , 0
          334.88 2896.88
Permanent Ineff=
       F       F
Bank Sta=517.69,550
XS Rating Curve= 0 ,0
Exp/Cntr(USF)=0,0
Exp/Cntr=0.3,0.1

Type RM Length L Ch R = 1 ,22343   ,278,278.5,277.6
XS GIS Cut Line= 4
2236632.14734705516525.7961263482236787.88547532 517175.49155036
2236888.56466936517491.6871441292237171.72490258517650.571497216
#Sta/Elev= 30
       0  2971.5    36.4 2964.12    69.3 2955.34    85.8 2948.74    98.1 2938.76
   106.3 2928.89   142.2 2904.55   155.5 2891.85   168.7 2875.19   172.1 2872.32
   176.2 2871.85   221.5  2873.9   447.7 2874.04   525.9 2876.57     641 2875.59
   679.2  2878.6   699.3 2874.62   771.6  2874.9   806.6 2874.99   879.8 2876.94
   976.3 2875.55   988.9 2880.22  1057.7 2880.78    1105 2885.93  1123.3 2890.86
  1146.3 2894.51  1187.5 2914.09  1260.9 2943.59  1289.1 2958.011324.628 2972.49
#Mann= 10 ,-1,0
       0      .1       0     230     .05       0   738.1    .025       0
   771.6    .045       0   806.6    .025       0   838.1      .1       0
   948.1     .06       0 1079.94     .05       0 1089.94     .07       0
 1199.94      .1       0
#XS Ineff= 2 , 0
          393.02 2889.27
Permanent Ineff=
       F       F
Bank Sta=771.6,806.6
XS Rating Curve= 0 ,0
Exp/Cntr(USF)=0,0
Exp/Cntr=0.3,0.1

Type RM Length L Ch R = 1 ,22065   ,422.8,418.5,405.8
XS GIS Cut Line= 4
2236347.33617299 516561.541215572236353.62862262516712.560006624
2236628.92329381517574.6256055552236699.71335212517911.271660613
#Sta/Elev= 30
       0 2945.43    15.7 2942.76   139.8 2900.89   151.8 2891.09   179.1 2877.34
   202.2 2867.22   214.8 2865.99   235.8 2869.02   349.2  2872.1   449.9 2872.59
   479.3 2870.55   630.5 2874.07   685.1 2870.89   698.6 2868.11   720.2 2870.14
   785.9 2868.94   802.6 2871.62   850.7    2871   882.7  2871.1   920.7 2874.34
  1008.4 2876.54  1058.7 2880.91  1075.1 2876.24  1091.3  2879.5  1291.7  2885.3
  1316.2 2886.95  1332.6 2894.55  1358.2 2887.88  1381.6 2897.811400.114 2899.19
#Mann= 8 ,-1,0
       0      .1       0  201.15     .05       0  601.15     .08       0
   850.7    .045       0   882.7     .08       0  911.15     .05       0
 1021.15     .07       0 1116.11     .05       0
#XS Ineff= 2 , 0
           358.8 2878.97
Permanent Ineff=
       F       F
Bank Sta=850.7,882.7
XS Rating Curve= 0 ,0
Exp/Cntr(USF)=0,0
Exp/Cntr=0.3,0.1

Type RM Length L Ch R = 1 ,21646   ,360.6,387.5,408.7
XS GIS Cut Line= 4
2235854.95198966516825.8240999142236131.81977326517225.394651244
2236320.59326208517613.9534157262236312.72770004 517952.17258319
#Sta/Elev= 30
       0  3022.5    29.2 3005.17      78 2962.88   149.6 2913.67   163.7 2889.83
   169.5  2883.4   184.4 2875.36   193.9 2868.13   205.8 2862.81   223.1 2861.57
     262 2865.84   369.1 2867.65   490.3  2866.4   540.1 2868.52     576 2863.61
   583.7 2861.21   601.5 2861.09   619.3 2863.51   662.8 2870.23   933.3  2878.5
   957.3 2877.43  1053.4 2879.29  1101.4 2885.35  1148.5 2888.23  1179.1 2893.16
  1201.4 2898.76  1217.4 2905.38  1229.4 2914.29  1245.4    29161256.418 2923.18
#Mann= 8 ,-1,0
       0      .1       0     270     .05       0     576    .045       0
   619.3     .08       0  726.12     .05       0  836.12     .07       0
 1038.11     .05       0 1238.11      .1       0
#XS Ineff= 2 , 0
          248.84 2873.73
Permanent Ineff=
       F       F
Bank Sta=576,619.3
XS Rating Curve= 0 ,0
Exp/Cntr(USF)=0,0
Exp/Cntr=0.3,0.1

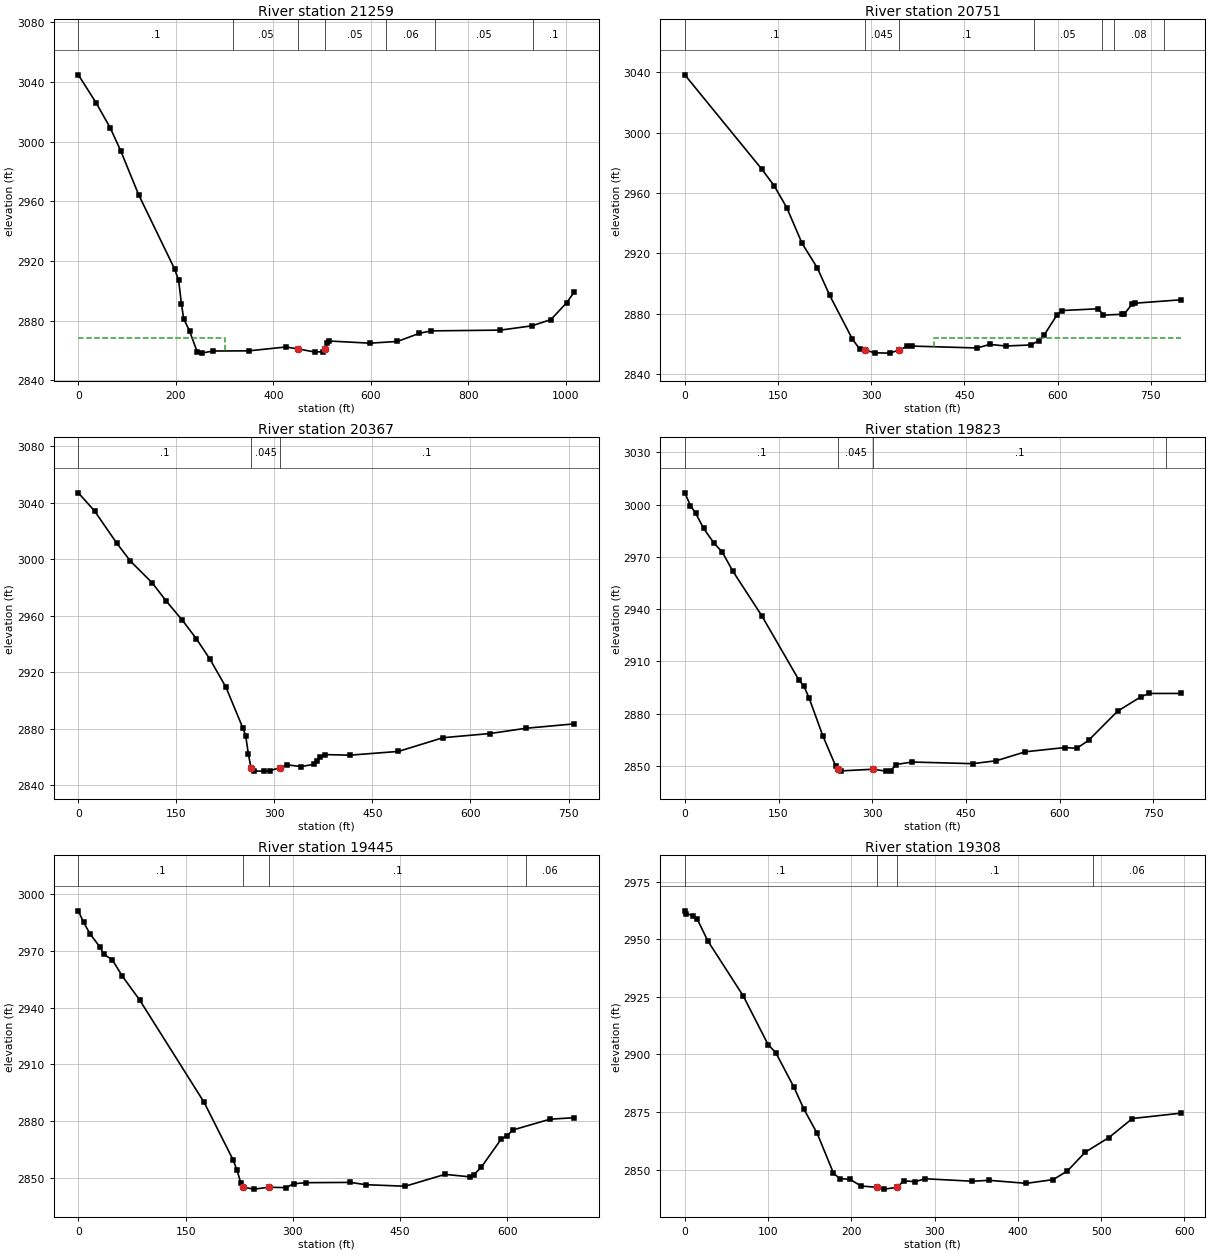
Type RM Length L Ch R = 1 ,21259   ,514.3,507.5,492.8
XS GIS Cut Line= 5
2235598.53466735 516965.831104122235707.07942342517154.604592937
2235812.47795468517340.2318569412235765.28458247517648.561888676
2235796.74683061517920.710335054
#Sta/Elev= 30
       0 3044.78    36.2 3026.18    65.2 3009.39    86.9 2993.89   123.8 2964.38
   197.7 2914.54   205.8 2906.99   211.5 2891.38   216.1 2881.32   228.1 2873.21
   243.7 2859.24   252.9 2858.31   275.9 2859.73   349.5 2859.84   425.8 2862.42
   449.9  2861.2   484.8 2859.06     501 2859.26     505 2861.22   509.1 2864.94
   513.2 2866.44   598.1 2864.98   654.7 2866.14   699.5 2871.57   723.5 2873.22
   865.4 2873.72   930.4  2876.6   969.3 2880.77  1001.5    2892  1017.1 2899.14
#Mann= 7 ,-1,0
       0      .1       0  317.76     .05       0   449.9    .045       0
     505     .05       0  631.22     .06       0  731.22     .05       0
  933.14      .1       0
#XS Ineff= 2 , 0
           300.7 2868.76
Permanent Ineff=
       F       F
Bank Sta=449.9,505
XS Rating Curve= 0 ,0
Exp/Cntr(USF)=0,0
Exp/Cntr=0.3,0.1

Type RM Length L Ch R = 1 ,20751   ,368.5,384.2,405
XS GIS Cut Line= 4
2235359.42158152516979.9891157812235312.22820931517230.113988464
2235337.39800782517475.5195239262235254.02305026517760.252869559
#Sta/Elev= 30
       0 3038.31   123.7 2975.85   143.7  2964.8     164 2950.29   188.7 2926.53
   213.2  2910.3   233.2 2892.03   269.7 2863.02   281.7 2856.29   290.1 2855.64
   305.9 2853.93     330 2853.72   344.8 2855.79   358.1 2858.25   366.2 2858.39
   470.7 2857.13   490.8 2859.51   516.5 2858.44   557.1 2859.14   569.6 2861.95
     578 2865.52   598.8 2878.94   606.7 2881.96   665.5 2883.14   673.8 2878.93
     703 2879.48   707.2  2879.7   719.7 2886.16   723.9 2886.83797.9202 2889.07
#Mann= 7 ,-1,0
       0      .1       0   290.1    .045       0   344.8      .1       0
  561.23     .05       0  671.23     .07       0  691.23     .08       0
  771.23     .07       0
#XS Ineff= 2 , 0
                          400.61         2863.87
Permanent Ineff=
       F       F
Bank Sta=290.1,344.8
XS Rating Curve= 0 ,0
Exp/Cntr(USF)=0,0
Exp/Cntr=0.3,0.1

Type RM Length L Ch R = 1 ,20367   ,569.9,544.4,519.2
XS GIS Cut Line= 3
2235068.69060122516877.4969501062234928.38878205517313.488946025
2234940.13569031517613.851135729
#Sta/Elev= 30
       0 3047.07    24.9 3034.18    58.5 3011.63    79.6  2998.8   113.1 2983.33
   134.1 2970.71   159.3 2956.82   180.4 2943.93   201.4 2929.32   225.9 2909.46
   251.8 2880.55     256 2875.26   260.2 2862.16  264.15 2852.57   268.6 2850.24
   283.7 2850.14   293.8 2850.56   308.5 2852.56     319 2854.64   340.3 2853.37
     361 2854.96   365.2    2857   369.4 2860.42   377.8 2861.84   415.7 2861.44
   489.7 2864.09   557.9 2873.79   629.8 2876.74   684.8 2880.47   758.6 2883.58
#Mann= 3 ,0,0
       0      .1       0  264.15    .045       0   308.5      .1       0
Bank Sta=264.15,308.5
XS Rating Curve= 0 ,0
Exp/Cntr=0.3,0.1

Type RM Length L Ch R = 1 ,19823   ,389.9,377.7,366.5
XS GIS Cut Line= 2
2234358.70679105516904.5097793922234611.08641885517656.815135729
#Sta/Elev= 30
       0 3006.74     9.1 2999.37    17.6 2994.89    30.2 2986.27    47.1 2977.66
    59.8 2972.84    76.6 2961.93   123.1 2936.23   182.1 2899.58   190.6 2895.79
     199  2888.9   220.9 2867.27   241.2 2850.11   244.9 2848.11   249.6 2847.11
   301.8 2848.09   321.4 2846.99   329.8 2847.32   338.2 2850.79   363.5 2852.22
   460.6 2851.27   498.6 2852.96     545 2858.09   608.3 2860.53   627.2 2860.07
   646.2 2864.66   692.6  2881.4   730.6  2889.8   743.3 2891.57   793.5 2891.59
#Mann= 4 ,-1,0
       0      .1       0   244.9    .045       0   301.8      .1       0
     770     .08       0
Bank Sta=244.9,301.8
XS Rating Curve= 0 ,0
Exp/Cntr=0.3,0.1

Type RM Length L Ch R = 1 ,19445   ,125.2,137.3,146.1
XS GIS Cut Line= 3
2233950.20452005517116.9480573882234268.09718749517535.988391732
2234281.25730945517702.879547547
#Sta/Elev= 30
       0 2991.26     7.3 2985.19    16.5 2979.01    30.4 2972.01    35.8 2968.16
    47.3 2965.48    61.5 2956.69    85.6 2944.17     176 2889.84   216.2 2859.64
   221.7 2854.25   227.1 2847.39     230 2844.97   246.3 2843.98   266.4    2845
   289.9 2844.77   301.5 2846.83   318.5 2847.39   380.5 2847.54     402 2846.32
   457.2 2845.52   512.9  2851.8   547.2 2850.49   553.2 2851.69   563.3 2855.45
   591.4 2870.49   599.4 2872.13   607.4 2875.25   659.6 2880.98   693.4 2881.78
#Mann= 4 ,-1,0
       0      .1       0     230    .045       0   266.4      .1       0
  625.98     .06       0
Bank Sta=230,266.4
XS Rating Curve= 0 ,0
Exp/Cntr=0.3,0.1

Type RM Length L Ch R = 1 ,19308   ,338.4,342.5,346.9
XS GIS Cut Line= 3
2233916.94756224517179.4134383542234094.49481267517648.249146522
2234161.07503158517714.829365434
#Sta/Elev= 30
       0 2962.31     1.9  2961.1    10.4 2960.17    14.7 2958.89    27.6 2949.29
    70.3 2925.33     100 2904.33   109.4 2900.71   131.1  2885.8     143 2876.33
     159 2865.78   178.5 2848.59   185.8 2846.21   198.6 2845.82   211.7 2842.95
   230.3 2842.43   239.7 2841.61   255.2 2842.41   262.8  2845.2   276.9 2844.84
   288.5 2846.11   345.1 2845.04   365.5 2845.42   410.3 2844.12   442.4 2845.73
   459.6 2849.51   480.9 2857.63   509.4 2863.98   537.6 2872.24   595.5 2874.54
#Mann= 4 ,-1,0
       0      .1       0   230.3    .045       0   255.2      .1       0
     490     .06       0
Bank Sta=230.3,255.2
XS Rating Curve= 0 ,0
Exp/Cntr(USF)=0,0
Exp/Cntr=0.3,0.1

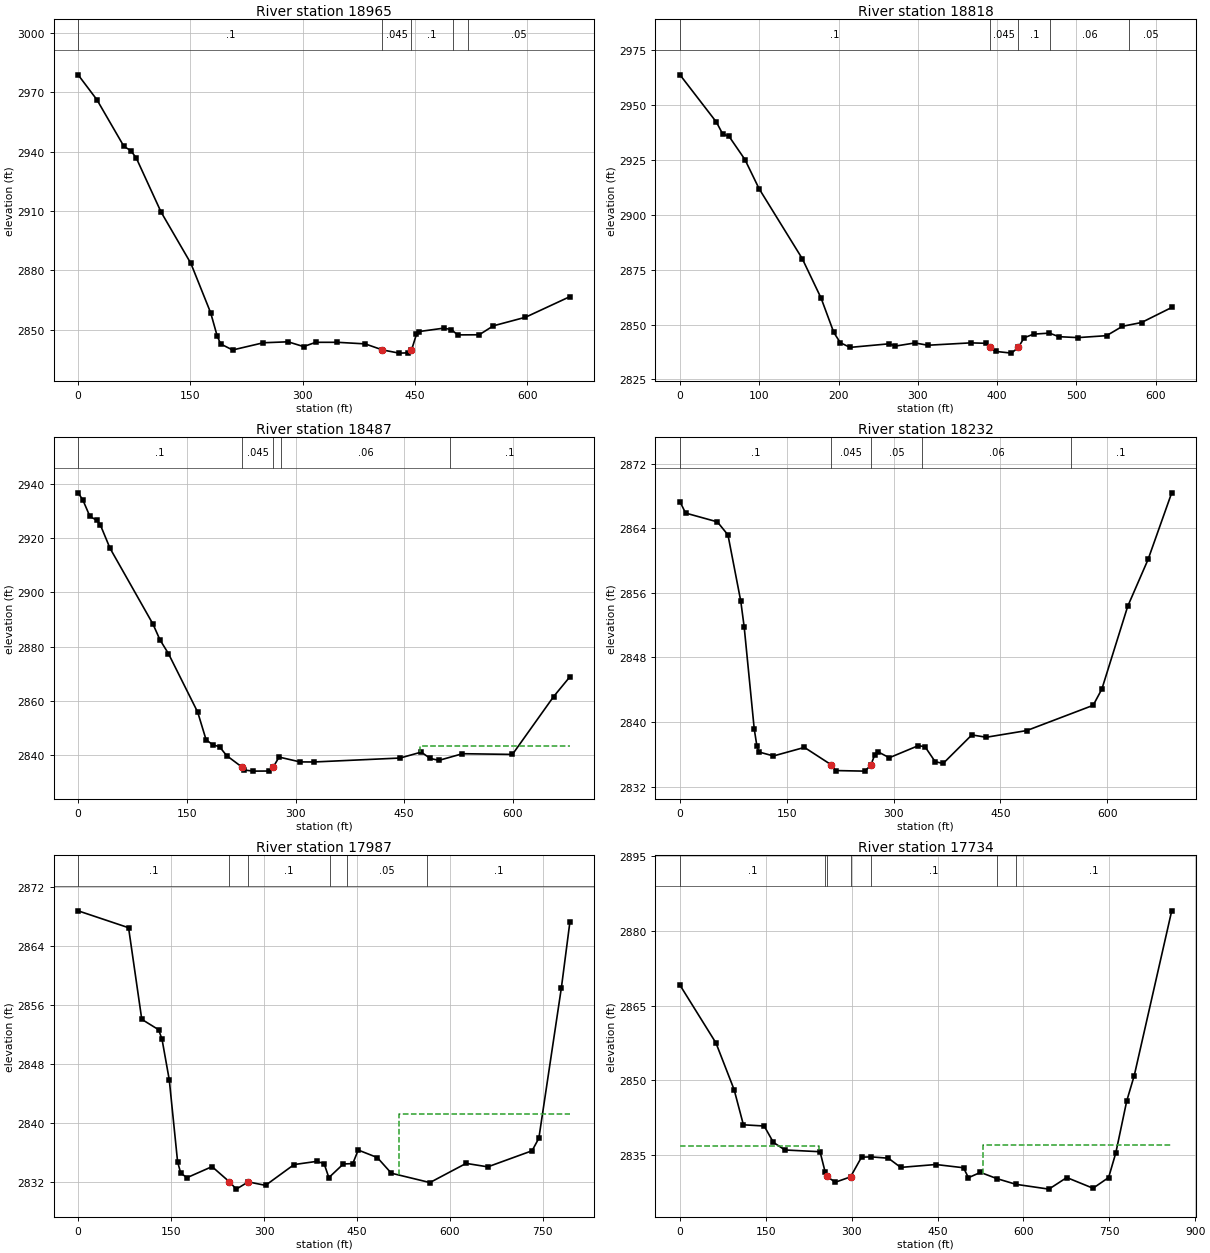
Type RM Length L Ch R = 1 ,18965   ,138.5,147,157.2
XS GIS Cut Line= 2
2233686.69097184517248.7678330542233842.04481596517886.828264288
#Sta/Elev= 30
       0 2978.75    25.1 2966.15    61.2 2942.57    70.4 2940.46    77.7 2936.68
   110.8  2909.4   150.6 2883.46     177 2858.53   185.7 2846.82   190.3 2842.79
   206.3 2839.74   247.4 2843.39   280.4 2843.87     301 2841.46   317.4 2843.61
   346.2 2843.62   383.3 2842.82   406.42839.779   428.6 2838.15   440.9 2838.29
   445.2 2839.65   451.8 2847.63   455.1 2849.04   488.3 2850.77   498.6 2850.01
   506.8 2847.36   535.6 2847.42   554.5 2851.94   597.4 2856.27   656.7 2866.68
#Mann= 5 ,-1,0
       0      .1       0   406.4    .045       0   445.2      .1       0
     500     .08       0     520     .05       0
Bank Sta=406.4,445.2
XS Rating Curve= 0 ,0
Exp/Cntr(USF)=0,0
Exp/Cntr=0.3,0.1

Type RM Length L Ch R = 1 ,18818   ,315.7,331.6,351
XS GIS Cut Line= 4
 2233614.0498096517275.3627623182233606.50887637517465.804296325
2233643.66516217517638.1681776932233632.41795282517891.156309029
#Sta/Elev= 30
       0 2963.71    45.9  2942.2    53.9 2936.77    61.9 2935.68    81.9 2925.15
    99.8 2911.84   154.2 2880.02     178 2862.02     194 2846.39   202.2 2841.73
   214.5 2839.59   263.6 2841.22   271.8  2840.2   296.3 2841.61   312.8 2840.57
   366.5 2841.65   385.9 2841.46   391.6 2839.58     398 2837.78     418 2836.98
   426.8 2839.57     434 2843.97     446 2845.63     466 2846.09     478 2844.46
   502.1 2844.05     538 2844.93   558.1  2849.2   582.1 2850.92   620.2 2857.77
#Mann= 5 ,-1,0
       0      .1       0   391.6    .045       0   426.8      .1       0
  466.91     .06       0  566.91     .05       0
Bank Sta=391.6,426.8
XS Rating Curve= 0 ,0
Exp/Cntr=0.3,0.1

Type RM Length L Ch R = 1 ,18487   ,255.6,254.6,256.9
XS GIS Cut Line= 3
2233523.93935236517303.7616054582233263.84535173517686.677773048
2233227.72118498 517899.29429737
#Sta/Elev= 30
       0 2936.66     6.5 2934.05    16.2 2928.01    25.9 2926.52    30.7 2924.84
      44 2916.26   103.3 2888.34   112.9 2882.58   124.7 2877.45     165 2855.94
   176.5 2845.84   185.5 2843.95   195.1 2843.23   204.8 2839.98   225.5 2835.85
     229 2834.66   241.6 2834.24   262.9 2834.28  269.46 2835.84   277.3 2839.41
   306.3 2837.63   325.7 2837.61   444.3 2839.06   473.5 2841.24   485.7 2838.93
   497.9  2838.2   530.4 2840.65   599.3 2840.39   656.1 2861.66678.5605 2868.94
#Mann= 5 ,-1,0
       0      .1       0   225.5    .045       0  269.46      .1       0
     280     .06       0   512.9      .1       0
#XS Ineff= 2 , 0
                          472.43         2843.67
Permanent Ineff=
       F       F
Bank Sta=225.5,269.46
XS Rating Curve= 0 ,0
Exp/Cntr(USF)=0,0
Exp/Cntr=0.3,0.1

Type RM Length L Ch R = 1 ,18232   ,222.8,244.8,264.8
XS GIS Cut Line= 3
2233264.32157109517248.5407624222233049.16458931517595.851296638
2233001.99047641517873.920404854
#Sta/Elev= 30
       0 2867.31     7.9  2865.9    52.5 2864.81    67.4 2863.19    85.4 2854.97
    90.2 2851.76   104.3 2839.13   108.1 2836.99     111 2836.28   131.3 2835.79
   174.8 2836.85   212.7 2834.68   218.5 2833.98   259.5 2833.91   267.9 2834.62
   273.7 2835.97   278.4 2836.29     294 2835.57   334.8 2837.07   344.2 2836.93
   358.4 2835.08   369.6 2834.86   409.9  2838.4   430.2 2838.11   487.1 2838.94
   580.3 2842.07   592.5 2844.08   628.8 2854.34   657.4 2860.15   690.6 2868.41
#Mann= 5 ,-1,0
       0      .1       0   212.7    .045       0   267.9     .05       0
     340     .06       0  548.55      .1       0
Bank Sta=212.7,267.9
XS Rating Curve= 0 ,0
Exp/Cntr=0.3,0.1

Type RM Length L Ch R = 1 ,17987   ,277.7,253.2,228.7
BEGIN DESCRIPTION:
xs 4
END DESCRIPTION:
XS GIS Cut Line= 4
2233142.05530382517089.0808430352233012.00830351517261.444724403
2232832.41958879517342.9821293622232555.81168336517604.108249039
#Sta/Elev= 30
       0 2868.74    81.4 2866.45   102.7 2854.03   129.9 2852.62   135.4 2851.32
   147.1 2845.82   160.5 2834.73   165.5 2833.19   175.6 2832.56   216.1 2834.06
  243.86 2832.02   255.3 2831.01  274.47 2831.99   302.4 2831.52   348.5 2834.34
   384.8 2834.77   396.9 2834.48   404.6 2832.57     428 2834.42   443.2 2834.47
     452 2836.31   482.8 2835.29   505.4 2833.17   567.7  2831.9   626.1  2834.5
   661.1 2834.03   732.5 2836.21   743.5 2837.91   779.9 2858.34793.5451 2867.19
#Mann= 6 ,-1,0
       0      .1       0  243.86    .045       0  274.47      .1       0
  405.92     .06       0  433.15     .05       0  563.15      .1       0
#XS Ineff= 2 , 0
                          518.27         2841.22
Permanent Ineff=
       F       F
Bank Sta=243.86,274.47
XS Rating Curve= 0 ,0
Exp/Cntr(USF)=0,0
Exp/Cntr=0.5,0.3

Type RM Length L Ch R = 1 ,17734   ,42.9,39.6,40.3
BEGIN DESCRIPTION:
xs 3
END DESCRIPTION:
XS GIS Cut Line= 6
2232881.35168834516801.058464474 2232870.2048026517030.675207452
2232816.56375904517120.8630808412232754.32698032517130.009379264
2232684.42337358517097.3798437592232350.94570849517272.014387038
#Sta/Elev= 30
       0 2869.09    62.9  2857.5    94.6 2848.16   110.8 2841.12   147.1 2840.88
   163.1 2837.61   183.3 2836.08   244.7 2835.73   253.6 2831.67   256.4  2830.8
   271.3 2829.62   297.9 2830.69   317.2 2834.64     334  2834.7   364.1 2834.43
   385.6 2832.59     447 2833.17   495.3 2832.52   503.9 2830.53   524.9 2831.59
   553.8 2830.34     587  2829.2   644.5 2828.24   675.7 2830.56   721.6 2828.42
   748.8 2830.56   761.4 2835.51   780.5 2845.92   793.6 2850.99859.0234 2883.97
#Mann= 7 ,-1,0
       0      .1       0   253.6     .05       0   256.4    .045       0
   297.9     .05       0     334      .1       0   553.8     .06       0
     587      .1       0
#XS Ineff= 3 ,-1
       0   243.1 2836.93   311.3     530 2831.24     530 859.023 2837.06
Permanent Ineff=
       F       F       F
Bank Sta=256.4,297.9
XS Rating Curve= 0 ,0
Exp/Cntr(USF)=0,0
Exp/Cntr=0.5,0.3

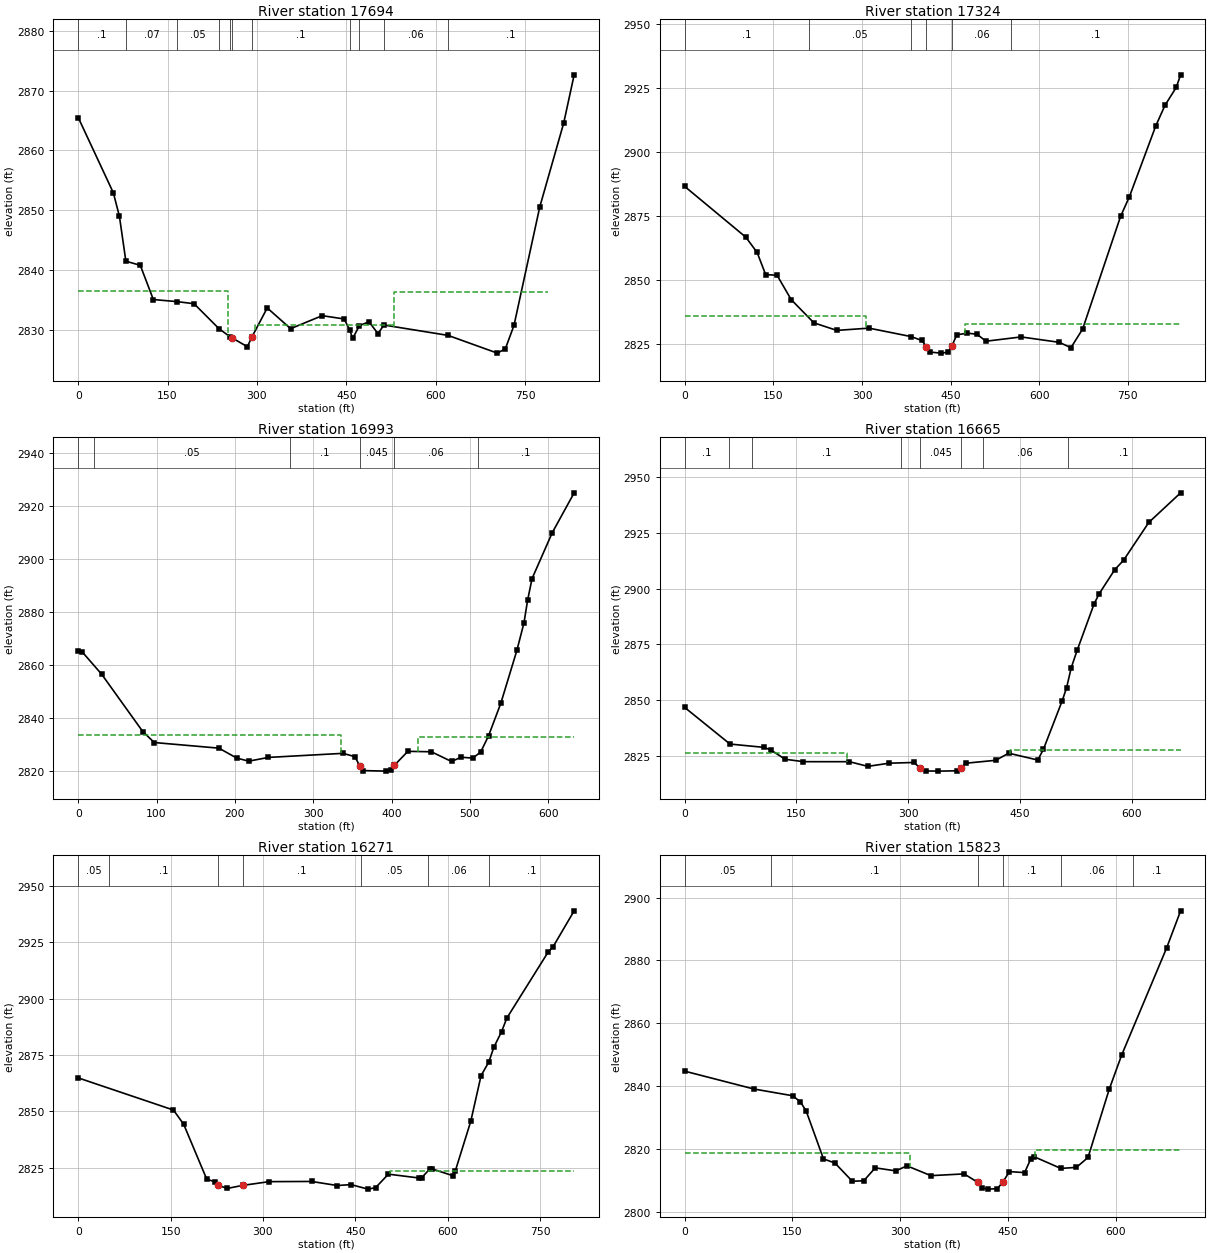
Type RM Length L Ch R = 1 ,17694   ,344.8,370.4,385.5
BEGIN DESCRIPTION:
xs 2
END DESCRIPTION:
XS GIS Cut Line= 6
2232846.98212398516788.9826715872232808.89693103 516907.88278616
2232826.54616678517023.0672721522232793.10550956517089.948586599
2232666.77413783517037.0008793282232332.36756559517200.488536865
#Sta/Elev= 30
       0  2865.5      59 2852.93    69.2    2849      80 2841.53   104.2 2840.84
   126.1 2835.13   166.2 2834.78   194.5 2834.43   236.2 2830.28   255.1  2828.9
   258.2 2828.74   283.9 2827.26   291.4 2828.85   317.3 2833.73   356.6 2830.27
   409.6 2832.44   446.4 2831.89   455.7 2830.08   460.7 2828.65   472.1 2830.78
     488 2831.42   503.2 2829.45   513.2 2830.88   620.8 2829.15   703.6 2826.19
     717 2826.91   731.5 2830.81   774.8 2850.59   814.9 2864.55832.5097 2872.62
#Mann= 11 ,-1,0
       0      .1       0      80     .07       0   166.2     .05       0
   236.2      .1       0   255.1     .05       0   258.2    .045       0
   291.4      .1       0   455.7     .05       0   472.1      .1       0
   513.2     .06       0   620.8      .1       0
#XS Ineff= 3 ,-1
       0     252  2836.5   297.5     5302830.905     530   789.3 2836.43
Permanent Ineff=
       F       F       F
Bank Sta=258.2,291.4
XS Rating Curve= 0 ,0
Exp/Cntr(USF)=0,0
Exp/Cntr=0.5,0.3

Type RM Length L Ch R = 1 ,17324   ,331.6,331,330.3
BEGIN DESCRIPTION:
xs 1
END DESCRIPTION:
XS GIS Cut Line= 3
2232878.42872618516630.8611155062232675.90896482516764.986156561
2232194.17503137517116.259631486
#Sta/Elev= 30
       0 2886.62   103.5  2866.8   122.6 2860.84     137 2852.19   156.3 2851.96
   180.2 2842.44   218.6 2833.38   257.4 2830.43   311.9 2831.31   383.1 2828.02
     401 2826.52  409.08 2824.13   415.8 2821.97   433.3 2821.56   445.5 2821.91
   451.8 2824.23   460.4 2828.71   478.5 2829.35   494.4 2828.94   509.9 2826.21
   569.3 2827.88   633.7 2825.78   653.5 2823.68   673.3 2830.95   737.6 2874.98
   752.4 2882.57     797  2910.2   812.6 2918.25   831.7 2925.27   839.1 2930.17
#Mann= 6 ,-1,0
       0      .1       0     210     .05       0  382.91     .06       0
  409.08    .045       0   451.8     .06       0  552.91      .1       0
#XS Ineff= 2 , 0
          307.04 2836.13  474.36         2832.78
Permanent Ineff=
       F       F
Bank Sta=409.08,451.8
XS Rating Curve= 0 ,0
Exp/Cntr=0.3,0.1

Type RM Length L Ch R = 1 ,16993   ,309.7,328.5,343.4
XS GIS Cut Line= 2
2232637.68233333516375.0745154082232133.09079772516757.340830263
#Sta/Elev= 30
       0 2865.48     5.4 2864.91      30 2856.55    82.5 2834.88    97.2 2830.77
   179.6 2828.65   202.4 2824.89   217.7 2823.74   242.8 2825.15   338.1 2826.69
   353.2 2825.42   359.5 2821.86   363.2 2820.18   393.3 2819.97   399.5 2820.47
   403.4 2822.13   420.8 2827.45   450.8 2827.28   476.5 2823.61   488.7 2825.23
   503.7 2824.89   513.8 2827.22   523.8 2833.34   539.4 2845.58   559.9 2865.55
     569    2876   573.6 2884.51   579.3 2892.71     605 2910.01633.0404 2925.12
#Mann= 6 ,-1,0
       0     .06       0      20     .05       0     270      .1       0
   359.5    .045       0   403.4     .06       0     510      .1       0
#XS Ineff= 2 , 0
          334.88 2833.48  433.97         2832.69
Permanent Ineff=
       F       F
Bank Sta=359.5,403.4
XS Rating Curve= 0 ,0
Exp/Cntr(USF)=0,0
Exp/Cntr=0.3,0.1

Type RM Length L Ch R = 1 ,16665   ,421.3,393.6,348.6
XS GIS Cut Line= 3
2232515.35711258516241.2813052092232083.39617679516343.218989171
 2231931.7638719516505.045062459
#Sta/Elev= 30
       0 2846.69    60.8 2830.26     106 2828.78   115.6 2827.62   134.8 2823.44
   159.4 2822.35   221.1 2822.34   245.8 2820.25   274.5 2821.67   307.4 2821.99
   316.4 2819.47   323.8  2818.2   340.3 2818.11   364.9 2818.25  370.36  2819.5
   377.3 2821.66   417.5 2822.97   434.8 2826.16   473.9 2823.09   481.5 2827.94
   506.8 2849.78   512.6  2855.6   518.7 2864.42   526.7 2872.28   549.4 2893.09
   556.1 2897.59   577.2  2908.5     589 2912.72   622.9  2929.7665.5917 2942.98
#Mann= 8 ,-1,0
       0      .1       0      60     .05       0      90      .1       0
     290     .05       0   316.4    .045       0  370.36     .05       0
     400     .06       0  513.83      .1       0
#XS Ineff= 2 , 0
          217.96 2826.36  437.13         2827.73
Permanent Ineff=
       F       F
Bank Sta=316.4,370.36
XS Rating Curve= 0 ,0
Exp/Cntr(USF)=0,0
Exp/Cntr=0.3,0.1

Type RM Length L Ch R = 1 ,16271   ,461.5,448.4,419.7
XS GIS Cut Line= 3
2232145.83300822515716.3022328082232005.66869277516214.522663169
 2231921.5701035516489.754409865
#Sta/Elev= 30
       0 2864.84   154.7 2850.58   171.3 2844.26   208.7 2819.92   222.6 2818.74
   227.7 2817.24   241.7 2815.82   266.8 2817.16   310.1 2818.84     379 2818.92
   420.6 2817.12   443.1 2817.52   470.5 2815.52   482.9 2816.17   503.7 2822.16
   552.9 2820.48     558 2820.66   570.5 2824.33   574.7 2824.47   608.2  2821.5
   612.4 2823.62   637.5 2845.64   654.2 2865.87   666.7 2871.85   675.1 2878.52
   687.5 2885.33     696 2891.34   762.9 2920.53   771.3 2923.06805.3547 2938.91
#Mann= 7 ,-1,0
       0     .05       0      50      .1       0   227.7    .045       0
   266.8      .1       0     460     .05       0  567.56     .06       0
  667.56      .1       0
#XS Ineff= 2 , 0
                          506.26         2823.64
Permanent Ineff=
       F       F
Bank Sta=227.7,266.8
XS Rating Curve= 0 ,0
Exp/Cntr(USF)=0,0
Exp/Cntr=0.3,0.1

Type RM Length L Ch R = 1 ,15823   ,414.4,427.4,439.1
XS GIS Cut Line= 3
2231657.80634625515744.3350958982231676.91966199516057.793474079
 2231792.8737775516415.849588993
#Sta/Elev= 30
       0 2844.72    96.5 2839.03   150.3 2836.89   161.1 2834.95   169.2 2831.99
   193.2 2816.78   209.2 2815.46   233.4 2809.65   249.3 2809.81   265.3 2813.93
   293.9 2812.96   309.4 2814.57   342.8 2811.44   389.1    2812   408.2 2809.27
   414.3 2807.49   422.7 2807.15   435.3  2807.3   443.2 2809.51   452.1 2812.73
   473.2 2812.41   481.6 2816.67   485.8 2817.54   523.6 2813.75   545.3 2814.07
   561.5 2817.24   590.9 2838.88   608.3 2849.84   670.8 2883.89690.4041 2895.78
#Mann= 6 ,-1,0
       0     .05       0     120      .1       0   408.2    .045       0
   443.2      .1       0  524.04     .06       0  624.04      .1       0
#XS Ineff= 2 , 0
          313.52 2818.72  487.44          2819.6
Permanent Ineff=
       F       F
Bank Sta=408.2,443.2
XS Rating Curve= 0 ,0
Exp/Cntr(USF)=0,0
Exp/Cntr=0.3,0.1

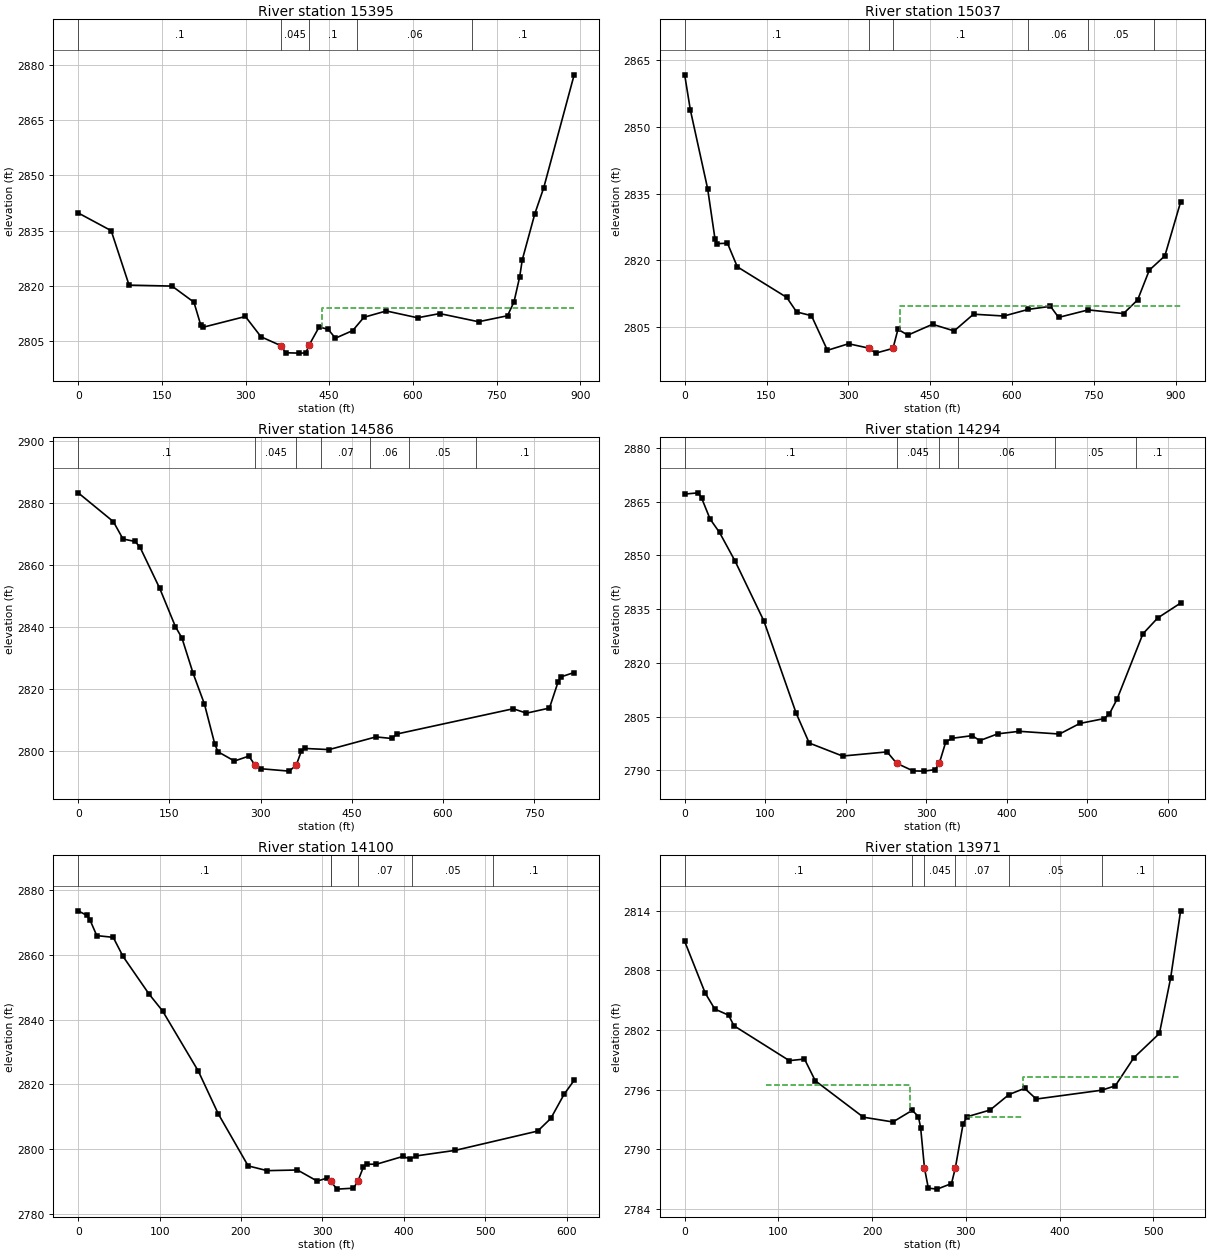
Type RM Length L Ch R = 1 ,15395   ,377,358.6,333.9
XS GIS Cut Line= 3
2231315.04088393515762.1741905912231271.71736825516386.542504854
2231415.70434684 516606.98274642
#Sta/Elev= 30
       0  2839.8    59.1    2835    91.2 2820.24   168.2 2819.98   207.5 2815.61
   219.5 2809.52   223.5 2808.81   299.7 2811.74   327.8 2806.23   363.9  2803.8
   371.9 2801.91     396 2801.81     408 2801.85   413.8 2803.94     432 2808.91
   448.1 2808.25   461.2 2805.86   492.2 2807.93   512.2 2811.52   552.3 2813.24
   608.5 2811.39   648.1 2812.53   717.7 2810.32   769.7 2811.94   781.3  2815.7
   791.5 2822.48   796.2 2827.13   818.8 2839.65   834.5 2846.58889.1682 2877.24
#Mann= 5 ,-1,0
       0      .1       0   363.9    .045       0   413.8      .1       0
     500     .06       0  705.87      .1       0
#XS Ineff= 2 , 0
                          437.75         2813.97
Permanent Ineff=
       F       F
Bank Sta=363.9,413.8
XS Rating Curve= 0 ,0
Exp/Cntr(USF)=0,0
Exp/Cntr=0.3,0.1

Type RM Length L Ch R = 1 ,15037   ,466,450.8,432.8
XS GIS Cut Line= 2
2230777.31960104 515895.967400792231204.18365262516698.726661986
#Sta/Elev= 30
       0 2861.58    10.4 2853.71    42.1 2836.07    55.7 2824.72    59.2 2823.76
    78.4 2823.88    96.5 2818.58   187.1 2811.73   205.2 2808.47   232.4 2807.64
   261.7 2799.88   300.4 2801.35   337.2 2800.38   350.2 2799.25   381.9 2800.31
     391 2804.59   409.1 2803.28   454.4 2805.71     494 2804.22   529.5 2807.97
   585.4 2807.56     630 2809.05   670.6 2809.73   685.5 2807.25   739.8 2808.93
   804.5 2808.11   830.4 2811.17   851.8 2817.83   880.3 2821.03   909.2  2833.1
#Mann= 6 ,-1,0
       0      .1       0   337.2    .045       0   381.9      .1       0
     630     .06       0     740     .05       0     860      .1       0
#XS Ineff= 2 , 0
                          395.49          2809.9
Permanent Ineff=
       F       F
Bank Sta=337.2,381.9
XS Rating Curve= 0 ,0
Exp/Cntr(USF)=0,0
Exp/Cntr=0.3,0.1

Type RM Length L Ch R = 1 ,14586   ,270.1,291.5,304.6
XS GIS Cut Line= 3
2230383.58529673516306.2665787352230772.22271684516612.079630619
2230944.24255852516883.488714166
#Sta/Elev= 30
       0 2883.25    57.8 2873.97    73.7 2868.37    93.6 2867.58   101.7 2865.71
   134.1 2852.46     160 2840.09   170.6 2836.49   189.1 2825.04   207.6 2815.21
   224.6 2802.34   229.8 2799.83     257 2796.82   280.7 2798.41   290.9 2795.49
   301.1 2794.33   346.9 2793.57   358.6 2795.45   366.9 2799.91   372.8 2800.88
   412.7 2800.51   489.8  2804.6   515.6 2804.09   524.2 2805.53   715.6 2813.67
   737.4 2812.25   775.2 2813.89   789.4  2822.3   794.2 2823.94815.8619 2825.35
#Mann= 7 ,-1,0
       0      .1       0   290.9    .045       0   358.6      .1       0
     400     .07       0     480     .06       0  544.53     .05       0
  654.53      .1       0
Bank Sta=290.9,358.6
XS Rating Curve= 0 ,0
Exp/Cntr(USF)=0,0
Exp/Cntr=0.3,0.1

Type RM Length L Ch R = 1 ,14294   ,180.2,194.5,206.8
XS GIS Cut Line= 2
2230287.49730677516450.8337101742230592.64330393 516985.88422575
#Sta/Elev= 30
       0  2867.1    16.9 2867.45    21.1 2865.96    31.5 2860.16    43.3 2856.38
    62.6  2848.4    98.3 2831.73   138.6 2805.88   154.7 2797.63   196.1    2794
   251.4 2795.16   263.2 2791.99   283.7 2789.85   297.4 2789.79   311.2 2790.21
   316.3 2792.03   324.3 2797.96   332.4 2798.96     357 2799.69   366.5 2798.31
   388.9  2800.2   415.7  2800.9   465.5 2800.14   490.8  2803.1   521.3 2804.46
   527.6 2805.82   536.9 2809.82   569.1  2828.1   587.5 2832.53 615.949 2836.69
#Mann= 6 ,-1,0
       0      .1       0   263.2    .045       0   316.3      .1       0
     340     .06       0     460     .05       0     560      .1       0
Bank Sta=263.2,316.3
XS Rating Curve= 0 ,0
Exp/Cntr(USF)=0,0
Exp/Cntr=0.3,0.1

Type RM Length L Ch R = 1 ,14100   ,130.9,128.3,125.7
BEGIN DESCRIPTION:
xs 4
END DESCRIPTION:
XS GIS Cut Line= 2
2230203.05964728516446.6536280212230292.51340535517049.421474475
#Sta/Elev= 30
       0 2873.59    10.6 2872.18    14.7 2870.63    22.8 2865.93      43  2865.4
    55.1 2859.49    87.1 2847.85   103.6 2842.68   147.6 2824.06   172.2 2810.81
   208.8 2794.79   232.1 2793.32   269.4 2793.52   293.7 2790.08   305.8 2791.05
   310.3 2789.99     318 2787.61   338.2  2787.9   343.6 2790.05   350.3 2794.38
   354.4  2795.3   366.5 2795.31   398.8  2797.7   408.1 2796.94   415.2 2797.87
   463.5  2799.6   564.6 2805.55   580.7 2809.46     597 2816.91609.3694 2821.23
#Mann= 6 ,-1,0
       0      .1       0     310     .07       0   310.3    .045       0
   343.6     .07       0     410     .05       0     510      .1       0
Bank Sta=310.3,343.6
XS Rating Curve= 0 ,0
Exp/Cntr(USF)=0,0
Exp/Cntr=0.5,0.3

Type RM Length L Ch R = 1 ,13971   ,47.2,47.5,48.4
BEGIN DESCRIPTION:
xs 3
END DESCRIPTION:
XS GIS Cut Line= 6
2229935.18827869516620.6244671442230050.06864048516664.853916404
2230078.79427798516680.8763972582230101.56510606516706.353659068
2230112.28441825516736.3083535552230182.15923651517035.209195155
#Sta/Elev= 30
       0 2810.93    21.9 2805.72    32.1 2804.11    46.9 2803.49    52.5 2802.43
   111.6 2798.91   127.8 2799.07   139.3 2796.88   190.6 2793.21   222.1 2792.73
   242.7  2793.9   249.3 2793.28   251.7 2792.14   255.8 2788.07   259.9 2786.06
   269.3 2785.96   284.6 2786.52   288.7 2788.09   296.9  2792.5     301 2793.25
   325.7 2793.93   345.9 2795.49   362.6 2796.12     375 2795.04   444.8 2795.93
   459.3 2796.37   479.1  2799.2   506.4 2801.65   518.3 2807.21     529 2814.01
#Mann= 6 ,-1,0
       0      .1       0   242.7     .07       0   255.8    .045       0
   288.7     .07       0   345.9     .05       0   444.8      .1       0
#XS Ineff= 4 ,-1
   86.54     240 2796.46     240   243.8  2793.1   300.7  361.01 2793.26
  361.01     529 2797.25
Permanent Ineff=
       F       F       F       F
Bank Sta=255.8,288.7
XS Rating Curve= 0 ,0
Exp/Cntr(USF)=0,0
Exp/Cntr=0.5,0.3