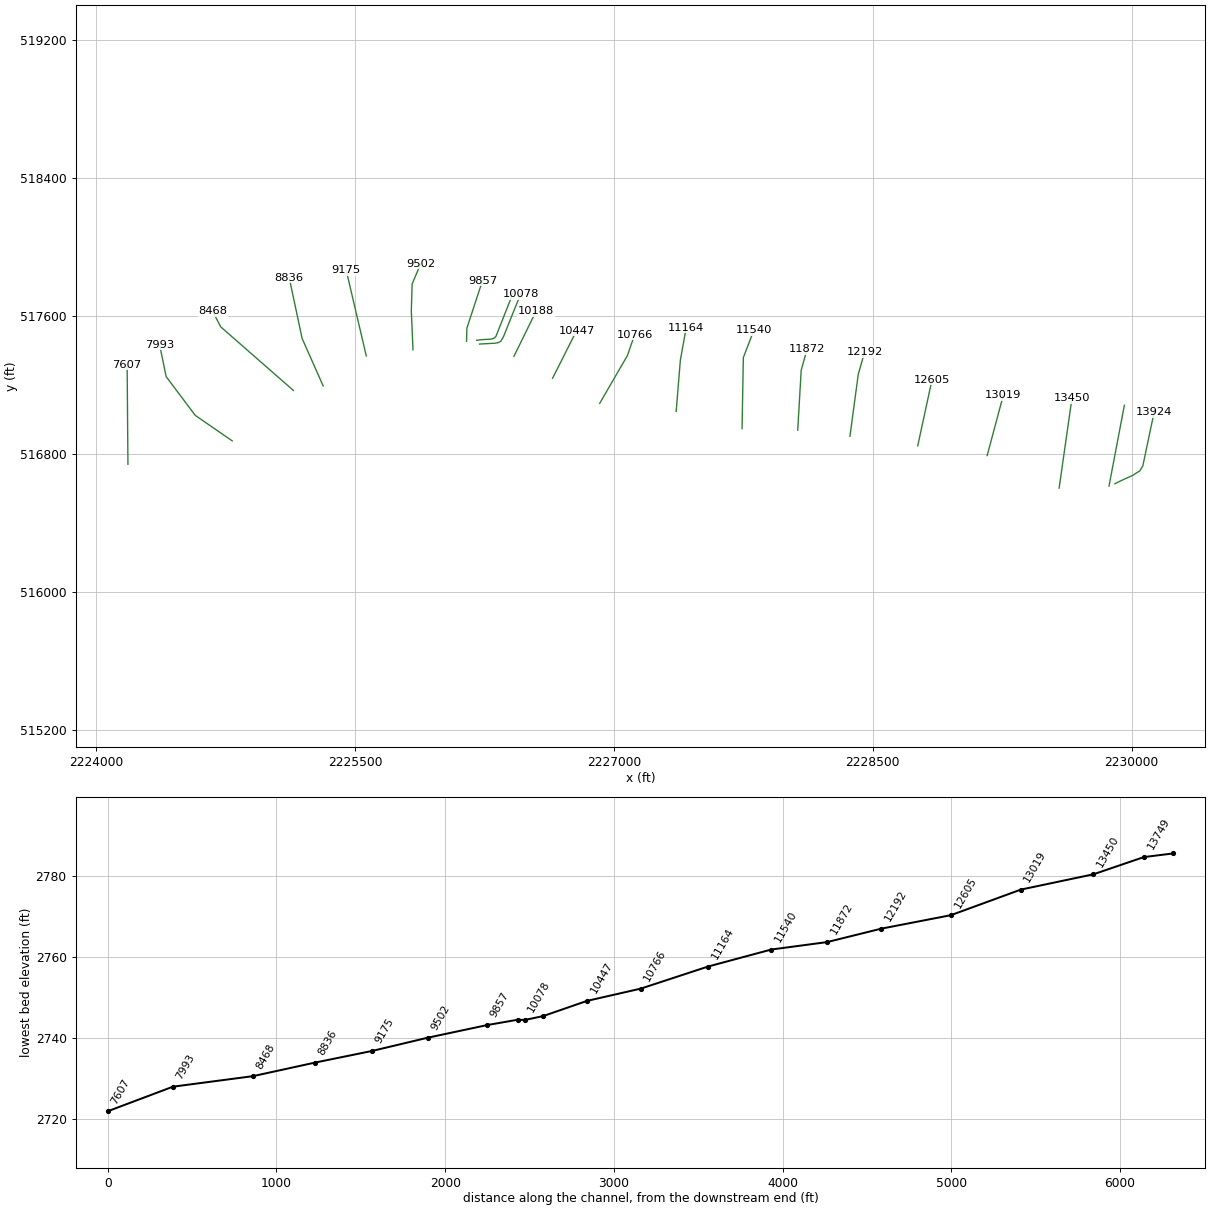
HEC-RAS study BIGSPRFK.prj: BIGSPRFK

--- BIGSPRFK.g01 (geometry) --- (continued)

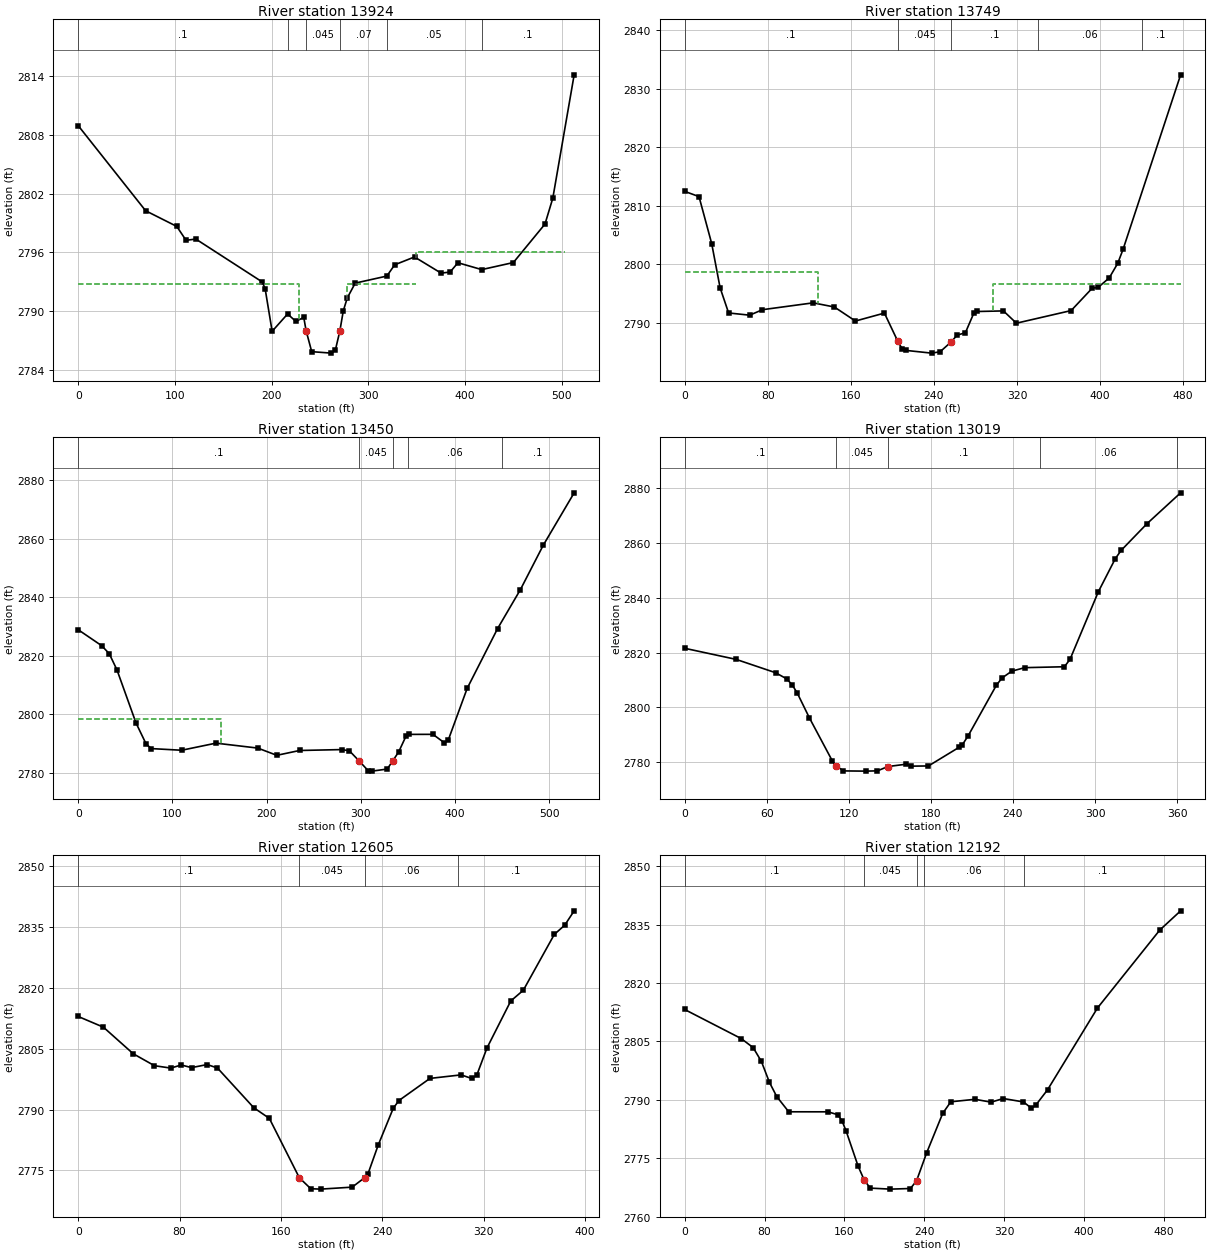
Type RM Length L Ch R = 1 ,13924   ,173.5,175.4,177.2
BEGIN DESCRIPTION:
xs 2
END DESCRIPTION:
XS GIS Cut Line= 6
2229902.67392767 516629.741226322229939.71447164516648.133587792
 2230004.0877368516677.3941628632230046.72457476516704.146688642
 2230064.2809198516732.5712472822230129.49020139 517042.73334303
#Sta/Elev= 30
       0 2808.93    69.7 2800.24   101.9 2798.64   111.5 2797.22   121.6 2797.35
   190.4 2792.96   193.3 2792.25   200.5 2787.93   216.5  2789.7     225 2788.94
   233.2 2789.35  235.58 2788.01   241.4 2785.85   261.8  2785.7   265.9 2786.02
   270.5 2787.96   274.1 2790.03   278.2 2791.34   286.4 2792.85   319.1 2793.57
   327.2 2794.72   347.7 2795.52   375.2 2793.87   384.5 2793.98   392.6 2794.93
   417.2 2794.23   449.9 2794.95   482.6 2798.88   490.7 2801.53512.7539 2814.12
#Mann= 6 ,-1,0
       0      .1       0   216.5     .07       0  235.58    .045       0
   270.5     .07       0   319.1     .05       0   417.2      .1       0
#XS Ineff= 3 ,-1
       0   228.5 2792.75   277.5  349.52 2792.75  349.52  502.99 2796.04
Permanent Ineff=
       F       F       F
Bank Sta=235.58,270.5
XS Rating Curve= 0 ,0
Exp/Cntr(USF)=0,0
Exp/Cntr=0.5,0.3

Type RM Length L Ch R = 1 ,13749   ,297.9,298.6,299.6
BEGIN DESCRIPTION:
xs 1
END DESCRIPTION:
XS GIS Cut Line= 2
2229868.26311982516615.6353068682229957.43820575517084.733415142
#Sta/Elev= 30
       0 2812.46    13.8 2811.56      26 2803.53    34.1 2795.97    42.3 2791.66
    62.6 2791.28    74.9 2792.22   123.7 2793.39   144.1 2792.68   164.4 2790.28
   192.3 2791.64   205.2 2786.81   209.2 2785.58   213.4 2785.25   237.7 2784.79
   245.9 2785.02   256.5 2786.69   262.2 2787.85   270.3 2788.29   278.4 2791.63
   281.8 2791.91   306.9 2792.01   319.4 2789.91   372.1 2792.07   392.4  2795.9
   398.1 2796.04   408.7 2797.64   416.9 2800.13   422.1 2802.55477.4989 2832.39
#Mann= 5 ,-1,0
       0      .1       0   205.2    .045       0   256.5      .1       0
     340     .06       0     440      .1       0
#XS Ineff= 2 , 0
          127.89 2798.69  296.62         2796.58
Permanent Ineff=
       F       F
Bank Sta=205.2,256.5
XS Rating Curve= 0 ,0
Exp/Cntr(USF)=0,0
Exp/Cntr=0.3,0.1

Type RM Length L Ch R = 1 ,13450   ,435.2,430.9,426.6
XS GIS Cut Line= 2
 2229579.3729977516604.4884211262229653.68556931517125.605329526
#Sta/Elev= 30
       0 2828.89    24.9 2823.44    32.9 2820.72    41.1 2815.19    61.4 2796.96
      72 2789.87    77.5 2788.24   109.8 2787.67   146.2  2790.1   190.6 2788.41
   210.8 2785.94     235 2787.59   279.5  2787.9   287.8 2787.49   298.4 2783.93
   307.8 2780.67   311.8 2780.53     328 2781.24   333.7 2783.98   340.1 2787.08
   348.2  2792.7   351.4  2793.1   376.5 2793.11   388.6 2790.23   392.6 2791.01
   412.8 2808.81   445.1 2829.27   469.4 2842.65   493.6  2857.8526.3888 2875.72
#Mann= 5 ,-1,0
       0      .1       0   298.4    .045       0   333.7      .1       0
     350     .06       0     450      .1       0
#XS Ineff= 2 , 0
          151.77 2798.22
Permanent Ineff=
       F       F
Bank Sta=298.4,333.7
XS Rating Curve= 0 ,0
Exp/Cntr(USF)=0,0
Exp/Cntr=0.3,0.1

Type RM Length L Ch R = 1 ,13019   ,412.1,414.3,416.9
XS GIS Cut Line= 2
2229162.29368955516793.056571581 2229256.1133112517143.254565283
#Sta/Elev= 30
       0 2821.58    37.6 2817.53    66.4 2812.67    74.7 2810.39    78.8 2808.08
    82.4 2805.14    91.2 2796.15   107.8 2780.59   110.6 2778.71   116.1 2776.81
   132.3 2776.73   140.9 2776.83   148.6 2778.41   161.7 2779.24   165.8 2778.55
   178.2 2778.62   200.9 2785.52     203 2786.36   207.2  2789.6   227.9 2808.12
     232 2810.74   239.1 2813.23   248.6 2814.51   277.6 2814.84   281.7 2817.55
   302.4 2842.22   314.8  2854.3     319 2857.29     338 2867.09362.5476 2878.34
#Mann= 5 ,-1,0
       0      .1       0   110.6    .045       0   148.6      .1       0
     260     .06       0     360      .1       0
Bank Sta=110.6,148.6
XS Rating Curve= 0 ,0
Exp/Cntr(USF)=0,0
Exp/Cntr=0.3,0.1

Type RM Length L Ch R = 1 ,12605   ,409.6,412.8,416
XS GIS Cut Line= 2
2228760.07689572516849.7199074322228842.74963164517232.429651213
#Sta/Elev= 30
       0 2812.94    19.9  2810.3    43.4 2803.76    60.2 2800.81    73.1 2800.22
    81.3 2800.99    89.5 2800.34   101.8 2801.09   109.9 2800.25   138.6 2790.46
   150.9 2787.83   174.6 2773.19   183.6  2770.5   191.4  2770.4   216.3 2770.89
  226.03  2773.2   228.6 2774.02   236.8 2781.22   248.7 2790.31   253.2 2792.23
   277.7 2797.68   302.3 2798.55   310.5 2797.68   314.6 2798.43   322.7 2805.17
   341.5 2816.76   351.4  2819.4   375.9 2833.17   384.1 2835.43391.5374 2838.97
#Mann= 4 ,-1,0
       0      .1       0   174.6    .045       0  226.03     .06       0
     300      .1       0
Bank Sta=174.6,226.03
XS Rating Curve= 0 ,0
Exp/Cntr(USF)=0,0
Exp/Cntr=0.3,0.1

Type RM Length L Ch R = 1 ,12192   ,317.4,320.4,323.3
XS GIS Cut Line= 3
2228367.16151432516905.0515791612228415.45234489517264.012494146
2228452.31292855517393.241085302
#Sta/Elev= 30
       0 2813.21    56.6 2805.74    68.6 2803.41    76.8 2799.87    84.9 2794.48
    92.2 2790.83   104.2 2786.93   143.5 2786.92   153.5 2786.17   157.6 2784.55
   161.6 2782.03   173.7 2772.94  179.74 2769.41   185.8 2767.32     206 2767.06
   226.1 2767.22   232.2 2769.22   242.3 2776.39   258.4 2786.54   266.5  2789.5
   290.7 2790.14   306.9  2789.4     319 2790.34   339.2 2789.46   347.2 2787.86
   351.3 2788.55   363.4  2792.6   413.3 2813.58   475.7 2833.61   496.6 2838.56
#Mann= 5 ,-1,0
       0      .1       0  179.74    .045       0   232.2      .1       0
     240     .06       0     340      .1       0
Bank Sta=179.74,232.2
XS Rating Curve= 0 ,0
Exp/Cntr=0.3,0.1

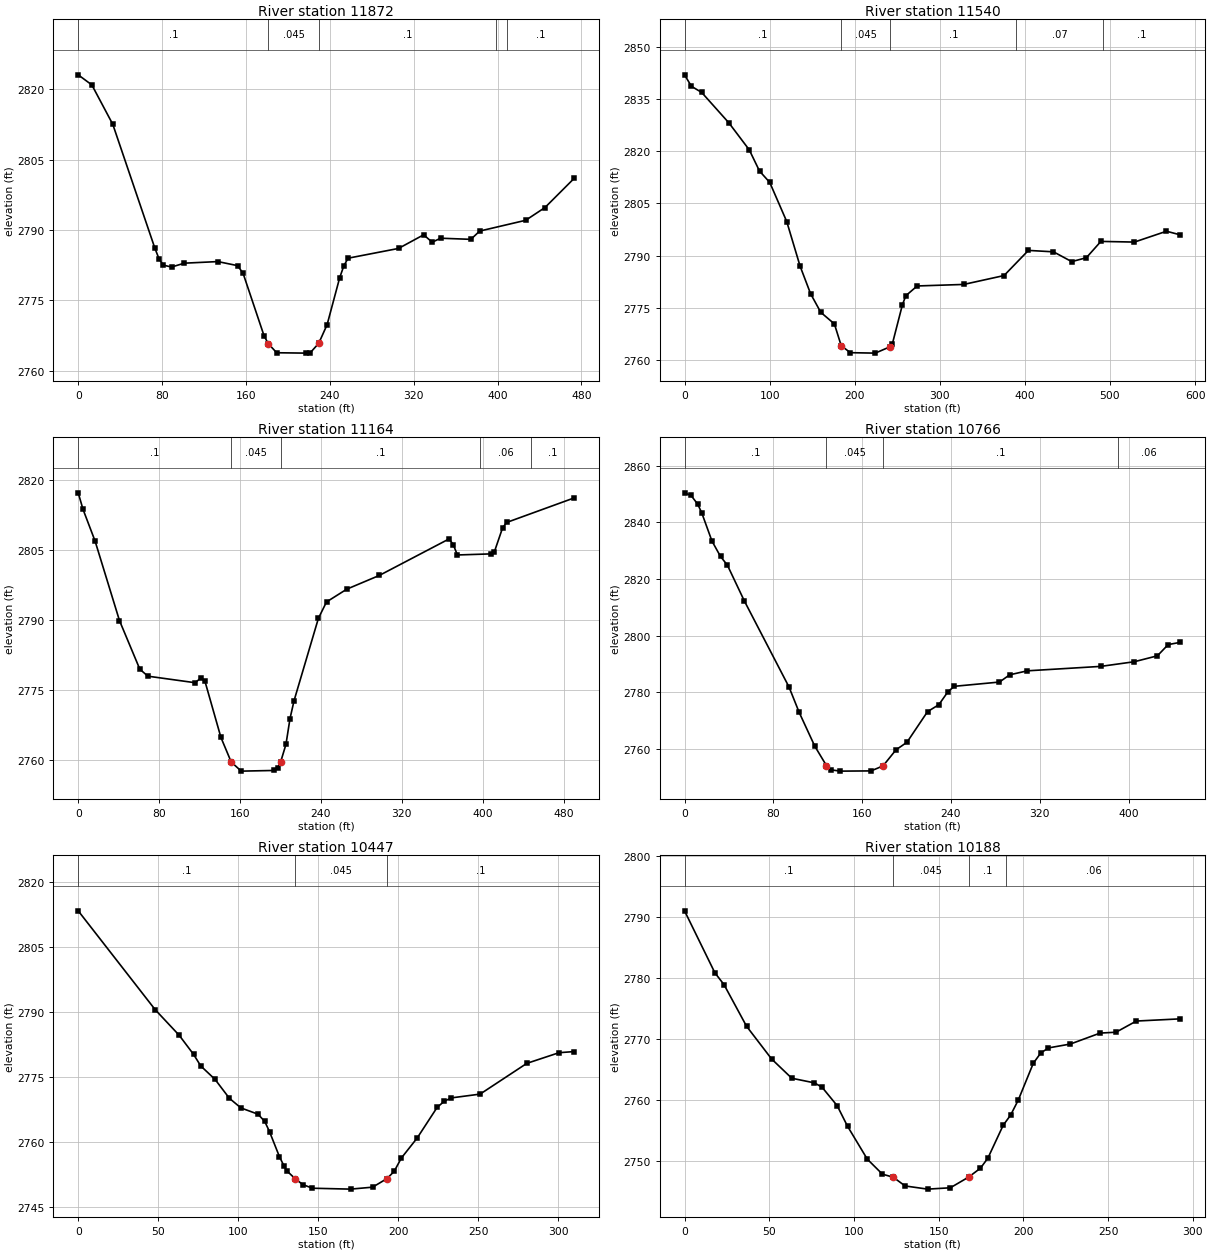
Type RM Length L Ch R = 1 ,11872   ,329.4,331.5,332.9
XS GIS Cut Line= 3
2228064.54475763 516940.190136292228084.76140123517288.164079919
2228118.37375039517407.830870949
#Sta/Elev= 30
       0 2823.05      13  2820.9      33 2812.49    73.1 2786.11    77.1 2783.83
    81.1 2782.49    89.1 2782.09   101.2 2782.91   133.2 2783.25   152.1 2782.38
   157.3 2780.72   177.3 2767.41   181.3 2765.75   189.3 2763.82   217.4 2763.74
   221.4 2763.84   229.4 2765.83   237.4 2769.81   249.4 2779.82   253.4 2782.37
   257.4 2783.97   305.5 2786.05   329.5 2788.96   337.6 2787.37   345.6 2788.23
   374.5 2787.99   382.9 2789.75   426.8 2792.05   445.2 2794.77   472.9 2800.96
#Mann= 5 ,-1,0
       0      .1       0   181.3    .045       0   229.4      .1       0
  398.56     .06       0  408.56      .1       0
Bank Sta=181.3,229.4
XS Rating Curve= 0 ,0
Exp/Cntr=0.3,0.1

Type RM Length L Ch R = 1 ,11540   ,380.3,375.6,373.8
XS GIS Cut Line= 3
2227741.99466469516949.1129719572227749.42592185517360.618837237
2227810.73379343517520.390866194
#Sta/Elev= 30
       0 2842.03     8.1 2838.72    20.1 2836.97    52.1  2828.2    76.1 2820.41
    88.1 2814.32   100.1 2811.06   120.1 2799.78   135.8 2786.93   148.1 2779.01
   160.1 2773.64   176.1  2770.3   184.1 2764.05   194.8 2762.02   224.1 2761.89
   241.9 2763.76   244.1 2764.43   256.1 2775.87   260.1 2778.43   273.4 2781.23
   328.1 2781.67   375.5 2784.23   404.1 2791.47   433.6 2791.06     455 2788.24
   472.2 2789.36   489.3 2794.06   528.7 2793.87   566.4 2796.99582.7038 2795.94
#Mann= 5 ,-1,0
       0      .1       0   184.1    .045       0   241.9      .1       0
     390     .07       0  491.57      .1       0
Bank Sta=184.1,241.9
XS Rating Curve= 0 ,0
Exp/Cntr(USF)=0,0
Exp/Cntr=0.3,0.1

Type RM Length L Ch R = 1 ,11164   ,414.5,397.9,377.9
XS GIS Cut Line= 3
2227360.21382806517048.5060364832227384.36541383 517344.82741577
2227418.42645704517534.678371105
#Sta/Elev= 30
       0 2817.23     4.7 2813.73    16.7 2806.89    40.8 2789.89    60.9 2779.49
    68.9 2777.99   115.6 2776.59   121.1 2777.58   125.1 2777.06   141.1 2764.88
  151.26 2759.62   161.2 2757.67   193.3 2757.81   197.3  2758.4  200.11 2759.62
   205.4  2763.4   209.4 2768.92   213.4 2772.75   237.5 2790.39   245.5 2793.88
   265.6 2796.62   297.7 2799.55   366.7 2807.37   370.8 2806.14   374.9 2803.93
   407.7 2804.16   411.4 2804.57   419.6 2809.76   423.6 2810.89   490.2 2816.13
#Mann= 5 ,-1,0
       0      .1       0  151.26    .045       0  200.11      .1       0
   397.3     .06       0   447.3      .1       0
Bank Sta=151.26,200.11
XS Rating Curve= 0 ,0
Exp/Cntr=0.3,0.1

Type RM Length L Ch R = 1 ,10766   ,316.7,319.6,321.9
XS GIS Cut Line= 3
2226917.22908624517095.8133862122227077.82605595517372.694630123
2227118.88548568517492.472685239
#Sta/Elev= 30
       0 2850.41     5.9 2849.47    11.9 2846.38    15.5 2843.34    24.7 2833.39
    32.4 2827.95    38.6 2824.89    53.7  2812.4    94.1 2781.91   103.3 2772.91
   117.3 2761.04   127.8 2754.19   131.9 2752.66   140.3 2752.21     168 2752.29
   178.8 2754.04   190.5 2759.72   200.4  2762.4   218.9 2773.19   229.1 2775.65
   237.4 2780.28   243.1 2782.14   283.7 2783.64   292.9 2786.19   308.8  2787.6
     375 2789.17   405.2 2790.81     426  2792.9   435.7 2796.85   446.7 2797.67
#Mann= 4 ,-1,0
       0      .1       0   127.8    .045       0   178.8      .1       0
  390.09     .06       0
Bank Sta=127.8,178.8
XS Rating Curve= 0 ,0
Exp/Cntr=0.3,0.1

Type RM Length L Ch R = 1 ,10447   ,258.4,258.9,259.5
XS GIS Cut Line= 2
2226644.02641918517240.7898155192226783.36249095517517.604144759
#Sta/Elev= 30
       0 2813.42    48.1  2790.6    63.1 2784.69    72.1 2780.28    76.6  2777.6
    85.5 2774.51    94.5 2770.13   101.7 2767.91   112.4 2766.46   116.6 2764.78
   119.6 2762.41   125.8 2756.63   128.5 2754.61   130.3 2753.41   135.8  2751.5
   140.4 2750.21   146.4 2749.37   170.2 2749.16     184 2749.61     193 2751.59
   197.5 2753.27     202 2756.35   211.9 2760.98   224.3 2768.01   228.8 2769.46
   233.3 2770.23   251.2  2771.1   280.4  2778.2   300.5 2780.66309.9044 2780.92
#Mann= 3 ,-1,0
       0      .1       0   135.8    .045       0     193      .1       0
Bank Sta=135.8,193
XS Rating Curve= 0 ,0
Exp/Cntr(USF)=0,0
Exp/Cntr=0.3,0.1

Type RM Length L Ch R = 1 ,10188   ,106.7,109.5,112.2
BEGIN DESCRIPTION:
xs 4
END DESCRIPTION:
XS GIS Cut Line= 2
2226420.28370035 517368.298143532226549.04574253517631.146113631
#Sta/Elev= 30
       0 2790.96    17.9 2780.82    23.3 2778.88    36.6 2772.07    51.4 2766.71
    63.3 2763.56    76.7  2762.8    81.2 2762.08    90.1 2759.07    96.2 2755.71
   107.9 2750.31   116.8 2747.86   123.2 2747.36   130.2 2745.93   143.5 2745.41
   156.9 2745.63  167.76 2747.39   174.7 2748.84   179.1  2750.5   188.1 2755.86
   192.5 2757.53     197 2759.98   205.9 2766.02   210.3 2767.69   214.8 2768.52
   227.8 2769.16   245.3 2770.95   254.7 2771.09   266.7 2772.92   292.7 2773.28
#Mann= 4 ,-1,0
       0      .1       0   123.2    .045       0  167.76      .1       0
     190     .06       0
Bank Sta=123.2,167.76
XS Rating Curve= 0 ,0
Exp/Cntr=0.5,0.3

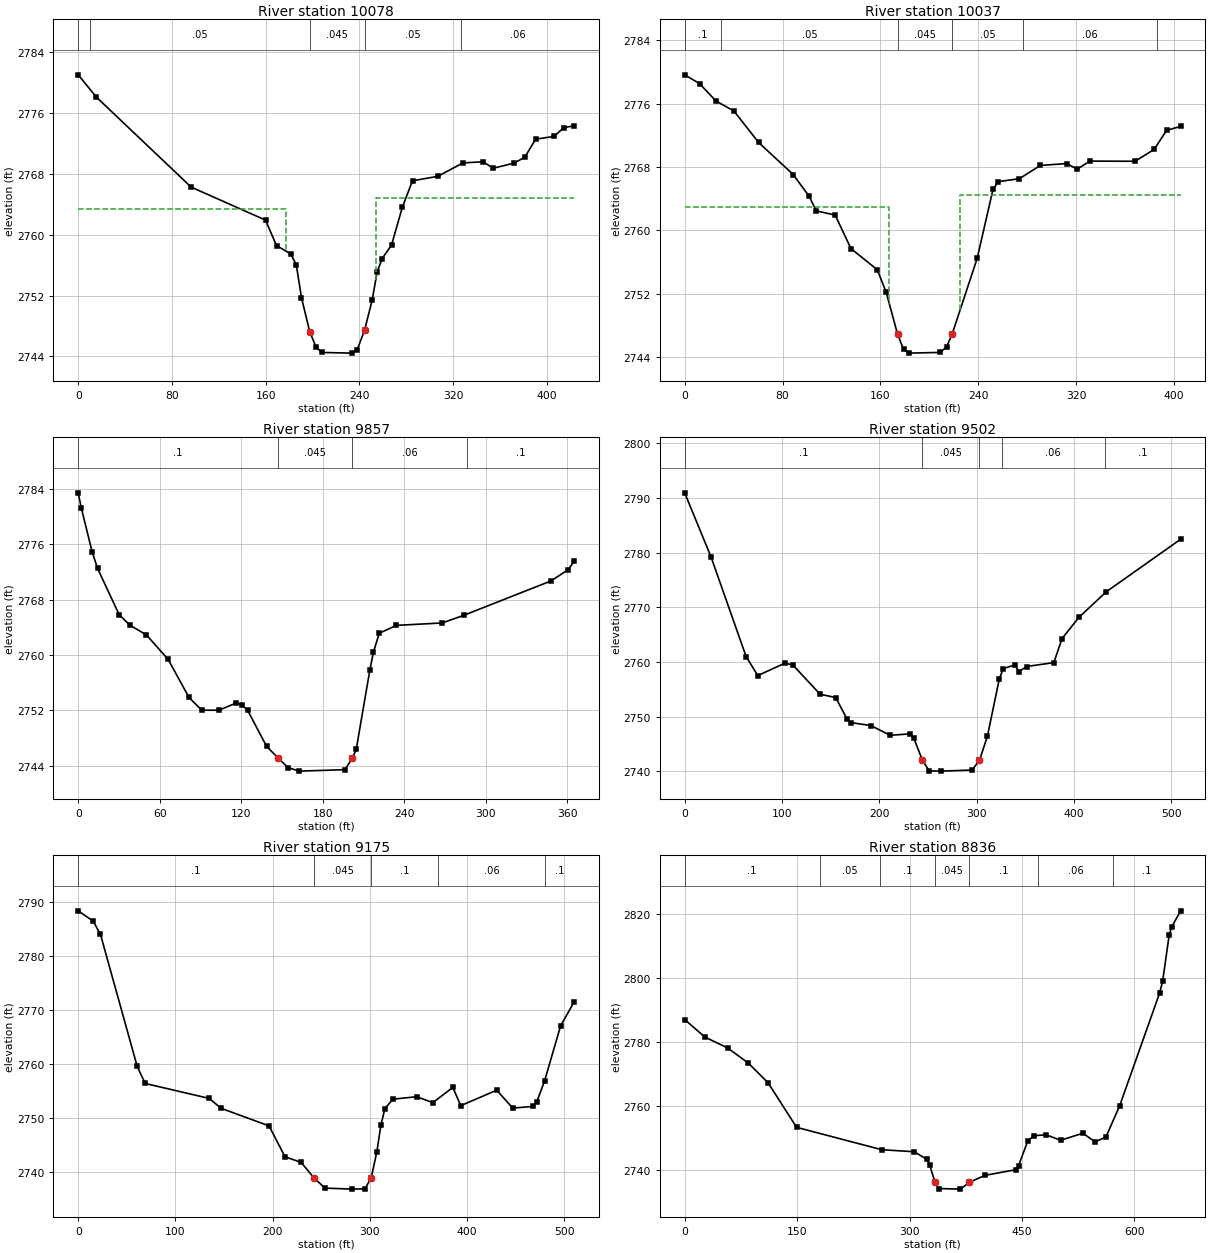
Type RM Length L Ch R = 1 ,10078   ,41.5,41.8,41.9
BEGIN DESCRIPTION:
xs 3
END DESCRIPTION:
XS GIS Cut Line= 6
 2226220.5509351517439.1726130882226309.53150788517444.048260911
2226328.42464319517447.0955408012226344.27049862517455.627924492
2226359.50689807517481.8345315412226458.84822246517729.273658569
#Sta/Elev= 30
       0 2781.03    15.5  2778.1    96.4 2766.27   159.9 2761.93   169.3 2758.58
   181.4 2757.49   186.2 2756.05   190.6 2751.75   197.6 2747.28   202.9 2745.29
   207.8 2744.53   233.6 2744.44     238 2744.79   244.5 2747.48   250.9 2751.36
   255.2  2755.1   259.5 2756.88   267.5 2758.64   276.8 2763.66   285.4  2767.1
   306.9 2767.68   328.5 2769.45   345.7  2769.6   354.3 2768.75   372.1 2769.42
   381.3  2770.2   390.5 2772.57   406.1 2772.93   414.7 2774.09423.4095 2774.33
#Mann= 5 ,-1,0
       0      .1       0      10     .05       0   197.6    .045       0
   244.5     .05       0  326.77     .06       0
#XS Ineff= 2 , 0
             177 2763.34     254         2764.84
Permanent Ineff=
       F       F
Bank Sta=197.6,244.5
XS Rating Curve= 0 ,0
Exp/Cntr(USF)=0,0
Exp/Cntr=0.5,0.3

Type RM Length L Ch R = 1 ,10037   ,177.4,179.8,182.5
BEGIN DESCRIPTION:
xs 2
END DESCRIPTION:
XS GIS Cut Line= 6
 2226204.0956237517461.1130282932226243.10080629517465.379220138
2226284.54381278517467.2075880722226304.65586006517473.302147851
2226315.62606766517483.0534434972226421.67140781517751.823529751
#Sta/Elev= 30
       0 2779.66    12.2 2778.55    25.5 2776.36    40.3 2775.08    60.4 2771.12
    88.7 2767.06   101.7 2764.32   107.6 2762.47     123 2761.94   135.9 2757.71
   157.4 2755.04   164.7 2752.19     174 2746.89   178.9 2744.96   183.2  2744.5
     209 2744.59   214.1 2745.32  218.52 2746.86   239.1 2756.49     252 2765.19
   256.3 2766.17   273.5 2766.53   290.7 2768.21   312.2 2768.45   320.8 2767.74
   331.2 2768.76   368.1 2768.74   383.7 2770.23   393.9 2772.65405.3553 2773.14
#Mann= 6 ,-1,0
       0      .1       0      30     .05       0     174    .045       0
  218.52     .05       0  276.42     .06       0  386.42      .1       0
#XS Ineff= 2 , 0
           167.4    2763   225.2          2764.5
Permanent Ineff=
       F       F
Bank Sta=174,218.52
XS Rating Curve= 0 ,0
Exp/Cntr(USF)=0,0
Exp/Cntr=0.5,0.3

Type RM Length L Ch R = 1 ,9857    ,343.8,354.5,368.6
BEGIN DESCRIPTION:
xs 1
END DESCRIPTION:
XS GIS Cut Line= 3
2226145.58784982517455.0184685142226147.41621776517531.200465751
2226237.61570249517805.455655807
#Sta/Elev= 30
       0 2783.44     2.2 2781.31    10.2 2774.93    14.2 2772.52    30.2 2765.79
    38.2 2764.28    50.2 2762.89    66.2 2759.34    81.5 2753.85    90.9    2752
   103.6    2752   116.2 2753.04   120.4 2752.78   124.6    2752   138.6 2746.78
   147.1 2745.08   154.4 2743.71   162.5 2743.19   196.2  2743.4  201.75 2745.07
   204.6 2746.38   214.6 2757.82   217.2 2760.39   221.5 2763.13   234.1 2764.27
   267.8 2764.62   283.5 2765.71   347.8 2770.69   360.4 2772.31364.9112 2773.52
#Mann= 4 ,-1,0
       0      .1       0   147.1    .045       0  201.75     .06       0
   286.2      .1       0
Bank Sta=147.1,201.75
XS Rating Curve= 0 ,0
Exp/Cntr(USF)=0,0
Exp/Cntr=0.3,0.1

Type RM Length L Ch R = 1 ,9502    ,317.6,327.7,340.5
XS GIS Cut Line= 4
2225835.06429077517406.1240163552225825.50323102517631.479259295
 2225830.0904268517787.4439157572225880.04818998517905.276782589
#Sta/Elev= 30
       0 2790.93    27.1  2779.2    63.1    2761    75.1 2757.51   103.1 2759.79
   111.2 2759.44   139.2 2754.09   155.2  2753.5     167 2749.49   171.2  2748.9
   191.2 2748.38   211.2 2746.59   231.3 2746.85   235.3 2746.12  244.33 2742.01
   251.3 2740.09   263.3 2740.04   295.3 2740.24   302.9    2742   311.1 2746.45
   323.3 2756.91   327.3 2758.78   339.3 2759.47   343.3 2758.22   351.3 2759.17
   379.3 2759.88   387.8 2764.29   405.2 2768.18   433.3 2772.85   509.6 2782.44
#Mann= 5 ,-1,0
       0      .1       0  244.33    .045       0   302.9      .1       0
  325.56     .06       0  431.59      .1       0
Bank Sta=244.33,302.9
XS Rating Curve= 0 ,0
Exp/Cntr=0.3,0.1

Type RM Length L Ch R = 1 ,9175    ,339.8,339,339.6
XS GIS Cut Line= 2
2225564.53165594517370.0588311312225448.18056095517866.702586811
#Sta/Elev= 30
       0 2788.41    15.5 2786.47    22.9 2784.03    60.7 2759.53    68.9 2756.38
   134.7 2753.61     147 2751.77   196.3 2748.51   212.7 2742.78   229.2 2741.75
   242.5 2738.87   253.8 2736.97   282.1 2736.78   294.9 2736.84  301.34 2738.85
   307.2 2743.75   311.3 2748.61   315.4 2751.71   323.7 2753.47   348.3 2753.92
   364.7 2752.82   385.3 2755.65   393.5 2752.27   430.5 2755.14   446.9 2751.81
   467.4 2752.12   471.6 2752.94   479.8 2756.93   496.2 2767.09   510.1 2771.52
#Mann= 5 ,-1,0
       0      .1       0   242.5    .045       0  301.34      .1       0
     370     .06       0     480      .1       0
Bank Sta=242.5,301.34
XS Rating Curve= 0 ,0
Exp/Cntr=0.3,0.1

Type RM Length L Ch R = 1 ,8836    ,343.1,367.8,387.6
XS GIS Cut Line= 3
2225314.51947124 517196.668677572225192.47021362   517472.074206
2225117.66428601517824.729523485
#Sta/Elev= 30
       0 2786.93    26.8 2781.48    57.4 2778.03    84.8 2773.34   111.3 2767.15
   149.3 2753.22   262.9 2746.22   306.5 2745.58   322.8 2743.24   326.9 2741.48
  333.99 2735.99   339.2 2734.07   367.8 2733.89   379.8    2736   400.5 2738.19
   441.4 2739.95   445.5 2741.24   457.7 2748.91   465.9  2750.6   482.3 2750.88
   501.5 2749.18   531.4 2751.37   547.7 2748.65   562.2 2750.26   580.4 2759.98
   633.6 2795.17   637.7  2798.9   646.5 2813.48   649.9 2815.95   661.7 2820.94
#Mann= 7 ,-1,0
       0      .1       0     180     .05       0     260      .1       0
  333.99    .045       0   379.8      .1       0  471.24     .06       0
  571.24      .1       0
Bank Sta=333.99,379.8
XS Rating Curve= 0 ,0
Exp/Cntr=0.3,0.1

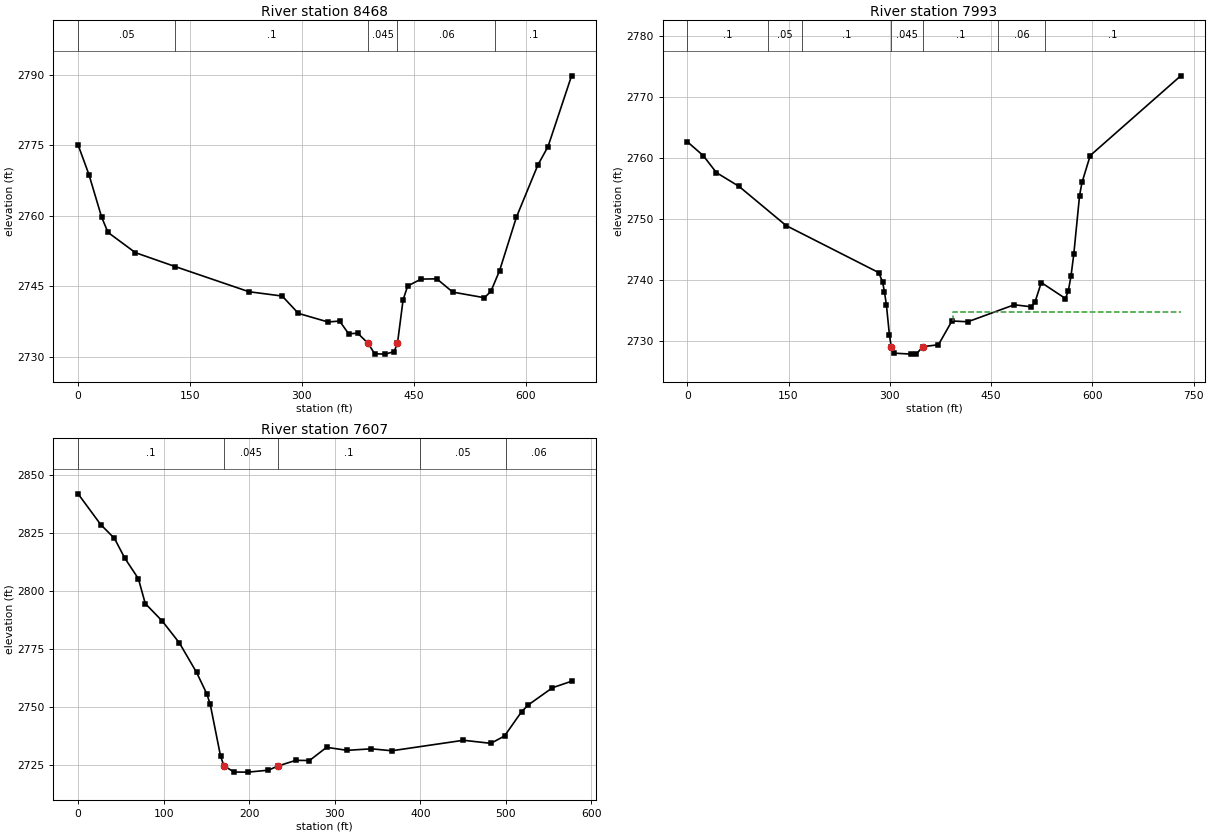
Type RM Length L Ch R = 1 ,8468    ,482.2,474.6,465.8
XS GIS Cut Line= 3
2225142.01106006517170.466083578 2224721.1358474517538.588544785
2224674.11709068517629.185661406
#Sta/Elev= 30
       0 2775.05    14.6 2768.71    31.6 2759.64    40.1 2756.43    76.8 2752.12
     130 2749.17   228.9 2743.81   273.5 2742.89   295.2  2739.2   334.9 2737.37
   350.4 2737.57   362.6 2734.85   374.6 2734.99   388.7 2732.81   397.3 2730.61
   411.4 2730.53   423.3 2731.05  427.94 2732.81   435.5 2742.09   441.6 2745.02
   459.6  2746.5   480.7 2746.55     502 2743.73   544.5 2742.53   553.2 2743.91
   564.8  2748.3   587.3 2759.66   616.1 2770.78   629.7  2774.7661.2228 2789.75
#Mann= 5 ,-1,0
       0     .05       0     130      .1       0   388.7    .045       0
  427.94     .06       0  559.15      .1       0
Bank Sta=388.7,427.94
XS Rating Curve= 0 ,0
Exp/Cntr(USF)=0,0
Exp/Cntr=0.3,0.1

Type RM Length L Ch R = 1 ,7993    ,411.3,386.3,357.9
XS GIS Cut Line= 4
2224787.65018619516878.0323527132224573.19878355517025.969416562
 2224404.6193387517250.7420096982224366.77497353517436.523438718
#Sta/Elev= 30
       0 2762.65    23.7 2760.37    43.1  2757.6    76.7 2755.34   146.4 2748.94
   283.6 2741.25   289.3 2739.74   292.1 2738.12     295 2735.98   299.5 2731.05
   302.2 2729.12   306.4 2728.08   332.1 2727.92   339.5 2727.95   348.9 2729.14
   372.1 2729.45   392.1 2733.34   415.6 2733.21   484.5 2735.99   509.5 2735.66
     515 2736.38   524.5 2739.62   560.3 2737.01   564.4  2738.2   568.5 2740.68
   572.6 2744.23   581.2 2753.85   584.8 2755.99     597 2760.39731.0904 2773.42
#Mann= 7 ,-1,0
       0      .1       0     120     .05       0     170      .1       0
   302.2    .045       0   348.9      .1       0  460.53     .06       0
  530.53      .1       0
#XS Ineff= 2 , 0
                          392.97         2734.84
Permanent Ineff=
       F       F
Bank Sta=302.2,348.9
XS Rating Curve= 0 ,0
Exp/Cntr(USF)=0,0
Exp/Cntr=0.3,0.1

Type RM Length L Ch R = 1 ,7607    ,497.5,494.7,487.3
XS GIS Cut Line= 2
 2224183.2871424516742.7100772542224178.69994662517319.549946372
#Sta/Elev= 30
       0 2841.71    26.5 2828.44    42.5 2822.52    54.5 2814.07    70.5 2805.14
    78.5 2794.47    98.5 2786.86   118.5 2777.44   138.5 2764.78   150.5 2755.55
   154.5 2750.99   166.5 2728.79   170.5  2724.5   182.5 2721.88   198.5 2721.84
   222.5 2722.67   233.2 2724.43   254.5 2726.91   270.5 2726.84   290.5 2732.52
   314.5 2731.23   342.9 2731.88   366.7 2731.04   450.5 2735.56   482.5 2734.24
   498.5 2737.41   518.5 2747.89   526.5 2750.85   554.5 2758.18576.8581 2760.99
#Mann= 5 ,-1,0
       0      .1       0   170.5    .045       0   233.2      .1       0
     400     .05       0     500     .06       0
Bank Sta=170.5,233.2
XS Rating Curve= 0 ,0
Exp/Cntr(USF)=0,0
Exp/Cntr=0.3,0.1