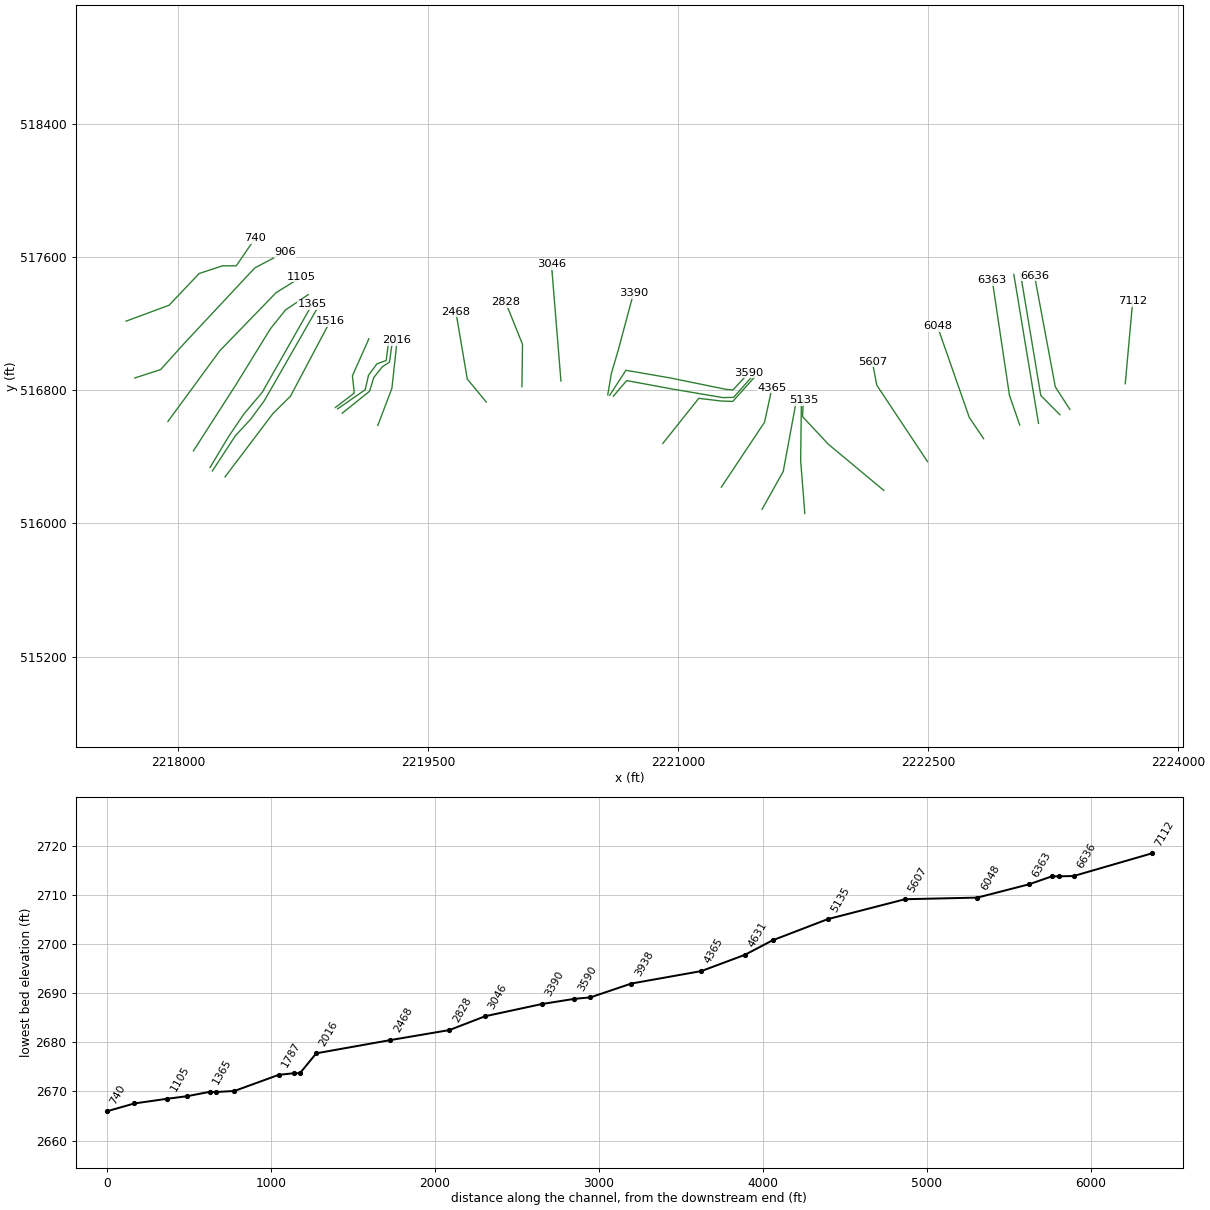
HEC-RAS study BIGSPRFK.prj: BIGSPRFK

--- BIGSPRFK.g01 (geometry) --- (continued)

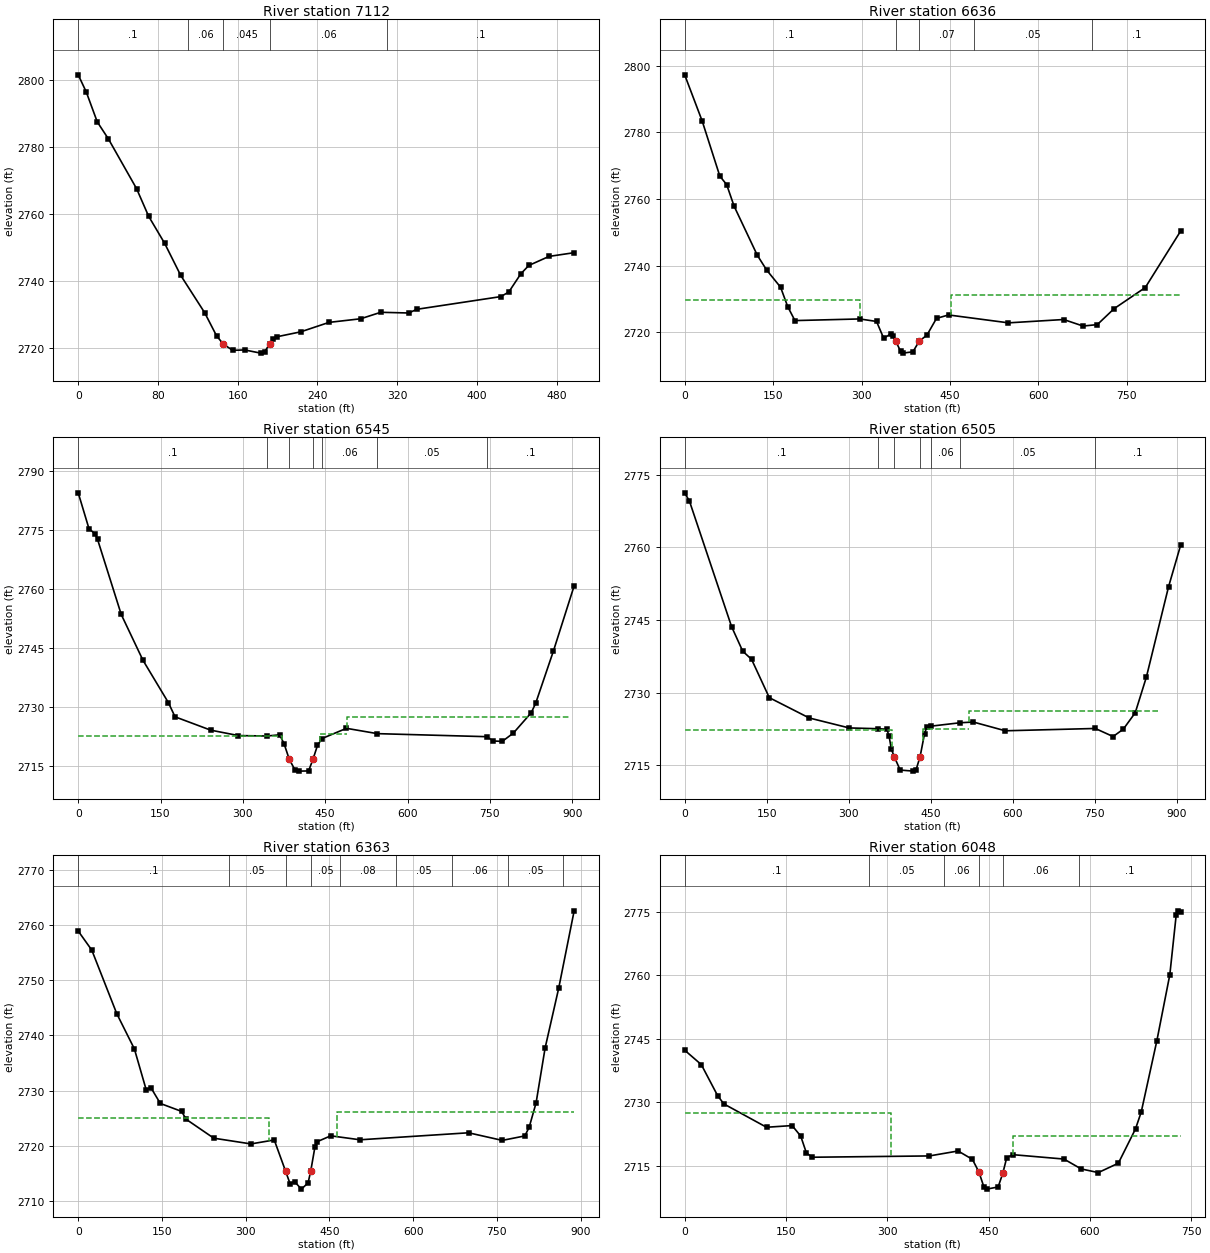
Type RM Length L Ch R = 1 ,7112    ,467,476.3,486.4
XS GIS Cut Line= 2
     2223681.777516838.8041382532223726.66810554517334.471306599
#Sta/Elev= 30
       0 2801.42     8.1 2796.29    19.1 2787.39    30.2 2782.35    58.6 2767.45
    70.7 2759.22    86.7 2751.18   102.8 2741.63   126.9 2730.47   138.9 2723.54
   145.7 2721.08     155 2719.24   167.1 2719.36   183.1 2718.41   187.1 2718.76
   192.2 2721.23   195.2 2722.62   199.2 2723.28   223.3 2724.76   251.7 2727.58
   283.5 2728.66   303.6 2730.59   331.7 2730.38   339.8 2731.48   424.1 2735.27
   432.1 2736.64   444.2 2742.07   452.2 2744.56   472.5 2747.26   497.7 2748.37
#Mann= 5 ,-1,0
       0      .1       0     110     .06       0   145.7    .045       0
   192.2     .06       0     310      .1       0
Bank Sta=145.7,192.2
XS Rating Curve= 0 ,0
Exp/Cntr=0.3,0.1

Type RM Length L Ch R = 1 ,6636    ,91.7,90.4,89.9
BEGIN DESCRIPTION:
xs 4
END DESCRIPTION:
XS GIS Cut Line= 3
 2223349.5643097516684.2233310812223262.40758991 516819.54560654
2223137.40650495517488.129391224
#Sta/Elev= 30
       0 2797.27    29.7 2783.41    59.6  2766.9    71.2 2764.35    83.8 2757.89
   123.2 2743.15   139.1 2738.71   162.6 2733.59   174.8 2727.73     187 2723.57
   296.9 2724.06   325.4 2723.31   337.6 2718.24   349.8 2719.63   353.9 2719.09
   357.9 2717.39   366.1 2714.42   370.2 2713.81   387.1 2714.21  397.78 2717.39
   410.9 2719.22   427.1 2724.23   447.5 2725.26   549.2 2722.89   642.8 2723.89
   675.7 2721.93   699.8 2722.36   728.3 2727.14   781.2 2733.48841.1296  2750.4
#Mann= 5 ,-1,0
       0      .1       0   357.9    .045       0  397.78     .07       0
  490.96     .05       0  690.96      .1       0
#XS Ineff= 2 , 0
          297.46 2729.77  451.83         2731.16
Permanent Ineff=
       F       F
Bank Sta=357.9,397.78
XS Rating Curve= 0 ,0
Exp/Cntr(USF)=0,0
Exp/Cntr=0.5,0.3

Type RM Length L Ch R = 1 ,6545    ,40.7,40.8,40.7
BEGIN DESCRIPTION:
xs 3
END DESCRIPTION:
XS GIS Cut Line= 3
2223289.93076458516652.1129606332223175.25087012516767.939654034
  2223053.690182517498.450581725
#Sta/Elev= 30
       0 2784.36    19.6 2775.27    30.9 2773.91    35.3 2772.52    78.4 2753.49
     118 2741.87   164.3 2731.13   176.4 2727.53   241.3 2724.15   291.9 2722.77
     344 2722.66     367 2722.96   375.1 2720.69   384.5 2716.75   395.4 2713.93
   403.1 2713.75   419.7  2713.8   427.8 2716.78   435.9 2720.27     444 2722.01
   488.7 2724.61   545.1 2723.26   744.1 2722.49   756.3  2721.4   772.5 2721.29
   792.8  2723.4   825.2 2728.54   833.3 2730.91   865.8 2744.23903.5508 2760.76
#Mann= 7 ,-1,0
       0      .1       0     344     .07       0   384.5    .045       0
   427.8     .07       0     444     .06       0   545.1     .05       0
   744.1      .1       0
#XS Ineff= 3 ,-1
       0     372 2722.72   439.8  490.14 2723.06  490.14  893.52 2727.49
Permanent Ineff=
       F       F       F
Bank Sta=384.5,427.8
XS Rating Curve= 0 ,0
Exp/Cntr(USF)=0,0
Exp/Cntr=0.5,0.3

Type RM Length L Ch R = 1 ,6505    ,142,141.7,140.9
BEGIN DESCRIPTION:
xs 2
END DESCRIPTION:
XS GIS Cut Line= 2
2223161.48928279516600.5070081272223013.55221894517495.010184891
#Sta/Elev= 30
       0  2771.3     8.8 2769.56    85.8 2743.62   106.1 2738.56   122.3 2736.87
   154.7 2728.95   227.7 2724.75   300.7 2722.69   353.4 2722.53   369.6 2722.42
   373.7 2720.98   377.7 2718.37     383 2716.77     394 2713.98   418.3 2713.76
   422.7 2713.93   430.4 2716.77   438.5  2721.5   442.6 2722.88   450.5 2723.06
   503.4 2723.76   527.7 2723.91   586.2  2722.1   750.7 2722.58   783.2 2720.91
   801.9 2722.44   823.7 2725.83     844 2733.18   884.5 2751.84906.6539 2760.46
#Mann= 7 ,-1,0
       0      .1       0   353.4     .07       0     383    .045       0
   430.4     .07       0   450.5     .06       0   503.4     .05       0
   750.7      .1       0
#XS Ineff= 4 ,-1
       0  378.22 2722.24  436.02  519.442722.385  519.44  868.17 2726.18
  868.17906.65392722.385
Permanent Ineff=
       F       F       F       F
Bank Sta=383,430.4
XS Rating Curve= 0 ,0
Exp/Cntr(USF)=0,0
Exp/Cntr=0.5,0.3

Type RM Length L Ch R = 1 ,6363    ,308.9,314.6,321
BEGIN DESCRIPTION:
xs 1
END DESCRIPTION:
XS GIS Cut Line= 3
2223049.10298622516590.1858176262222987.17584321516769.086452979
 2222883.9639382517460.606216554
#Sta/Elev= 30
       0 2758.93    24.3 2755.48    69.1 2743.94   100.6 2737.56   121.7 2730.17
   130.2 2730.53   147.1 2727.66   185.2 2726.22   193.5 2724.78   242.9 2721.36
   309.5 2720.32   351.2 2721.04   371.4 2715.41   379.5 2713.11   387.6 2713.49
   399.8 2712.12   411.8 2713.25  416.59  2715.4     424 2719.72     428 2720.72
   452.4 2721.79   504.9 2721.07   699.3 2722.34   759.7 2720.96   800.1 2721.77
   807.9 2723.34   820.3 2727.77   836.5 2737.74   860.8 2748.56888.4954  2762.6
#Mann= 9 ,-1,0
       0      .1       0  269.32     .05       0   371.4    .045       0
  416.59     .05       0  469.32     .08       0  569.32     .05       0
  669.32     .06       0  769.32     .05       0  869.32      .1       0
#XS Ineff= 2 , 0
          342.19 2725.09   463.1         2726.06
Permanent Ineff=
       F       F
Bank Sta=371.4,416.59
XS Rating Curve= 0 ,0
Exp/Cntr(USF)=0,0
Exp/Cntr=0.3,0.1

Type RM Length L Ch R = 1 ,6048    ,429.6,441.1,450
XS GIS Cut Line= 3
 2222832.3579857516508.7630925612222746.34806485516636.057775409
2222554.83264111517184.227670913
#Sta/Elev= 30
       0 2742.27    24.6 2738.87    48.8 2731.52      58 2729.57   121.2 2724.05
   159.1 2724.45   171.8 2721.96   180.2 2717.99   188.7 2716.96   362.4 2717.27
   404.8 2718.44     426 2716.46   435.7 2713.45   442.9 2709.98   447.2 2709.42
   464.1 2709.93     471 2713.16   476.8 2716.85   485.9 2717.57   561.6 2716.53
     587  2714.2   612.4 2713.33   642.1 2715.55   667.5 2723.66     676 2727.67
     699 2744.43   718.3 2760.13   727.7 2774.18   730.8 2775.23734.2903 2775.04
#Mann= 6 ,-1,0
       0      .1       0  273.63     .05       0  383.63     .06       0
   435.7    .045       0     471     .06       0  583.63      .1       0
#XS Ineff= 2 , 0
          305.65 2727.38  485.81         2721.95
Permanent Ineff=
       F       F
Bank Sta=435.7,471
XS Rating Curve= 0 ,0
Exp/Cntr(USF)=0,0
Exp/Cntr=0.3,0.1

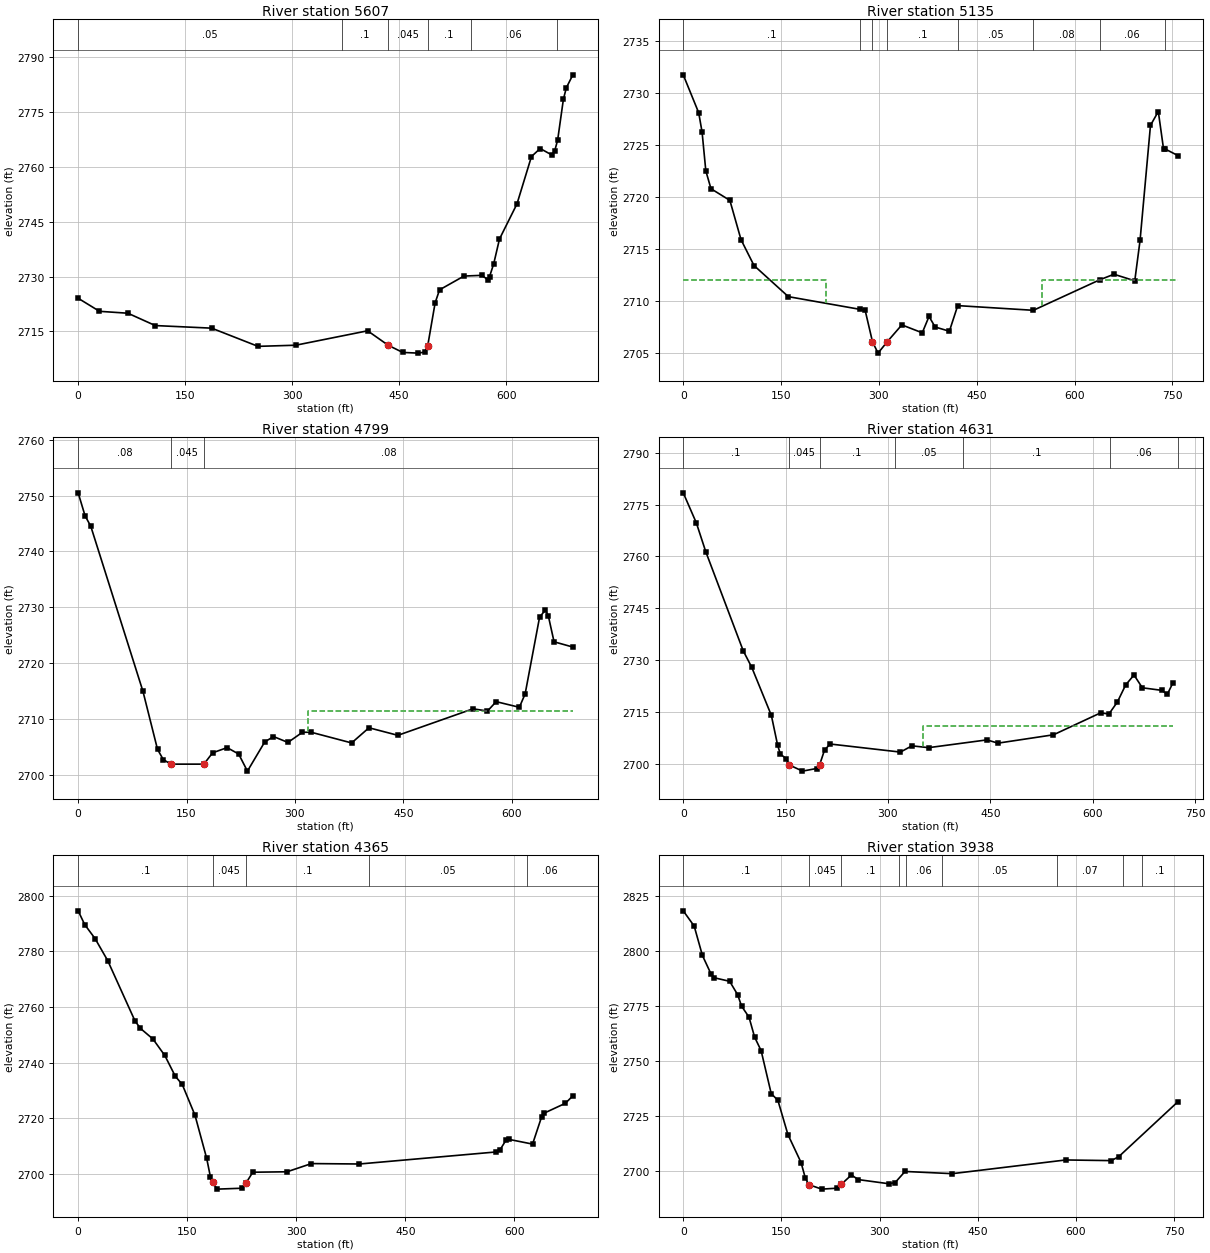
Type RM Length L Ch R = 1 ,5607    ,452.9,472.3,482.1
XS GIS Cut Line= 3
2222495.60523272516371.1052221642222191.29737568516829.866797041
2222164.66595251516970.099618474
#Sta/Elev= 30
       0 2724.08    29.9 2720.51    69.7 2719.99   108.1 2716.62   187.1 2715.91
   252.1 2710.94   304.9 2711.25   405.7 2715.19   434.5 2711.24   454.9 2709.28
   476.6 2709.09   485.9 2709.38  489.96 2711.16   500.3 2722.83   506.5 2726.38
   540.7 2730.14   565.8 2730.34   574.2 2729.13   576.5 2729.94   582.4  2733.5
   590.5 2740.27     615 2749.85   635.3 2762.79   647.5 2764.98   663.8 2763.23
   667.9 2764.35     672 2767.29   680.1 2778.48   684.2 2781.58   693.3 2785.11
#Mann= 6 ,-1,0
       0     .05       0     370      .1       0   434.5    .045       0
  489.96      .1       0     550     .06       0  670.51      .1       0
Bank Sta=434.5,489.96
XS Rating Curve= 0 ,0
Exp/Cntr=0.3,0.1

Type RM Length L Ch R = 1 ,5135    ,357.7,335.7,308
XS GIS Cut Line= 4
2222233.72893663516197.9805785832221900.93096762 516475.27964809
2221745.71541154516641.3003564982221751.88204799516739.244708876
#Sta/Elev= 30
       0 2731.74    23.7  2728.1    28.9 2726.24    34.6 2722.53    42.5 2720.81
    71.5 2719.69    88.6 2715.92   108.5 2713.44   161.2 2710.45   270.3 2709.24
   278.9 2709.15   290.2 2706.12   298.7 2705.03   312.9 2706.13   335.2 2707.74
   366.5 2706.98   376.9 2708.55   386.2 2707.54   408.1 2707.13   420.9 2709.59
   536.9 2709.14   638.8 2712.07   660.5  2712.6   692.4 2711.97   700.5 2715.84
   716.5 2726.89   728.5 2728.22   736.5 2724.64   738.1 2724.65   758.6 2723.99
#Mann= 8 ,-1,0
       0      .1       0   270.3     .08       0   290.2    .045       0
   312.9      .1       0   420.9     .05       0   536.9     .08       0
   638.8     .06       0   738.1      .1       0
#XS Ineff= 2 , 0
          218.72 2712.04     550         2712.04
Permanent Ineff=
       F       F
Bank Sta=290.2,312.9
XS Rating Curve= 0 ,0
Exp/Cntr(USF)=0,0
Exp/Cntr=0.3,0.1

Type RM Length L Ch R = 1 ,4799    ,187.6,168.2,142.7
XS GIS Cut Line= 3
2221759.78344094516059.7332183682221734.78609161516376.731029468
2221739.30971526516743.183780645
#Sta/Elev= 30
       0 2750.48     9.5  2746.4    17.5 2744.49    89.7 2714.98   109.8 2704.63
   117.8 2702.79   128.3 2701.98     174 2701.98     186    2704   206.1 2704.93
   222.1 2703.79   234.2 2700.73   258.2 2705.95   270.3 2706.91   290.3 2705.86
   310.4 2707.68   322.4 2707.68   378.4 2705.77   402.4 2708.48   442.4 2707.13
   546.4 2711.87   566.4 2711.47   578.4 2713.15   610.5 2712.14   618.5 2714.54
   638.5 2728.27   646.5 2729.52   650.5 2728.53   658.5 2723.85   684.5 2722.91
#Mann= 3 ,0,0
       0     .08       0   128.3    .045       0     174     .08       0
#XS Ineff= 2 , 0
                          318.38         2711.44
Permanent Ineff=
       F       F
Bank Sta=128.3,174
XS Rating Curve= 0 ,0
Exp/Cntr(USF)=0,0
Exp/Cntr=0.3,0.1

Type RM Length L Ch R = 1 ,4631    ,268.1,265.9,262
XS GIS Cut Line= 3
2221503.21800894516084.4474830712221630.32003023516311.979691385
2221713.31430539516760.877081398
#Sta/Elev= 30
       0 2778.44    19.2 2769.72    32.9 2761.43    87.9 2732.66   100.4 2727.86
   129.1 2713.95   138.3  2705.3   142.3 2702.73   151.2 2701.35   155.1 2699.61
   174.7 2697.79   195.3 2698.55  199.73 2699.56     207 2703.88   215.2 2705.65
   318.2 2703.31   335.1 2705.12   359.5 2704.59   444.9 2706.84   461.2  2705.9
   542.5 2708.32   611.7 2714.69   623.7 2714.34   636.1 2717.81   648.3 2722.78
   660.5 2725.65   672.7 2721.94   701.2  2721.2   709.3 2720.06   717.1 2723.19
#Mann= 7 ,-1,0
       0      .1       0   155.1    .045       0  199.73      .1       0
     310     .05       0     410      .1       0  624.86     .06       0
  724.86      .1       0
#XS Ineff= 2 , 0
                          350.83         2710.73
Permanent Ineff=
       F       F
Bank Sta=155.1,199.73
XS Rating Curve= 0 ,0
Exp/Cntr(USF)=0,0
Exp/Cntr=0.3,0.1

Type RM Length L Ch R = 1 ,4365    ,430,427.4,423.5
XS GIS Cut Line= 3
2221259.18389498516217.9211113442221518.12639522516607.387801794
2221563.06370923516815.272454882
#Sta/Elev= 30
       0 2794.59       9 2789.65    23.3 2784.59    40.6 2776.71    78.1 2755.03
    85.6 2752.31   102.9 2748.47   119.2 2742.55   133.6 2735.09   143.2 2732.12
   160.7 2721.06   176.8 2705.53   181.9 2698.92   184.8 2696.98   191.2 2694.48
   224.9  2694.8     231 2696.73   240.2 2700.56   287.3 2700.72   320.9 2703.67
   386.8 2703.52   575.2 2707.86     580 2708.52   588.2 2711.98   592.3 2712.39
     625 2710.68   637.3 2720.37   641.4 2721.87   670.1 2725.35   680.4 2728.03
#Mann= 5 ,-1,0
       0      .1       0   184.8    .045       0     231      .1       0
     400     .05       0  617.69     .06       0
Bank Sta=184.8,231
XS Rating Curve= 0 ,0
Exp/Cntr=0.3,0.1

Type RM Length L Ch R = 1 ,3938    ,322.3,249.4,186.7
BEGIN DESCRIPTION:
xs 4
END DESCRIPTION:
XS GIS Cut Line= 5
2220908.02935671516480.0931189472221123.62755829516750.737669866
2221258.94983375516734.6824846422221327.75777042516732.388886752
2221464.22684483 516884.91314638
#Sta/Elev= 30
       0 2818.27    16.7 2811.35    29.3    2798    42.3  2789.7    47.4 2787.88
    70.9 2786.28    83.2 2780.15    89.1    2775   100.5 2770.01     109 2760.97
     119 2754.78   134.4 2735.31   144.6 2732.25   159.9 2716.73     180 2704.01
   186.4  2697.1   191.6 2694.01   211.5 2691.94   234.3 2692.35   241.7 2694.19
     257 2698.37   267.3 2696.27     314 2694.39   323.6 2694.89   338.9 2699.96
     411 2698.96   584.4 2705.18     654 2704.88   665.3 2706.65755.8035 2731.62
#Mann= 9 ,-1,0
       0      .1       0   191.6    .045       0   241.7      .1       0
     330     .05       0     340     .06       0  396.02     .05       0
  571.14     .07       0  671.14     .06       0  701.14      .1       0
Bank Sta=191.6,241.7
XS Rating Curve= 0 ,0
Exp/Cntr(USF)=0,0
Exp/Cntr=0.5,0.3

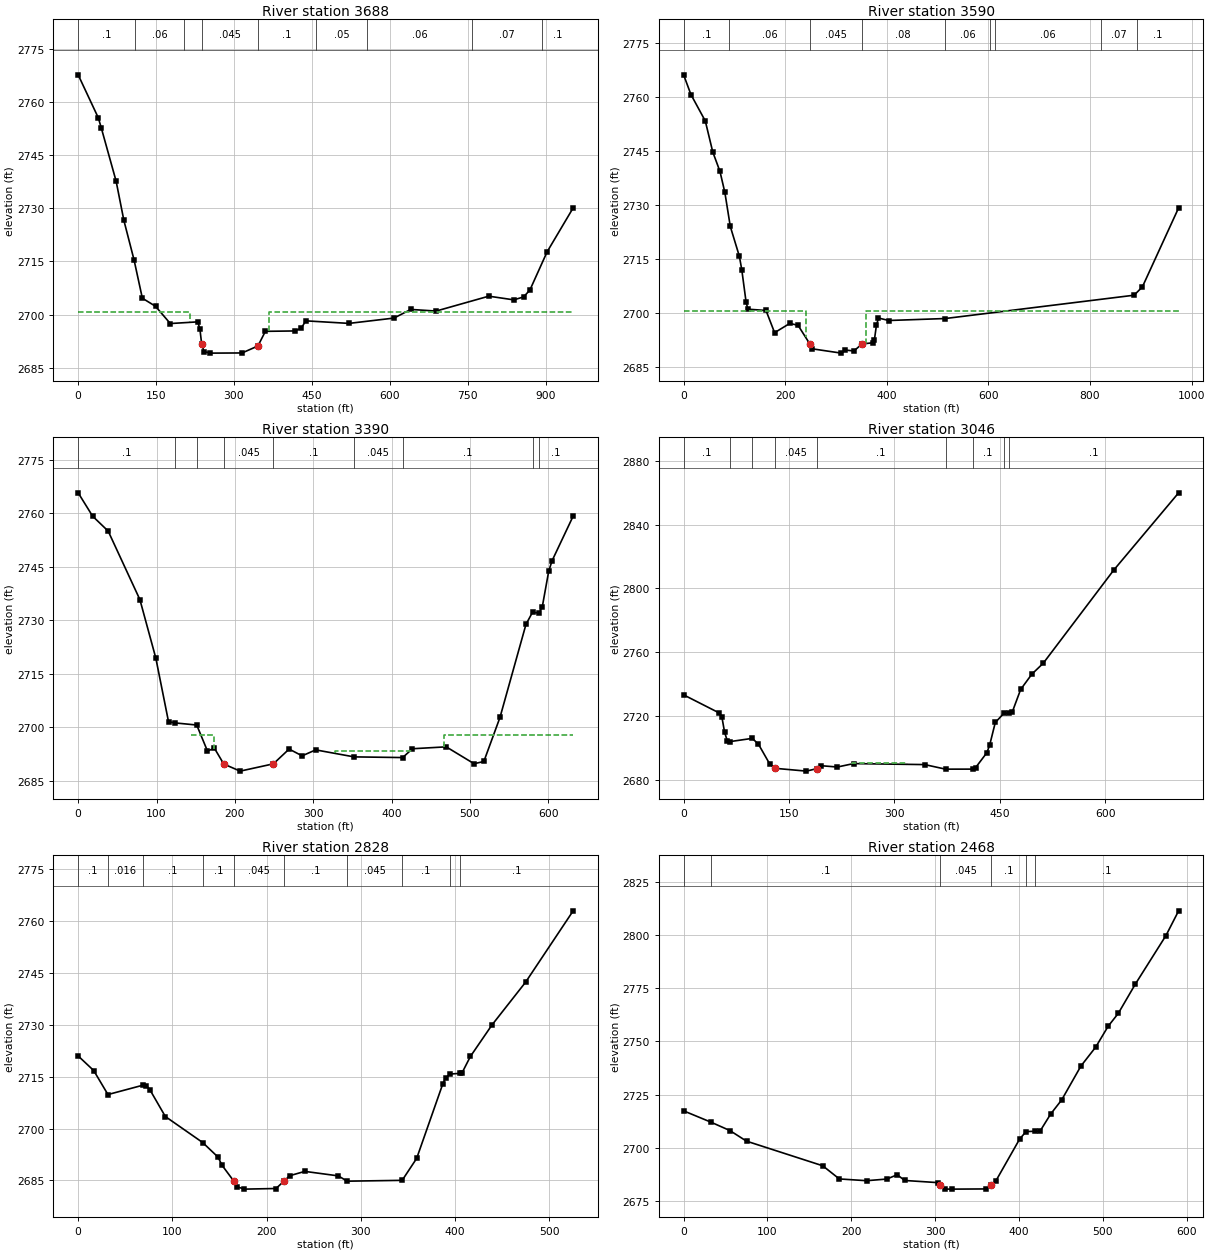
Type RM Length L Ch R = 1 ,3688    ,86.6,98,101.6
BEGIN DESCRIPTION:
xs 3
END DESCRIPTION:
XS GIS Cut Line= 6
2220611.00843007516763.3524582562220691.28435619516857.389971711
2220969.95649972516805.7840192052221266.97742636516755.324865644
 2221332.3449662516756.4716645882221451.61205643516890.647141103
#Sta/Elev= 30
       0 2767.66    38.8 2755.52    44.5  2752.7    73.1 2737.64      88 2726.59
   107.6 2715.44   123.6 2704.63     149 2702.34   177.4 2697.48   230.3 2697.95
   234.4 2695.96   237.9 2691.59   242.5 2689.56   254.7 2689.13   315.7 2689.18
  346.17 2691.15   360.5 2695.28   417.4 2695.39   429.6 2696.17   438.3 2698.24
   521.4 2697.52   608.1 2699.02   640.6 2701.46   689.3    2701   790.7  2705.2
   838.9 2704.16   857.7 2704.99   869.8 2706.91   903.1 2717.73953.2268 2730.12
#Mann= 9 ,-1,0
       0      .1       0     110     .06       0  203.64      .1       0
   237.9    .045       0  346.17      .1       0  457.05     .05       0
  557.05     .06       0  758.33     .07       0  893.71      .1       0
#XS Ineff= 2 , 0
           215.9 2700.62   368.2         2700.62
Permanent Ineff=
       F       F
Bank Sta=237.9,346.17
XS Rating Curve= 0 ,0
Exp/Cntr(USF)=0,0
Exp/Cntr=0.5,0.3

Type RM Length L Ch R = 1 ,3590    ,132.7,200.5,271.7
BEGIN DESCRIPTION:
xs 2
END DESCRIPTION:
XS GIS Cut Line= 6
2220589.21925012516769.0864529792220686.69716041516919.317114717
2220957.34171133 516872.298357992221287.61980736 516804.63722026
2221328.90456937516801.1968234272221425.23568071516905.555527383
#Sta/Elev= 30
       0 2766.28    14.4  2760.8    42.7 2753.43    57.3 2744.85    71.6 2739.38
    81.2 2733.54    91.9 2724.08   109.8 2715.76   114.5 2712.04     123 2703.01
   126.6 2701.06   162.2  2700.7   179.1 2694.52     209  2697.1   225.2 2696.58
   248.1 2691.47   253.6 2690.02   310.4 2688.83   318.6 2689.68   335.2 2689.43
   351.1 2691.37   372.6 2691.72   375.4 2692.37   379.5 2696.54   383.6  2698.6
   403.9 2697.91     515 2698.46   886.8 2704.95   903.1 2707.28974.3717 2729.26
#Mann= 9 ,-1,0
       0      .1       0      90     .06       0   248.1    .045       0
   351.1     .08       0  513.78     .06       0  603.78     .05       0
  613.78     .06       0  820.92     .07       0  892.35      .1       0
#XS Ineff= 2 , 0
             240  2700.5   359.1          2700.5
Permanent Ineff=
       F       F
Bank Sta=248.1,351.1
XS Rating Curve= 0 ,0
Exp/Cntr(USF)=0,0
Exp/Cntr=0.5,0.3

Type RM Length L Ch R = 1 ,3390    ,328.9,343.9,361.7
BEGIN DESCRIPTION:
start of detailed reach
END DESCRIPTION:
XS GIS Cut Line= 4
2220577.69406923516771.4475691362220598.75431691516898.002332309
2220640.82520262517040.8778028422220732.47507886517383.245490773
#Sta/Elev= 30
       0  2765.7    18.5 2759.15    38.3 2754.98    78.8 2735.78    99.1 2719.41
   115.3 2701.61   123.4 2701.27   151.3 2700.67     165 2693.39   173.9 2694.16
   185.8 2689.75   206.7 2687.76   249.1  2689.8   269.2 2693.94   285.8 2692.04
   303.1 2693.71   352.1 2691.75   414.1 2691.56   426.6 2694.03   469.7 2694.56
   505.3 2689.83   517.7 2690.46   538.3 2702.81   571.5 2728.89   579.8 2732.24
   588.1 2732.03   592.3 2733.81   600.5 2743.77   604.7 2746.65   631.7 2759.19
#Mann= 9 ,-1,0
       0      .1       0   123.4    .016       0   151.3      .1       0
   185.8    .045       0   249.1      .1       0   352.1    .045       0
   414.1      .1       0   579.8    .025       0   588.1      .1       0
#XS Ineff= 4 ,-1
  143.41  172.93 2697.84  268.69  306.432693.547  327.26   428.4  2693.4
   466.7   631.72697.773
Permanent Ineff=
       F       F       F       F
Bank Sta=185.8,249.1
XS Rating Curve= 0 ,0
Exp/Cntr(USF)=0,0
Exp/Cntr=0.3,0.1

Type RM Length L Ch R = 1 ,3046    ,221.8,218.1,215.4
XS GIS Cut Line= 2
2220296.86960927 516854.962037442220239.80273154517557.345753591
#Sta/Elev= 30
       0 2733.18    50.4 2721.88    54.4 2719.48    58.4 2709.58    62.4 2704.08
    65.8 2703.81    97.8 2705.86   106.6 2702.15   122.6 2689.77  129.83 2687.07
   174.8 2685.29   189.5 2686.84   194.9 2688.72   218.9 2687.87   241.9 2690.02
   343.3 2689.39   372.9 2686.53   411.6 2686.55   415.6 2687.45   431.6 2696.79
   435.6 2701.44   443.7 2715.82   455.7 2721.47   463.7 2721.83   467.8 2722.31
   479.8 2736.55   495.8  2746.2   511.9 2752.98   612.2 2811.43704.6982 2860.01
#Mann= 9 ,-1,0
       0      .1       0    65.8    .016       0    97.8      .1       0
  129.83    .045       0   189.5      .1       0   372.9    .045       0
   411.6      .1       0   455.7    .025       0   463.7      .1       0
#XS Ineff= 1 ,-1
  239.44  317.862690.268
Permanent Ineff=
       F
Bank Sta=129.83,189.5
XS Rating Curve= 0 ,0
Exp/Cntr(USF)=0,0
Exp/Cntr=0.3,0.1

Type RM Length L Ch R = 1 ,2828    ,348.2,360.3,362.5
XS GIS Cut Line= 3
2220062.83853456516820.6924054852220066.27893139517075.281771179
2219965.36062427 517326.43074004
#Sta/Elev= 30
       0 2720.99    16.5 2716.77    31.6 2709.83    68.5 2712.52    72.5 2712.43
    76.2 2711.18    92.5 2703.48   132.1 2695.96   148.5 2691.72   152.5 2689.44
   165.4 2684.71   168.5 2683.17   176.5 2682.48     210 2682.66   218.1 2684.73
   224.5 2686.36   240.5 2687.61   276.1 2686.31   285.4 2684.78   343.8 2685.02
   359.2 2691.37   386.8 2712.82   389.9 2714.63   394.6 2715.75   405.3 2715.97
   407.5 2716.19   416.2 2720.84   439.1 2729.95   474.8 2742.33525.2791 2762.96
#Mann= 10 ,-1,0
       0      .1       0    31.6    .016       0    68.5      .1       0
   132.1      .1       0   165.4    .045       0   218.1      .1       0
   285.4    .045       0   343.8      .1       0   394.6    .025       0
   405.3      .1       0
Bank Sta=165.4,218.1
XS Rating Curve= 0 ,0
Exp/Cntr(USF)=0,0
Exp/Cntr=0.3,0.1

Type RM Length L Ch R = 1 ,2468    ,447.7,451.8,415
Node Name=A
XS GIS Cut Line= 3
2219849.11598529516728.5784072262219735.06294018516866.566042495
2219666.21486771517272.062525928
#Sta/Elev= 30
       0 2717.31    32.3 2712.03    55.1 2708.05      75 2703.04   165.9 2691.44
   185.7 2685.24   218.2 2684.41   242.5 2685.19   254.7 2687.23   263.6 2684.52
   303.4  2683.5   305.7 2682.27   311.5 2680.47   319.6 2680.44   360.2 2680.53
  366.75 2682.21   372.4 2684.32   400.8 2704.07   408.4 2707.54   419.6 2707.71
   425.1 2707.76   437.7 2715.79   450.9 2722.48   473.8 2738.41   491.5 2747.37
   506.3 2757.16   518.4 2763.24   538.7    2777   575.2 2799.86590.3212 2811.52
#Mann= 6 ,-1,0
       0     .06       0    32.3      .1       0   305.7    .045       0
  366.75      .1       0   408.4    .025       0   419.6      .1       0
Bank Sta=305.7,366.75
XS Rating Curve= 0 ,0
Exp/Cntr(USF)=0,0
Exp/Cntr=0.3,0.1

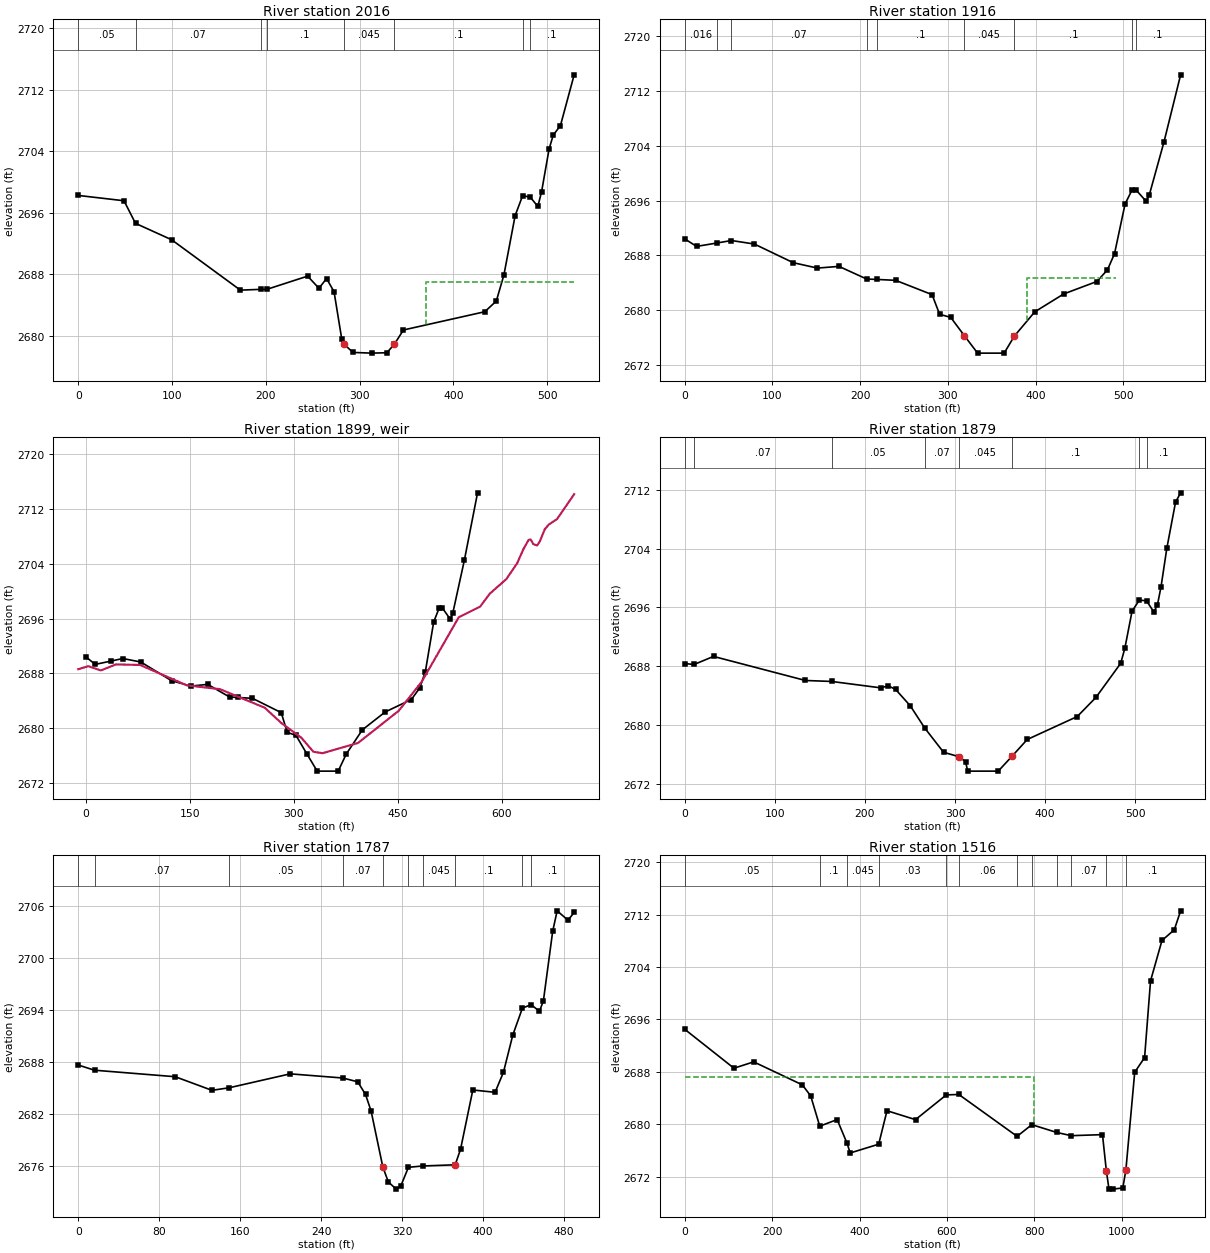
Type RM Length L Ch R = 1 ,2016    ,116.1,99.4,41.8
BEGIN DESCRIPTION:
xs 4
END DESCRIPTION:
XS GIS Cut Line= 3
2219198.33947791516588.0589506122219283.02290418516811.703054129
2219314.20003696517099.678133158
#Sta/Elev= 30
       0 2698.25    48.8 2697.56    61.1 2694.62    99.6 2692.49   172.9 2685.94
   194.6 2686.04   200.8 2686.03   244.6 2687.76   256.7 2686.18   264.8 2687.45
   272.8 2685.73   280.9 2679.65  283.15 2678.96   292.9 2677.84     313 2677.75
   329.1  2677.8   337.2 2678.93   346.8 2680.76   433.5 2683.13   445.8 2684.52
   453.9 2687.91   465.9 2695.64   473.9 2698.23     482 2698.02   490.1 2696.82
   494.1 2698.75   502.1  2704.3   506.5 2706.09   514.2 2707.34   528.8 2713.93
#Mann= 8 ,-1,0
       0     .05       0    61.1     .07       0   194.6    .016       0
   200.8      .1       0  283.15    .045       0   337.2      .1       0
   473.9    .025       0     482      .1       0
#XS Ineff= 2 , 0
                          370.74         2686.98
Permanent Ineff=
       F       F
Bank Sta=283.15,337.2
XS Rating Curve= 0 ,0
Exp/Cntr(USF)=0,0
Exp/Cntr=0.5,0.3

Type RM Length L Ch R = 1 ,1916    ,35.6,37.6,40.9
BEGIN DESCRIPTION:
xs 3
channel burned per available survey data
END DESCRIPTION:
XS GIS Cut Line= 6
2218984.91788567516661.5389446572219149.06733322516793.432166047
2219174.28287073516875.5819520092219224.87344779516939.976332694
2219268.39623194516968.1023553962219286.87591894517100.181015856
#Sta/Elev= 30
       0 2690.41    13.5  2689.3    36.5 2689.79    53.3 2690.16    79.3 2689.65
   123.7 2686.92   151.2 2686.13   175.8 2686.38   207.4 2684.53   219.4 2684.47
   240.4 2684.34  281.88 2682.25  290.49 2679.38  303.17 2678.92  318.63 2676.26
  333.76  2673.7  364.02  2673.7  375.71  2676.2  398.94 2679.74   431.9 2682.35
   469.6 2684.17   481.7 2685.86   489.8 2688.24   501.8  2695.5   509.9 2697.59
   513.9 2697.61   525.9 2695.88   529.5 2696.86     546  2704.5   565.1 2714.38
#Mann= 9 ,-1,0
       0    .016       0    36.5     .05       0    53.3     .07       0
   207.4    .016       0   219.4      .1       0  318.63    .045       0
  375.71      .1       0   509.9    .025       0   513.9      .1       0
#XS Ineff= 3 ,-1
       0     312 2676.32   380.7     390 2676.32     390  491.17 2684.67
Permanent Ineff=
       F       F       F
Bank Sta=318.63,375.71
XS Rating Curve= 0 ,0
Exp/Cntr(USF)=0,0
Exp/Cntr=0.5,0.3

Type RM Length L Ch R = 5 ,1899    ,,,
BEGIN DESCRIPTION:
Bridge No: 54075BSF030, private road
JV notes: channel burned per available survey data
discussed in mapping round up: per survey photos, structure completely failed on US side
culverts are not conveying any flow, more representative to model as an inline
END DESCRIPTION:
IW Pilot Flow=0
#Inline Weir SE= 30
     -112688.595   3.531 2689.04  21.6242688.419  43.441  2689.3  78.3142689.217
 145.6882686.238 193.4642685.681 258.1032682.965 281.6452680.764  311.02 2678.57
  328.27 2676.53  341.45 2676.32  392.72 2677.82 451.4162682.526 484.2752686.722
 538.032  2696.2 568.7572697.741 582.6392699.629  606.712701.781 622.2042704.085
 631.5152706.204 638.8072707.505 641.7252707.553 645.4812706.885 651.0552706.688
 654.7922707.255 662.1512709.072 667.987 2709.76 679.6592710.529  704.442714.177
IW Dist,WD,Coef,Skew,MaxSub,Min_El,Is_Ogee,SpillHt,DesHd
6.27807,22,2.6,0,0.98,, 0 ,,,0,0,
Inline Weir Flap Gates= 0
IW Outlet Rating Curve= 0 ,False,,

Type RM Length L Ch R = 1 ,1879    ,89.1,91.9,126
BEGIN DESCRIPTION:
xs 2
channel burned per survey data, invert = 2674.49
END DESCRIPTION:
XS GIS Cut Line= 6
2218957.65231636516687.7885701752219122.41697609516802.093785198
2219142.51108188516889.3428925012219193.17242614516957.858883878
2219248.56096841516977.9388251012219263.26272747 517090.80638249
#Sta/Elev= 30
       0 2688.36    10.4 2688.23      32 2689.33     134 2686.05     163 2685.92
   217.4 2685.05     226 2685.32   234.1 2684.83   250.3 2682.61   266.5 2679.56
   287.3 2676.27   304.3 2675.67  311.73 2674.99   314.1  2673.7  347.99  2673.7
  363.09  2675.7  380.17 2678.01   435.7 2681.14   456.4 2683.74   483.9 2688.39
   488.5 2690.44   496.5 2695.49   504.6 2697.01   512.6  2696.9   520.7 2695.38
   524.7 2696.36   528.7 2698.85   535.1 2704.07   544.8 2710.36   550.4 2711.62
#Mann= 8 ,-1,0
       0    .016       0    10.4     .07       0     163     .05       0
   266.5     .07       0   304.3    .045       0  363.09      .1       0
   504.6    .025       0   512.6      .1       0
#XS Ineff= 2 , 0
           284.3 2676.32   374.2         2676.32
Permanent Ineff=
       F       F
Bank Sta=304.3,363.09
XS Rating Curve= 0 ,0
Exp/Cntr(USF)=0,0
Exp/Cntr=0.5,0.3

Type RM Length L Ch R = 1 ,1787    ,267.9,270.7,266.7
BEGIN DESCRIPTION:
xs 1, channel burned 1.92'
lidar invert = 2675.29
interpolated invert = 2673.37
channel burn amount = 1.92'
END DESCRIPTION:
XS GIS Cut Line= 4
2218944.04726523516696.0778690562219057.04945838516782.366725402
2219046.03137351516885.9737303012219144.91913157517108.471185928
#Sta/Elev= 30
       0 2687.69    16.1 2687.09    95.8 2686.34   132.1 2684.77   148.9 2685.06
   209.4 2686.67   261.5 2686.19   276.1 2685.75   283.8  2684.3   289.3 2682.39
   300.9 2675.93  306.34  2674.2   314.1 2673.37  318.71 2673.75   326.2 2675.89
   340.3 2676.04   372.4 2676.18   377.7 2677.98   389.8 2684.81   411.8 2684.54
   420.1 2686.87   429.3 2691.15   438.8 2694.26   447.4 2694.65   455.6 2693.89
   459.5 2695.08   468.7 2703.12   473.1 2705.48   483.8  2704.4   489.9 2705.29
#Mann= 10 ,-1,0
       0    .016       0    16.1     .07       0   148.9     .05       0
   261.5     .07       0   300.9    .045       0   326.2     .08       0
   340.3    .045       0   372.4      .1       0   438.8    .025       0
   447.4      .1       0
Bank Sta=300.9,372.4
XS Rating Curve= 0 ,0
Exp/Cntr(USF)=0,0
Exp/Cntr=0.3,0.1

Type RM Length L Ch R = 1 ,1516    ,112.7,113,110.3
XS GIS Cut Line= 4
2218281.92757044516279.2550172472218569.50999898516659.722567058
2218674.73924094516763.9607617892218912.87731688517214.006684845
#Sta/Elev= 30
       0  2694.5   112.7 2688.55   157.8 2689.52   269.1 2686.01   288.2 2684.32
   308.9  2679.7   348.7 2680.71   371.4 2677.08   378.5 2675.61   443.7 2676.95
   462.7 2682.06   527.9  2680.7   598.4 2684.48     627 2684.54   760.2 2678.15
   793.9 2679.93   850.5 2678.75     884 2678.25   955.5 2678.41   964.4 2672.86
   970.3 2670.13   979.2 2670.09    1002 2670.27    1009    2673  1029.2 2687.93
  1051.8 2690.18  1065.4 2701.89  1091.6 2708.06  1119.7 2709.68  1134.2 2712.58
#Mann= 12 ,-1,0
       0     .05       0   308.9      .1       0   371.4    .045       0
   443.7     .03       0   598.4    .016       0     627     .06       0
   760.2    .016       0   793.9     .06       0   850.5    .016       0
     884     .07       0   964.4    .045       0    1009      .1       0
#XS Ineff= 2 , 0
          799.77 2687.21
Permanent Ineff=
       F       F
Bank Sta=964.4,1009
XS Rating Curve= 0 ,0
Exp/Cntr=0.3,0.1

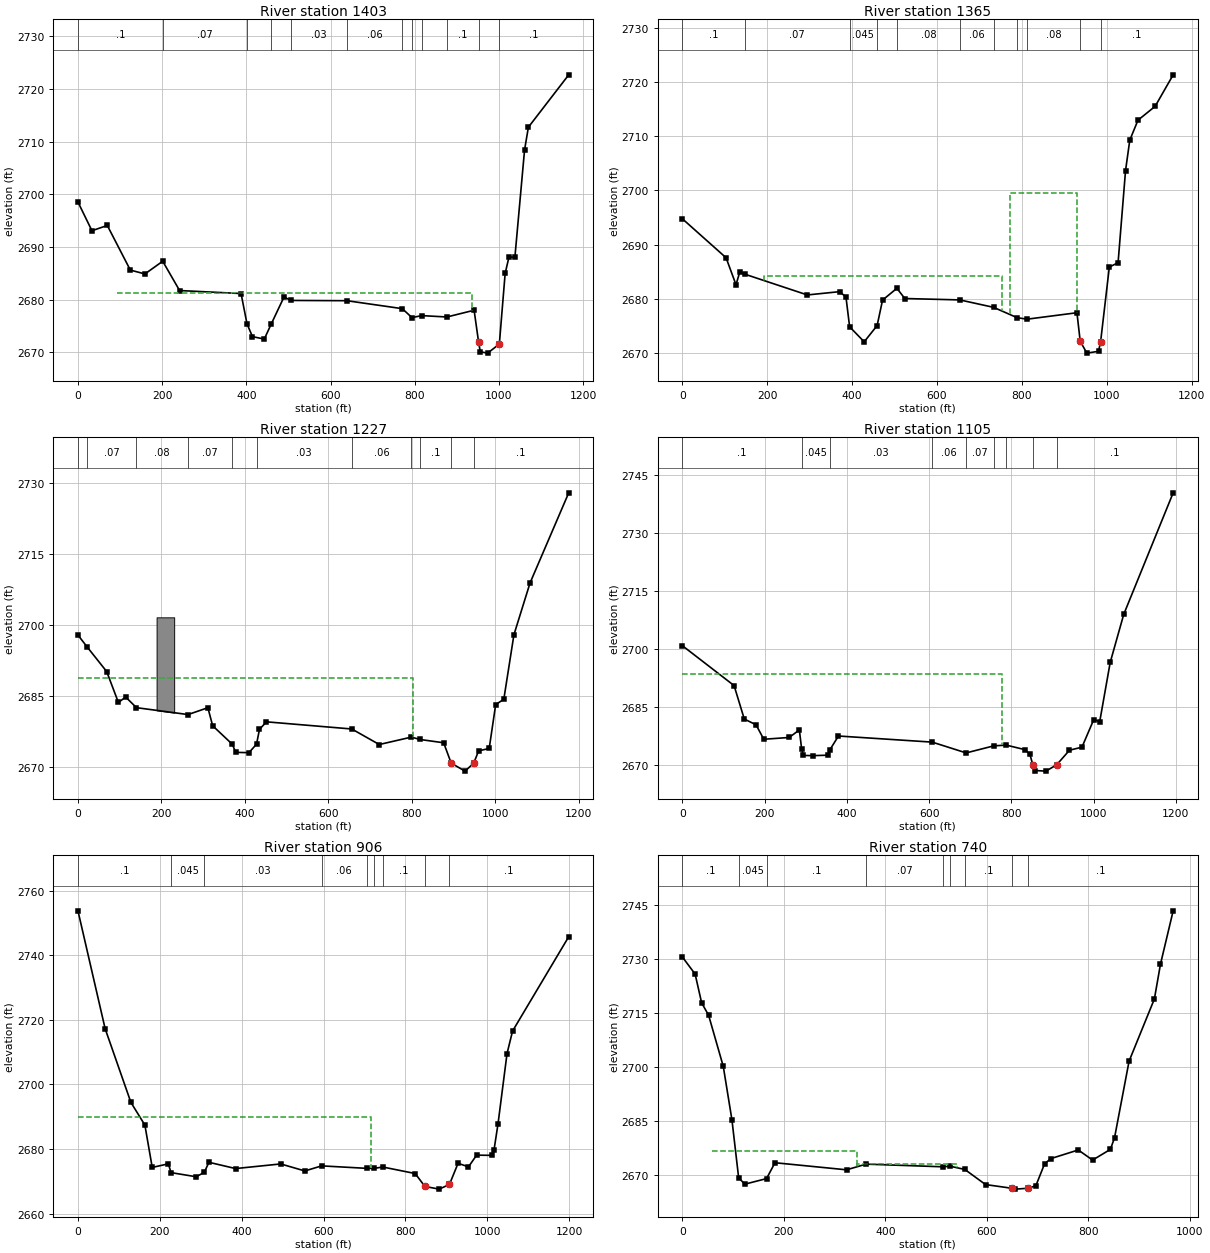
Type RM Length L Ch R = 1 ,1403    ,37.4,38.1,37.8
BEGIN DESCRIPTION:
IFA's placed for structure located along OLDFLDFK1
oldfldfk1 channel burned per survey data
END DESCRIPTION:
XS GIS Cut Line= 5
2218206.01567513516315.132974051 2218343.7167011516525.778327288
2218437.50226473516627.751519491 2218517.8898907516737.168010395
 2218835.7977636 517292.24879544
#Sta/Elev= 30
       0 2698.56    33.2 2693.11    69.7 2694.11   124.4 2685.64   159.1 2684.91
   201.3 2687.32   241.4 2681.76   387.4 2681.19   401.5 2675.44  414.46 2673.01
  442.55 2672.55   459.2 2675.43   489.3 2680.52   506.1 2679.88   638.5 2679.83
   770.3 2678.32   793.3 2676.62   816.4    2677   876.3 2676.74   940.9 2678.02
   951.4 2672.06   955.6 2670.13     973 2669.88  1000.8  2671.6  1014.6    2685
  1023.8 2688.16  1037.7 2688.03  1060.7 2708.44  1069.8 2712.76  1165.6  2722.7
#Mann= 12 ,-1,0
       0      .1       0   201.3     .07       0   401.5    .045       0
   459.2     .07       0   506.1     .03       0   638.5     .06       0
   770.3     .03       0   793.3    .016       0   816.4     .05       0
   876.3      .1       0   951.4    .045       0  1000.8      .1       0
#XS Ineff= 1 ,-1
   92.09  935.462681.254
Permanent Ineff=
       F
Bank Sta=951.4,1000.8
XS Rating Curve= 0 ,0
Exp/Cntr=0.3,0.1

Type RM Length L Ch R = 1 ,1365    ,142.5,138.7,131.7
BEGIN DESCRIPTION:
IFA's placed for structure located along OLDFLDFK1
oldfldfk1 channel burned per survey data
END DESCRIPTION:
XS GIS Cut Line= 5
2218192.13867084516335.9821744372218304.27940906516522.883404817
2218395.92130267516657.9346164482218505.04750492 516786.95675613
 2218804.2958479517314.127987995
#Sta/Elev= 30
       0 2694.75   102.9 2687.55   126.3 2682.56     135 2684.85   146.7 2684.52
   294.4 2680.67   370.6 2681.28   385.4 2680.28     394 2674.78  428.34    2672
   458.8 2675.01   471.6 2679.72   505.4  2681.9     524 2680.01   653.7 2679.75
   733.1 2678.38   788.8 2676.46   812.3 2676.19   929.6 2677.38   937.3 2672.11
   952.9 2669.91   980.5 2670.25   985.4 2672.05  1005.9 2685.83  1026.5 2686.63
  1044.1 2703.67  1054.1  2709.3  1073.4 2712.99  1113.9 2715.56  1156.3 2721.38
#Mann= 11 ,-1,0
       0      .1       0   146.7     .07       0     394    .045       0
   458.8     .07       0   505.4     .08       0   653.7     .06       0
   733.1     .07       0   788.8    .016       0   812.3     .08       0
   937.3    .045       0   985.4      .1       0
#XS Ineff= 2 ,-1
  193.36  753.49 2684.24  771.43   928.9 2699.61
Permanent Ineff=
       F       F
Bank Sta=937.3,985.4
XS Rating Curve= 0 ,0
Exp/Cntr=0.3,0.1

Type RM Length L Ch R = 1 ,1227    ,127.7,121.4,116
XS GIS Cut Line= 5
2218092.31511147516435.1611482232218346.55123993516831.320256038
2218554.22195465517168.452722786 2218644.0869084517280.783914969
2218780.91121301 517373.44836782
#Sta/Elev= 30
       0 2697.86    21.4 2695.41    68.9 2690.12    96.9 2683.57   114.3 2684.73
   140.2 2682.47   263.8 2681.01   311.3 2682.46   322.7 2678.64     370  2674.7
   377.9    2673   409.6 2672.93  427.86 2674.74   434.9 2677.87   451.5 2679.47
   656.1 2677.95   721.9 2674.66   798.9 2676.23   819.2 2675.73   876.2 2675.03
   894.2 2670.71   927.4 2669.02   948.3 2670.71   959.8  2673.3   985.3 2673.84
  1000.8 2683.12  1020.3 2684.25  1044.5 2697.92  1083.1  2708.9  1175.8 2728.01
#Mann= 11 ,-1,0
       0      .1       0    21.4     .07       0   140.2     .08       0
   263.8     .07       0     370    .045       0  427.86     .03       0
   656.1     .06       0   798.9    .016       0   819.2      .1       0
   894.2    .045       0   948.3      .1       0
#XS Ineff= 2 , 0
          803.44 2688.85
Permanent Ineff=
       F       F
#Block Obstruct= 1 ,-1
  188.38  230.54 2701.62
Bank Sta=894.2,948.3
XS Rating Curve= 0 ,0
Exp/Cntr=0.3,0.1

Type RM Length L Ch R = 1 ,1105    ,194.4,199.4,194.1
XS GIS Cut Line= 4
2217939.16081721516611.7991009352218250.84378939517036.946360372
2218589.32545221517386.0944076412218742.37053982517480.797309137
#Sta/Elev= 30
       0 2700.93   125.7 2690.62   150.5 2681.97   179.1 2680.48   197.9 2676.74
   259.6  2677.2   284.4 2679.15  290.03 2674.18   294.3 2672.56   316.5  2672.5
   353.5 2672.62   358.8 2674.04   379.5 2677.58   607.5    2676     690 2673.21
   757.4 2675.04   787.7 2675.22   833.8 2674.03   845.1 2672.81  852.18 2670.11
   856.4 2668.66     884  2668.5   910.1 2670.13   941.3 2673.91   971.6 2674.69
  1000.3 2681.83  1014.8  2681.3  1040.3 2696.61  1073.2 2709.03  1193.4 2740.46
#Mann= 9 ,-1,0
       0      .1       0  290.03    .045       0   358.8     .03       0
   607.5     .06       0     690     .07       0   757.4    .016       0
   787.7      .1       0  852.18    .045       0   910.1      .1       0
#XS Ineff= 2 , 0
          776.59 2693.59
Permanent Ineff=
       F       F
Bank Sta=852.18,910.1
XS Rating Curve= 0 ,0
Exp/Cntr=0.3,0.1

Type RM Length L Ch R = 1 ,906     ,202.4,165.5,136.1
BEGIN DESCRIPTION:
structure xs 4
END DESCRIPTION:
XS GIS Cut Line= 5
 2217741.0812633516873.1824298022217895.25658619516923.212832593
 2218036.1585369517079.430212736 2218460.1445812517533.529097381
2218641.42964094517629.233180139
#Sta/Elev= 30
       0 2753.74    66.3 2717.28   129.3 2694.41   163.5 2687.38   181.4 2674.27
   220.8 2675.38  227.37 2672.66   288.9 2671.38   308.6 2672.76   319.9 2675.86
     385 2673.92   495.3 2675.35   554.2 2673.18   595.2 2674.75   704.8 2673.99
   724.2 2673.99   744.5  2674.4   823.7 2672.38  847.42 2668.38   882.4 2667.55
   907.4    2669   928.4 2675.55   953.9 2674.45   973.7 2678.07  1011.9 2678.01
  1016.4 2679.82  1026.1 2687.85    1048 2709.52  1061.5  2716.5  1198.7 2745.72
#Mann= 9 ,-1,0
       0      .1       0  227.37    .045       0   308.6     .03       0
   595.2     .06       0   704.8     .07       0   724.2    .016       0
   744.5      .1       0  847.42    .045       0   907.4      .1       0
#XS Ineff= 2 , 0
          714.63    2690
Permanent Ineff=
       F       F
Bank Sta=847.42,907.4
XS Rating Curve= 0 ,0
Exp/Cntr=0.5,0.3

Type RM Length L Ch R = 1 ,740     ,54.7,68.5,56
BEGIN DESCRIPTION:
structure xs 3
channel not burned - survey data did not provide invert information
END DESCRIPTION:
XS GIS Cut Line= 6
2217688.59709019517214.2767742922217946.12714343517309.617687617
2218126.94611698517500.2995142682218267.21780555 517546.32616208
2218349.40824807 517546.326162082218462.28312247517711.802919691
#Sta/Elev= 30
       0 2730.51    25.1 2725.77    37.9 2717.79    51.7 2714.31    80.6 2700.09
    97.7  2685.2   110.9 2669.12   123.1 2667.35   165.9  2668.9   182.5 2673.31
   323.6 2671.34   362.2 2672.92   513.4 2672.18   527.6 2672.34   556.7 2671.45
   597.6 2667.24     650  2666.2   656.3 2665.97   681.3 2666.21   696.8 2666.91
     714 2672.99     726 2674.44   780.4 2676.86   808.7 2674.05   843.7 2677.02
   851.9 2680.24   880.6 2701.56   930.5 2718.86   942.5 2728.54   967.5 2743.36
#Mann= 9 ,-1,0
       0      .1       0   110.9    .045       0   165.9      .1       0
   362.2     .07       0   513.4    .016       0   527.6     .07       0
   556.7      .1       0     650    .045       0   681.3      .1       0
#XS Ineff= 3 ,-1
   57.46  344.79 2676.71  344.79   541.22672.889   729.4   967.5 2673.93
Permanent Ineff=
       F       F       F
Bank Sta=650,681.3
XS Rating Curve= 0 ,0
Exp/Cntr(USF)=0,0
Exp/Cntr=0.5,0.3