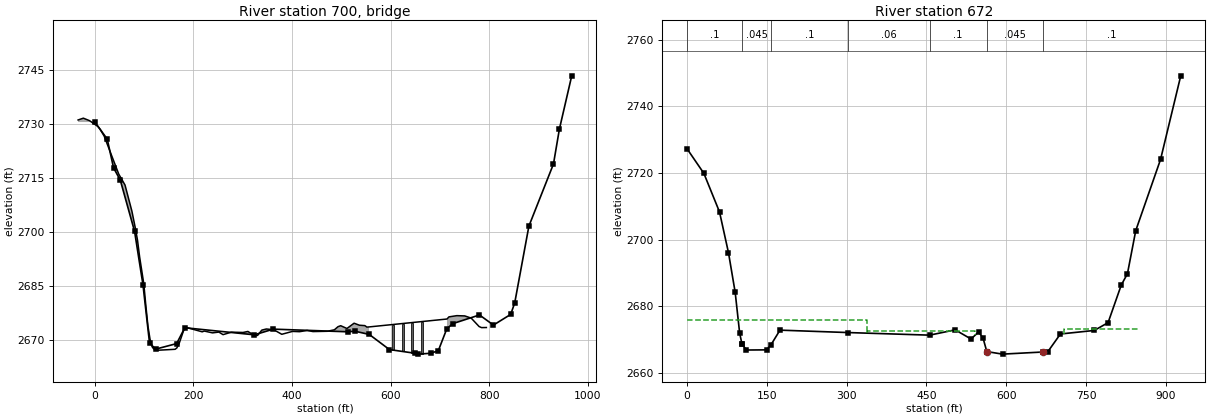
HEC-RAS study BIGSPRFK.prj: BIGSPRFK

--- BIGSPRFK.g01 (geometry) --- (continued)

Type RM Length L Ch R = 3 ,700     ,,,
BEGIN DESCRIPTION:
Bridge No.: 54075BSF020
JV notes: limited survey data - road deck assumed based on available lidar
road specifications measured off of aerial imagery based on placement of piers
survey did not capture channel invert so channel not burned
per survey photos - structure has no deck
4 elongated puers with semi-circular ends, assumed 4' width based on photos and leaf-off aerial imagery
END DESCRIPTION:
Bridge Culvert--1,0,-1,-1, 0
Deck Dist Width WeirC Skew NumUp NumDn MinLoCord MaxHiCord MaxSubmerge Is_Ogee
15,15,2.6,0, 60, 60, , , 0.98, 0, 0,0,,
     -34 -23.417 -10.722   6.204  10.435  18.898  48.519  61.213  75.117  82.371
  86.602  90.846  99.297 103.528  107.76 111.991 116.223 119.159 128.917 162.769
 166.346 171.232 179.695 183.927 217.779  222.01 238.701 251.631 260.094 277.025
  300.67 310.478 324.315 330.226 338.787  347.96 362.953 379.251 400.981 415.223
 430.719 442.541 471.841 485.996 493.336 498.769 511.475 525.932 536.798 547.801
 551.882 556.186 714.414 718.414 734.415  750.42 763.467 779.636 784.529 794.316
2731.0862731.5862730.8882729.2612728.537  2726.62716.0252712.9912705.7542700.869
2697.5942692.9962685.526 2679.37 2673.722670.0742668.0022667.4612667.0592667.313
 2667.692669.0172672.3882673.4492672.1752672.3842671.8822672.1012671.3882672.077
2671.9932672.2752671.0972671.1882672.6512672.961 2672.752671.4872672.2892672.211
2672.5532672.2442672.3242672.741  2673.62673.8722673.1012674.5692674.0072673.899
2673.4942673.5322675.7342676.3292676.6712676.5992675.9942673.6382673.3442673.369
                                                                                
                                                                                
                                                                                
                                                                                
                                                                                
        2673.5222675.634
     -44 -33.417 -20.722    .435   8.898  38.519  51.213  65.117  76.602  80.846
  89.297   97.76 101.991 106.223 109.159 118.917 156.346 173.927 207.779 241.631
 250.094 300.478 314.315  337.96 352.953 369.251 390.981 461.841 488.769 501.475
 515.932 541.882 546.186 704.414 708.414  740.42 753.467 769.636 784.316 808.783
  818.57 828.039 833.251 843.038 848.871 856.931 867.505 876.646 887.079 911.547
  916.44 921.334 931.121 943.048 945.801  954.53 960.481 970.268 980.0551001.711
2731.0862731.5862730.8882728.537  2726.62716.0252712.9912705.7542697.5942692.996
2685.526 2673.722670.0742668.0022667.4612667.059 2667.692673.4492672.1752672.101
2671.3882672.2752671.0972672.961 2672.752671.4872672.2892672.3242673.8722673.101
2674.5692673.4942673.5322675.7342676.3292676.5992675.9942673.6382673.3692675.117
2677.5572679.0682682.6812692.4242696.8242701.6692703.7582707.0912712.7992722.904
2725.9992731.083 2737.032745.7542747.4072750.8462756.3062760.7312767.9642777.969
                                                                                
                                                                                
                                                                                
                2673.5222675.634
                                                                                
                                                                                
Pier Skew, UpSta & Num, DnSta & Num=  ,604.3, 2 ,594.3, 2 , 0 , 0 , 0 ,,
       4       4
       0    2674
       4       4
       0    2674
Pier Skew, UpSta & Num, DnSta & Num=  ,624.3, 2 ,614.3, 2 , 0 , 0 , 0 ,,
       4       4
       0  2674.7
       4       4
       0  2674.7
Pier Skew, UpSta & Num, DnSta & Num=  ,644.3, 2 ,634.3, 2 , 0 , 0 , 0 ,,
       4       4
       0  2675.7
       4       4
       0  2675.7
Pier Skew, UpSta & Num, DnSta & Num=  ,664.3, 2 ,654.3, 2 , 0 , 0 , 0 ,,
       4       4
       0  2676.3
       4       4
       0  2676.3
BR Coef=-1 ,-1 , 0 ,, 0 ,,,0.8,0,1.33,0,
WSPro=,,,, 1 ,,,, 0 ,,,, 0 ,,,,-1 ,-1 ,-1 , 0 , 0 , 0 , 0 , 0
BR U #Sta/Elev= 30
       0 2730.51    25.1 2725.77    37.9 2717.79    51.7 2714.31    80.6 2700.09
    97.7  2685.2   110.9 2669.12   123.1 2667.35   165.9  2668.9   182.5 2673.31
   323.6 2671.34   362.2 2672.92   513.4 2672.18   527.6 2672.34   556.7 2671.45
   597.6 2667.24     650  2666.2   656.3 2665.97   681.3 2666.21   696.8 2666.91
     714 2672.99     726 2674.44   780.4 2676.86   808.7 2674.05   843.7 2677.02
   851.9 2680.24   880.6 2701.56   930.5 2718.86   942.5 2728.54   967.5 2743.36
BR U #Mann= 9
       0      .1   110.9     .04   165.9      .1   362.2     .07   513.4    .016
   527.6     .07   556.7      .1     650     .04   681.3      .1
BR D #Sta/Elev= 30
       0 2727.24    31.5  2719.9    60.9 2708.34    77.8  2696.1    90.4  2684.2
    98.8    2672     103 2668.84     103 2668.79   111.4 2666.94   149.3 2666.99
   157.7 2668.51   174.6  2672.9     302 2672.18     456  2671.4   504.1 2672.99
   533.8 2670.24   548.1 2672.37   556.4 2670.52  563.49 2666.47     593 2665.71
   669.4 2666.35   677.8 2666.35   701.9 2671.75   765.6 2672.81   791.5 2675.15
   816.2 2686.39   827.9 2689.82   843.5 2702.73   890.2  2724.1   928.1 2749.14
BR D #Mann= 7
       0      .1     103     .04   157.7      .1     302     .06     456      .1
  563.49     .04   669.4      .1
BC Design=,, 0 ,, 0 ,,,,,,
BC Use User HTab Curves=0
BC User HTab FreeFlow(D)= 0

Type RM Length L Ch R = 1 ,672     ,150.8,200.7,240.1
BEGIN DESCRIPTION:
structure xs 2
channel not burned - survey data did not provide invert information
END DESCRIPTION:
XS GIS Cut Line= 6
2217682.25107533517261.1259563372217922.70284137517339.723917078
2218114.52122089517544.7960903862218255.16320731517587.969319625
2218323.10730646517591.2569373262218421.81781026517740.830292864
#Sta/Elev= 30
       0 2727.24    31.5  2719.9    60.9 2708.34    77.8  2696.1    90.4  2684.2
    98.8    2672     103 2668.84     103 2668.79   111.4 2666.94   149.3 2666.99
   157.7 2668.51   174.6  2672.9     302 2672.18     456  2671.4   504.1 2672.99
   533.8 2670.24   548.1 2672.37   556.4 2670.52  563.49 2666.47     593 2665.71
   669.4 2666.35   677.8 2666.35   701.9 2671.75   765.6 2672.81   791.5 2675.15
   816.2 2686.39   827.9 2689.82   843.5 2702.73   890.2  2724.1   928.1 2749.14
#Mann= 7 ,-1,0
       0      .1       0     103    .045       0   157.7      .1       0
     302     .06       0     456      .1       0  563.49    .045       0
   669.4      .1       0
#XS Ineff= 3 ,-1
       0  337.46    2676  337.46   542.2 2672.66   708.4     850  2673.3
Permanent Ineff=
       F       F       F
Bank Sta=563.49,669.4
XS Rating Curve= 0 ,0
Exp/Cntr=0.5,0.3