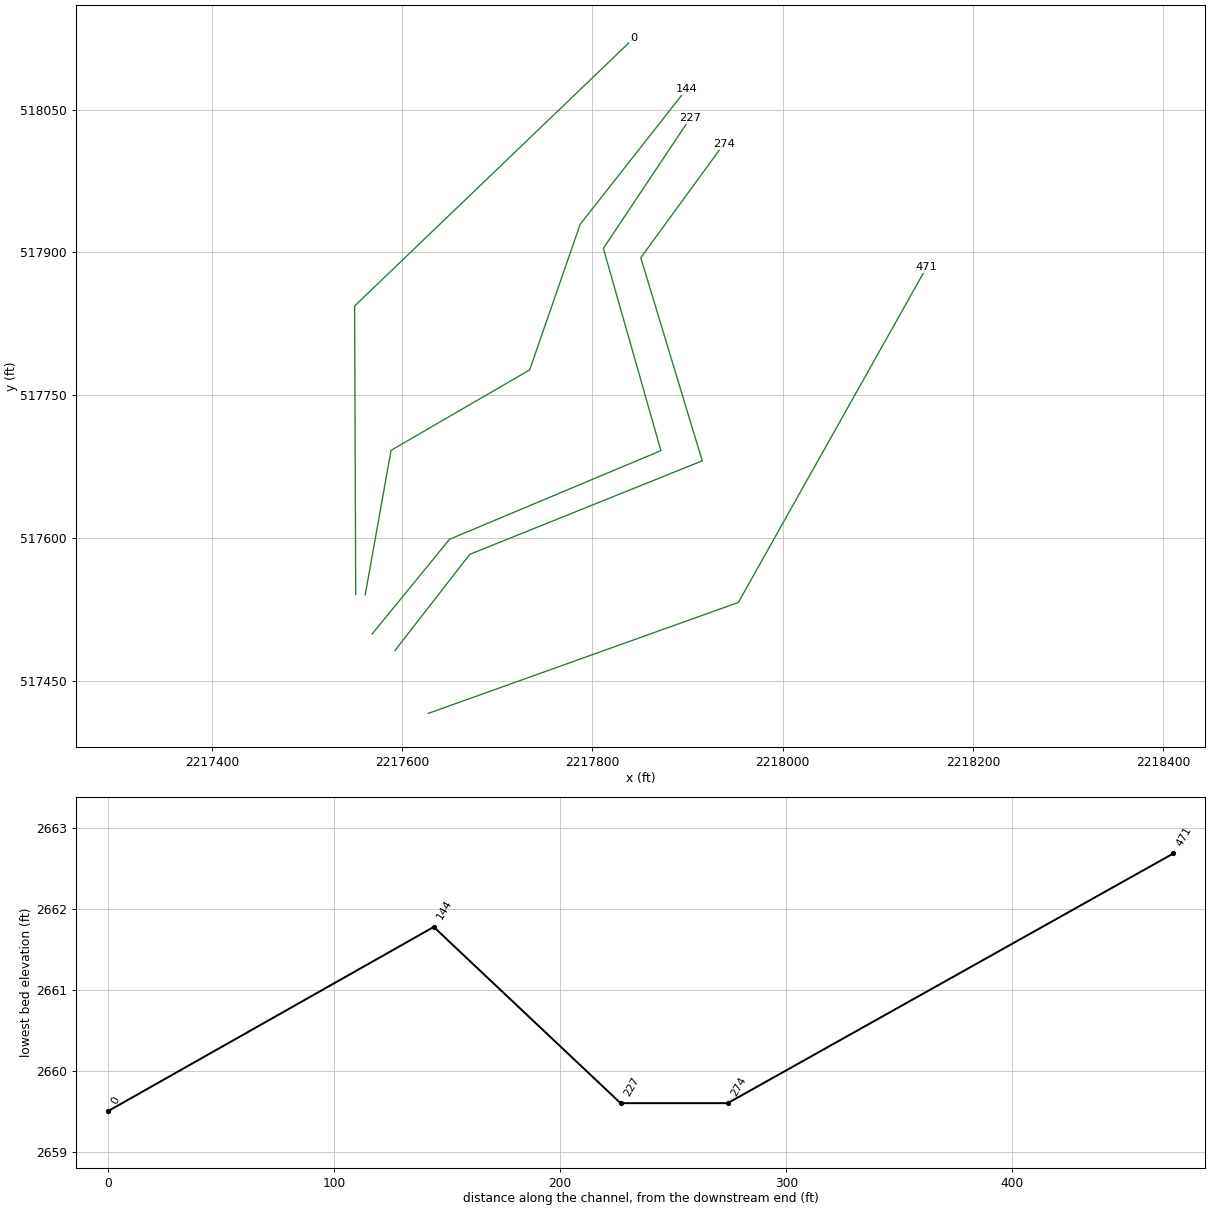
HEC-RAS study BIGSPRFK.prj: BIGSPRFK

--- BIGSPRFK.g01 (geometry) --- (continued)

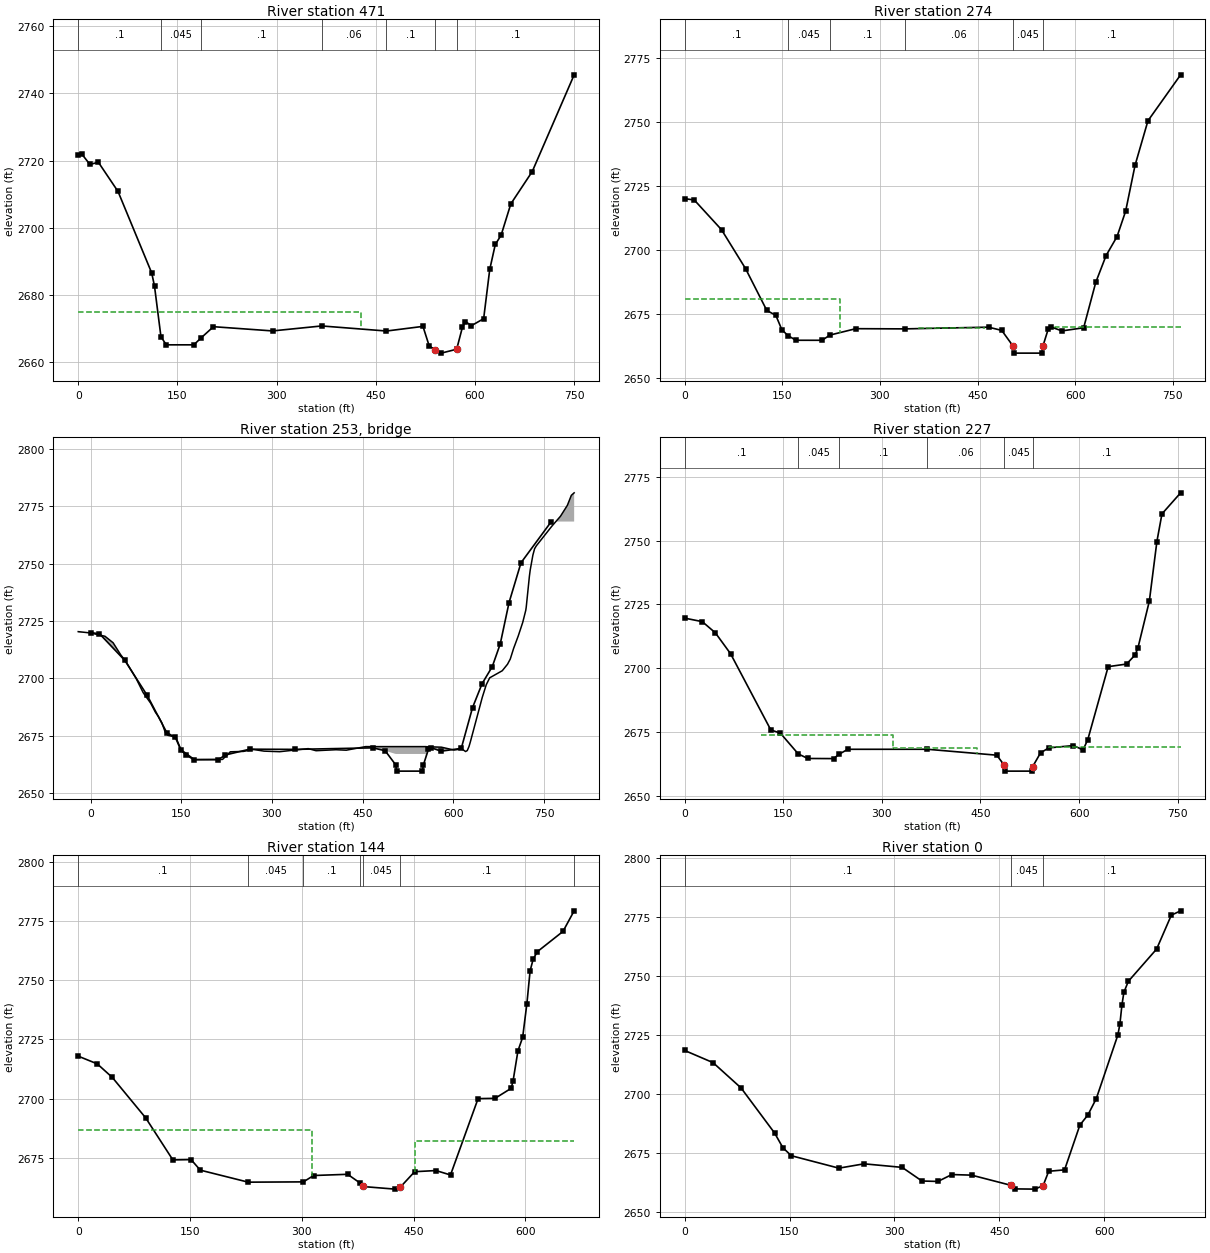
Type RM Length L Ch R = 1 ,471     ,182.4,197.1,225
BEGIN DESCRIPTION:
xs 4
END DESCRIPTION:
XS GIS Cut Line= 3
2217627.48961915517415.5813455892217953.25007648517532.124957478
 2218151.2338027517884.564072952
#Sta/Elev= 30
       0 2721.53       5 2722.06    17.7 2718.87    30.5 2719.51    60.2 2710.82
   111.2 2686.54   115.4 2682.63  125.16 2667.56   133.2 2665.16   174.9 2665.16
  185.55 2667.17   204.6 2670.56   293.9  2669.3   368.3 2670.78   466.3 2669.27
   521.5 2670.65     531 2664.79     540  2663.7   549.1 2662.69   572.5 2663.85
   581.2 2670.42   585.8 2672.06   594.9 2670.88   613.3 2672.94   622.5 2687.59
   630.9 2695.04   639.7 2697.79   654.4 2707.12   686.8 2716.75   750.2 2745.54
#Mann= 7 ,-1,0
       0      .1       0  125.16    .045       0  185.55      .1       0
   368.3     .06       0   466.3      .1       0     540    .045       0
   572.5      .1       0
#XS Ineff= 2 , 0
          427.31 2675.01
Permanent Ineff=
       F       F
Bank Sta=540,572.5
XS Rating Curve= 0 ,0
Exp/Cntr=0.5,0.3

Type RM Length L Ch R = 1 ,274     ,45.6,47.4,46.6
BEGIN DESCRIPTION:
xs 3
channel not burned - survey data did not provide invert information
END DESCRIPTION:
XS GIS Cut Line= 5
2217592.38612159517481.5759209962217671.01795612517582.673993961
2217915.33829911517680.9637871212217850.74786361517894.393052268
2217937.80453755518013.744943963
#Sta/Elev= 30
       0 2719.99    14.7 2719.49    56.6 2707.86    93.6 2692.62   126.2 2676.29
   140.1 2674.36   149.3 2668.77   158.6 2666.48   170.9 2664.63   211.2 2664.62
   223.1 2666.65     263 2669.16 338.401 2669.08   466.9 2669.75   487.2 2668.49
   504.5 2662.39   506.4  2659.6   548.8  2659.6   550.5 2662.36   558.8 2669.12
     563 2669.83   579.7 2668.29   613.1 2669.52   631.7 2687.27   647.6 2697.77
   664.4 2705.17   677.6  2715.1   692.1 2733.07 711.901 2750.45   762.1 2768.42
#Mann= 6 ,-1,0
       0      .1       0   158.6    .045       0   223.1      .1       0
 338.401     .06       0   504.5    .045       0   550.5      .1       0
#XS Ineff= 3 ,-1
       0  238.58 2680.61  359.68  461.382669.463   569.3   762.12669.996
Permanent Ineff=
       F       F       F
Bank Sta=504.5,550.5
XS Rating Curve= 0 ,0
Exp/Cntr=0.5,0.3

Type RM Length L Ch R = 3 ,253     ,,,
BEGIN DESCRIPTION:
Bridge No.: 54075BSF010, Rail Road
JV notes: limited survey data - road deck assumed based on available lidar
road specifications measured off of aerial imagery
survey did not capture channel invert so channel was burned based on the effective data
Deck thickness from effective profile
old railroad crossing
END DESCRIPTION:
Bridge Culvert--1,0,-1,-1, 0
Deck Dist Width WeirC Skew NumUp NumDn MinLoCord MaxHiCord MaxSubmerge Is_Ogee
15,15,2.6,0, 60, 60, , , 0.98, 0, 0,0,,
   -20.5   -.134  23.752  37.196  49.639  58.279  75.314  86.968  99.411 107.311
 112.223 117.756 123.709 128.004 140.891 149.482  169.99 175.255 218.211 231.097
 252.575 269.757 286.939 312.713 359.964  372.85 405.875 422.844 454.912 456.781
 554.349 554.858 580.322 601.013 614.224 620.197 623.051 625.905  628.05 647.872
 654.479 660.159 680.907 689.609 694.121  699.66 707.335 714.737 719.762  720.55
 725.812 727.157  731.52 734.375 737.229 762.919 777.192  788.61 795.147 799.816
2720.422 2719.832718.4032715.5712710.3722707.4132699.9882693.8042689.1932685.212
2683.3842680.7172676.3972675.2062674.4092668.958 2664.952664.5942664.702 2668.03
2668.1952669.0212668.313 2668.072669.411  2668.52668.9272668.7222670.294 2670.29
2670.2852670.262 2670.042668.8022669.2622668.1422668.5692670.3452672.2762691.799
2697.2982700.2962703.369 2706.212708.4512713.0862718.5262724.4272729.6882731.087
2744.6282747.3122753.7432756.5652757.8232766.3862770.7272775.4922779.8442780.936
                                                                                
                                                                                
                                                                         2667.09
 2667.09
                                                                                
                                                                                
 296.736 306.713 315.408 324.519 332.486 345.372 353.964 362.555  366.85 371.147
 382.907 399.875 404.117 416.844 433.812 448.911 450.781 548.349 548.858 558.263
 574.323 589.613 595.013 603.497 608.224 614.198 617.051 618.274 619.906  622.05
 625.615 638.378 641.871 648.478 654.159 674.906 683.609 685.559 688.121 693.659
 696.976 701.335 705.538 708.737 711.248 713.762  714.55 719.812 721.157  725.52
 728.375 731.229 736.938 756.919 771.192 779.755 782.609 789.147 791.173 793.816
 2668.26 2668.072668.1622668.7182668.6362668.9832669.4112668.641  2668.52668.778
2668.5962668.9272668.6882668.722 2669.742670.294 2670.292670.2852670.2622669.963
 2670.042668.9592668.8022669.2952669.2622668.1422668.5692669.1522670.3452672.276
2675.9142688.1422691.7992697.2982700.2962703.369 2706.212707.0082708.4512713.086
2715.2312718.5262722.0882724.4272726.8832729.6882731.0872744.6282747.3122753.743
2756.5652757.8232759.5372766.3862770.7272774.1132775.4922779.8442780.4812780.936
                                                                                
                                                 2667.09 2667.09
                                                                                
                                                                                
                                                                                
                                                                                
BR Coef=-1 ,-1 , 0 ,, 0 ,,,0.8,0,0.2,0,
WSPro=,,,, 1 ,,,, 0 ,,,, 0 ,,,,-1 ,-1 ,-1 , 0 , 0 , 0 , 0 , 0
BR U #Sta/Elev= 30
       0 2719.99    14.7 2719.49    56.6 2707.86    93.6 2692.62   126.2 2676.29
   140.1 2674.36   149.3 2668.77   158.6 2666.48   170.9 2664.63   211.2 2664.62
   223.1 2666.65     263 2669.16 338.401 2669.08   466.9 2669.75   487.2 2668.49
   504.5 2662.39   506.4  2659.6   548.8  2659.6   550.5 2662.36   558.8 2669.12
     563 2669.83   579.7 2668.29   613.1 2669.52   631.7 2687.27   647.6 2697.77
   664.4 2705.17   677.6  2715.1   692.1 2733.07 711.901 2750.45   762.1 2768.42
BR U #Mann= 6
       0      .1   158.6     .04   223.1      .1 338.401     .06   504.5     .04
   550.5      .1
BR D #Sta/Elev= 30
       0 2719.59    26.8 2718.21    46.7 2713.82    69.8 2705.64     131 2675.76
   145.6 2674.49   172.8 2666.34   187.3 2664.56   226.5 2664.51   235.1 2666.25
   248.1 2668.16 369.299 2668.17   474.8 2665.85  486.41 2661.84   487.3  2659.6
 528.801  2659.6  529.44 2661.39   541.4 2666.76   553.9 2668.72   591.5 2669.62
   606.1 2667.93   613.3 2671.99   644.3 2700.56   672.3 2701.58   685.4  2705.2
   689.6 2707.96   706.9 2726.24 718.401 2749.61   726.1 2760.46   754.5 2768.72
BR D #Mann= 6
       0      .1   172.8     .04   235.1      .1 369.299     .06  486.41     .04
  529.44      .1
BC Design=,, 0 ,, 0 ,,,,,,
BC Use User HTab Curves=0
BC User HTab FreeFlow(D)= 0

Type RM Length L Ch R = 1 ,227     ,100.2,82.6,61.5
BEGIN DESCRIPTION:
xs 2
channel not burned - survey data did not provide invert information
END DESCRIPTION:
XS GIS Cut Line= 5
 2217568.5274251517499.0729790042217649.69829891517598.494062926
2217871.91205877 517691.671495722217811.43194634517904.222031585
2217902.51946164518040.830609655
#Sta/Elev= 30
       0 2719.59    26.8 2718.21    46.7 2713.82    69.8 2705.64     131 2675.76
   145.6 2674.49   172.8 2666.34   187.3 2664.56   226.5 2664.51   235.1 2666.25
   248.1 2668.16 369.299 2668.17   474.8 2665.85  486.41 2661.84   487.3  2659.6
 528.801  2659.6  529.44 2661.39   541.4 2666.76   553.9 2668.72   591.5 2669.62
   606.1 2667.93   613.3 2671.99   644.3 2700.56   672.3 2701.58   685.4  2705.2
   689.6 2707.96   706.9 2726.24 718.401 2749.61   726.1 2760.46   754.5 2768.72
#Mann= 6 ,-1,0
       0      .1       0   172.8    .045       0   235.1      .1       0
 369.299     .06       0  486.41    .045       0  529.44      .1       0
#XS Ineff= 3 ,-1
  116.73     317 2673.72  317.49  445.482668.625 554.001   754.5    2669
Permanent Ineff=
       F       F       F
Bank Sta=486.41,529.44
XS Rating Curve= 0 ,0
Exp/Cntr=0.5,0.3

Type RM Length L Ch R = 1 ,144     ,162.6,144.1,127.4
XS GIS Cut Line= 5
2217561.16016962517540.1230808892217588.31994141517691.970895887
  2217733.995081517776.536548955 2217787.0800895517929.618899034
2217898.80551435518071.590433381
#Sta/Elev= 30
       0 2717.92    25.5 2714.67    45.8 2708.92    90.5 2691.87     127 2674.11
   151.4 2674.25   163.8 2669.79   228.1 2664.72   302.1 2664.84   315.9 2667.53
   361.5 2668.04   378.2 2664.34   381.5 2662.89     425 2661.78   431.8 2662.49
   451.4 2669.14     480 2669.62   499.5 2667.76   536.5 2699.99   559.3 2700.11
   580.9 2704.34   583.5 2707.58     590 2720.17   596.3 2725.85     602 2740.14
   606.3 2753.92   610.5 2758.98   616.2 2762.07   650.4 2770.57   665.4 2779.27
#Mann= 7 ,-1,0
       0      .1       0   228.1    .045       0   302.1      .1       0
   378.2     .04       0   381.5    .045       0   431.8      .1       0
   665.4      .1       0
#XS Ineff= 2 , 0
          313.95  2686.8  451.81            2682
Permanent Ineff=
       F       F
Bank Sta=381.5,431.8
XS Rating Curve= 0 ,0
Exp/Cntr=0.3,0.1

Type RM Length L Ch R = 1 ,0       ,143.6,232.3,225.5
BEGIN DESCRIPTION:
shared xs with OLDFLDFK
END DESCRIPTION:
XS GIS Cut Line= 3
2217551.17535133 517540.54482427 2217550.0206046517843.669238932
2217843.18412614518124.963528206
#Sta/Elev= 30
       0 2718.29    40.6 2713.13    80.6 2702.42   128.6  2683.3   140.6 2677.01
   152.6 2673.66   220.6 2668.39   256.6 2670.23   311.1 2668.72   339.4 2662.94
   362.3 2662.76   382.1 2665.68   410.4 2665.43466.98792661.095   472.6  2659.6
   500.9  2659.5512.68772660.967   520.7 2667.07   543.4 2667.67   565.3 2686.65
   576.8 2690.96   588.8  2697.9   619.7 2724.91   622.6 2729.65   625.4 2737.43
   628.2 2742.89   634.6 2747.61   675.1 2761.31   696.1 2775.66   709.4  2777.5
#Mann= 3 ,-1,0
       0      .1       0466.9879    .045       0512.6877      .1       0
Bank Sta=466.9879,512.6877
XS Rating Curve= 0 ,0
Exp/Cntr(USF)=0,0
Exp/Cntr=0.3,0.1
LCMann Table=0

Chan Stop Cuts=-1
Use User Specified Reach Order=0
Composite Channel Slope=5